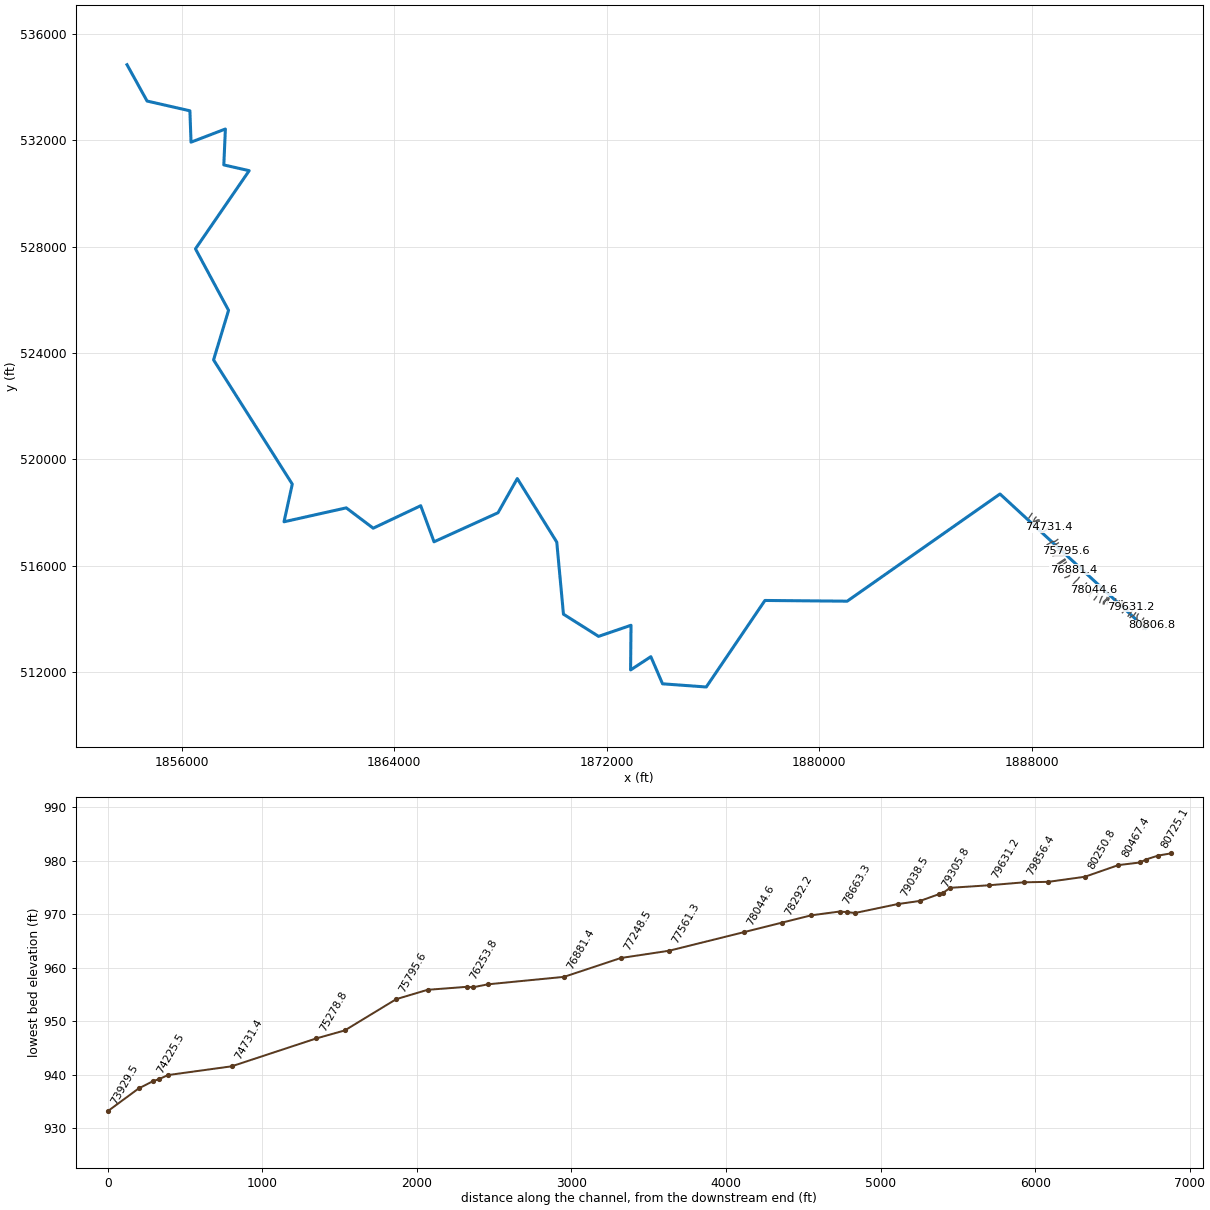
--- FALLINGRCR.prj (project) ---

Proj Title=FALLINGRCR
Current Plan=p01
Default Exp/Contr=0,0
English Units
Geom File=g01
Flow File=f01
Plan File=p01
BEGIN DESCRIPTION:
END DESCRIPTION:
DSS Export Rating Curves= 0
DSS Export Rating Curve Sorted= 0
DSS Export Volume Flow Curves= 0
DXF OffsetX= 0
DXF OffsetY= 0
DXF ScaleX= 0
DXF ScaleY= 0

--- FALLINGRCR.p01 (plan) ---

Plan Title=Floodplain
Program Version=4.00
Geom File=g01
Flow File=f01
K Sum by GR=0
Std Step Tol=0.01
Critical Tol=0.01
Num of Std Step Trials=20
Max Error Tol=0.3
Flow Tol Ratio=0.001
Split Flow NTrial=30
Split Flow Tol=0.02
Split Flow Ratio=0.02
Log Output Level=0
Friction Slope Method=1
Unsteady Friction Slope Method=2
Unsteady Bridges Friction Slope Method=1
Global Log Level=0
CheckData=False
Run HTab=0
Run UNet=0
Run PostProcess=0
UNET Theta=0
UNET Theta Warmup=0
UNET ZTol=0
UNET ZSATol=0
UNET MxIter=0
UNET MaxInSteps=0
UNET DtIC=0
UNET DtMin=0
UNET MaxCRTS=0
UNET WFStab=0
UNET SFStab=0
UNET WFX=0
UNET SFX=0
UNET DSS MLevel=0
UNET DZMax Abort=0
UNET Convert EG Bridges=0
UNET Use Existing IB Tables=0
UNET Froude Limit=0
UNET Froude Power=0
Write IC File=0
Echo Input=False
Echo Output=False
Write Detailed=0

--- FALLINGRCR.f01 (steady flow) ---

Flow Title=NFF Regression Equation
Program Version=4.10
Number of Profiles= 1
Profile Names=P100yr
River Rch & RM=FALLINGRCR,Main            ,80806.8
679.1446
River Rch & RM=FALLINGRCR,Main            ,80644.1
984.3234
River Rch & RM=FALLINGRCR,Main            ,79185.2
1039.641
River Rch & RM=FALLINGRCR,Main            ,76389.4
1119.403
River Rch & RM=FALLINGRCR,Main            ,72390.6
1426.589
River Rch & RM=FALLINGRCR,Main            ,67482.5
1580.656
River Rch & RM=FALLINGRCR,Main            ,63581.9
2456.726
River Rch & RM=FALLINGRCR,Main            ,56271.9
2911.237
River Rch & RM=FALLINGRCR,Main            ,53726.5
3098.357
River Rch & RM=FALLINGRCR,Main            ,47144
3382.919
River Rch & RM=FALLINGRCR,Main            ,46355.3
3593.804
River Rch & RM=FALLINGRCR,Main            ,43037.2
 3777.96
River Rch & RM=FALLINGRCR,Main            ,34755.2
3952.716
River Rch & RM=FALLINGRCR,Main            ,19052.3
4386.752
River Rch & RM=FALLINGRCR,Main            ,5342.9
4832.067
Boundary for River Rch & Prof#=FALLINGRCR,Main            , 1
Up Type= 0
Dn Type= 3
Dn Slope=0.0016
DSS Import GetInterval= 0
DSS Import GetPeak= 0
DSS Import FillOption= 0

--- FALLINGRCR.g01 (geometry) ---

Geom Title=USGS 10m DEM
Program Version=4.10

River Reach=FALLINGRCR      ,Main
Reach XY= 30
     1892298.122      513656.497     1886813.516      518702.739
     1881058.558      514674.076     1877962.215      514701.307
     1875751.977      511449.362      1874105.99       511568.78
      1873665.74      512588.318     1872902.026      512089.812
     1872918.702      513768.884     1871696.618      513352.009
     1870374.552      514184.995      1870121.62      516895.431
     1868635.623      519282.699     1867909.482      517997.193
     1865500.173        516906.1     1864998.471      518261.692
     1863209.137      517417.212     1862194.651      518181.251
     1859850.769      517657.824     1860162.012      519072.803
     1857198.133      523742.113     1857762.195      525604.274
     1856516.188      527914.962      1858538.88      530852.816
      1857583.62      531068.921       1857642.8      532418.942
     1856349.121      531924.184     1856306.295      533102.882
     1854693.704       533469.95     1853938.408      534834.829

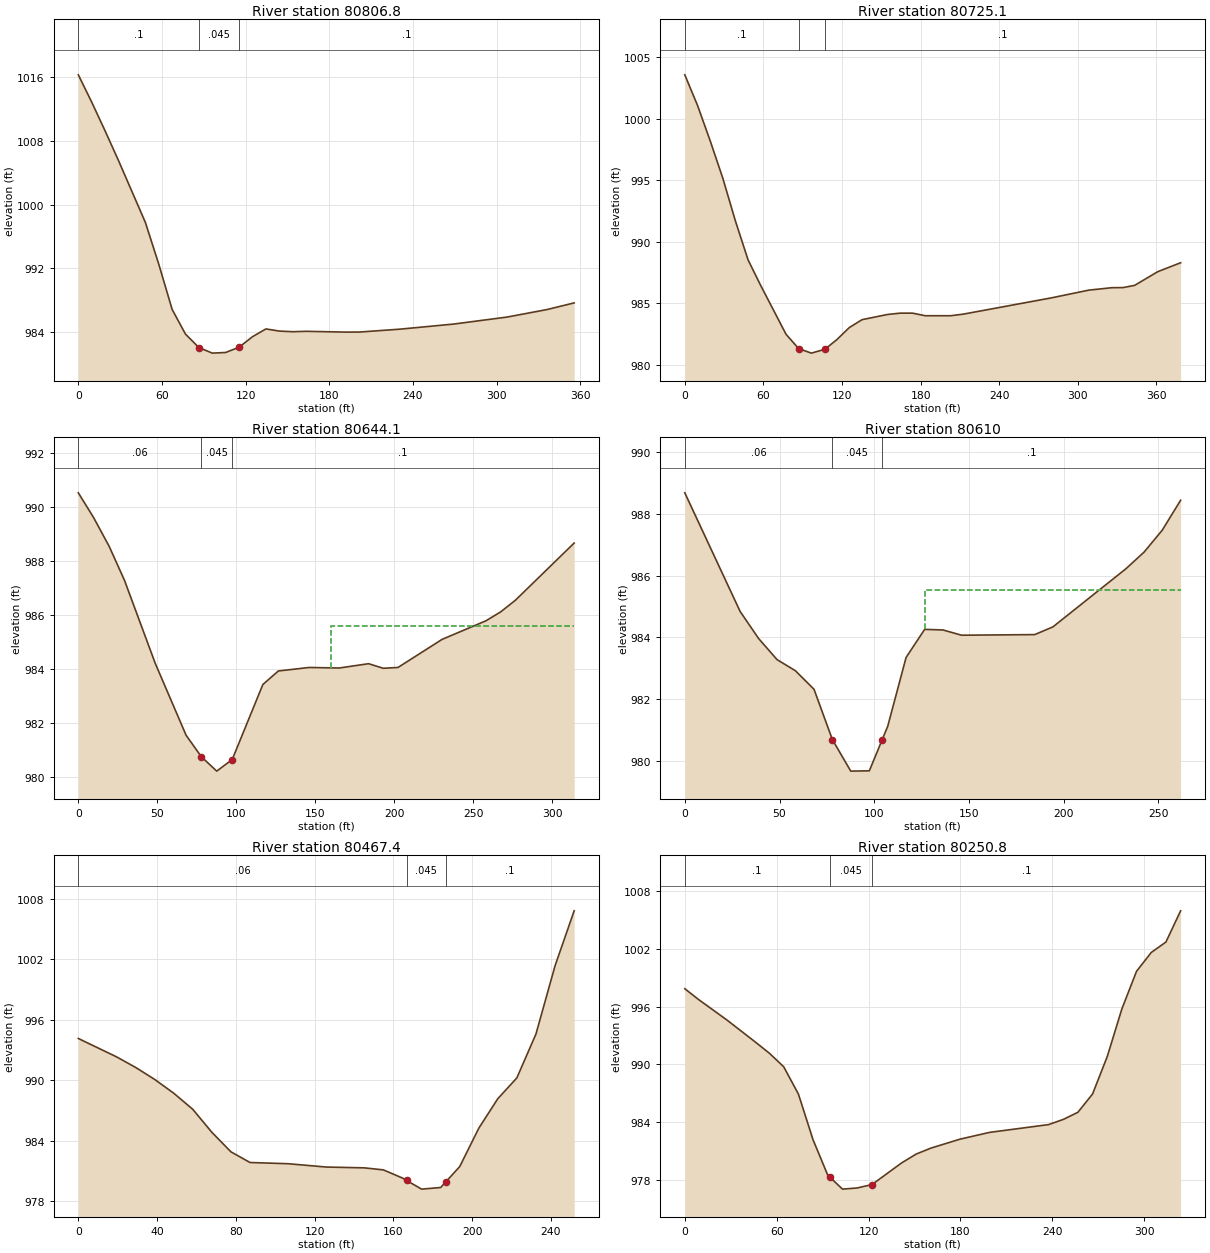
Type RM Length L Ch R = 1 ,80806.8 ,84.6,81.7,78.8
XS GIS Cut Line= 2
     1892201.225      513618.064     1892520.166      513775.448
#Sta/Elev= 24
       0 1016.32     9.6 1012.89    19.2 1009.28    28.8 1005.56    48.1  997.78
    57.7  992.54    67.3  986.85    76.9  983.74    86.5  982.06    96.1  981.36
   105.7  981.44   115.4  982.11     125  983.43   134.6   984.4   144.2  984.13
   153.8  984.05   163.4   984.1   192.2     984   201.9  984.01   230.7  984.37
   269.2  985.01   307.6  985.89   336.4  986.84   355.7  987.67
#Mann= 3 , 0 , 0
       0      .1       0    86.5    .045       0   115.4      .1       0
Bank Sta=86.5,115.4
XS Rating Curve= 0 ,0
Exp/Cntr=0.3,0.1

Type RM Length L Ch R = 1 ,80725.1 ,84.7,81,77.3
XS GIS Cut Line= 3
     1892168.423      513706.609     1892451.757      513803.832
     1892518.423      513846.193
#Sta/Elev= 27
       0 1003.59     9.7 1001.11    19.3  998.25      29  995.19    38.6  991.72
    48.3  988.54      58  986.45    77.3  982.49    86.9981.3321    96.6  980.96
   106.9981.2713     116  982.05   125.6  983.04   135.3  983.68   154.6   984.1
   164.3  984.21   173.9  984.21   183.6     984   202.9     984   212.6  984.13
   280.2  985.46   308.3  986.08   325.9  986.28   334.6  986.29   343.4  986.47
     361  987.58   378.5  988.31
#Mann= 3 , 0 , 0
       0      .1       0    86.9    .045       0   106.9      .1       0
Bank Sta=86.9,106.9
XS Rating Curve= 0 ,0
Exp/Cntr=0.3,0.1

Type RM Length L Ch R = 1 ,80644.1 ,34.1,34.1,34.1
XS GIS Cut Line= 3
     1892153.405      513801.152      1892306.97      513827.474
     1892455.202      513882.102
#Sta/Elev= 21
       0  990.52     9.7   989.6    19.5  988.54    29.2  987.28    48.7   984.2
    68.2  981.54    77.9  980.74    87.6  980.21    97.4  980.64   116.8  983.42
   126.6  983.92   146.1  984.05   165.1  984.03   183.7  984.19     193  984.02
   202.3  984.05   230.2  985.09     258  985.78   267.3  986.11   276.6  986.54
   313.8  988.66
#Mann= 3 , 0 , 0
       0     .06       0    77.9    .045       0    97.4      .1       0
#XS Ineff= 2 , 0
                          160.13           985.6
Permanent Ineff=
       F       F
Bank Sta=77.9,97.4
XS Rating Curve= 0 ,0
Exp/Cntr=0.3,0.1

Type RM Length L Ch R = 1 ,80610   ,124.1,142.5,161
XS GIS Cut Line= 3
     1892146.191      513834.419     1892299.756      513860.741
     1892399.005      513897.544
#Sta/Elev= 21
       0  988.68    29.2  984.84      39  983.96    48.7  983.28    58.4  982.92
    68.2  982.32    77.9  980.69    87.6  979.67    97.4  979.68   104.2980.6904
   107.1  981.12   116.8  983.35   126.6  984.26   136.3  984.24   146.1  984.07
   184.7  984.09   194.3  984.34   232.8  986.22   242.4  986.76     252  987.47
   261.7  988.44
#Mann= 3 , 0 , 0
       0     .06       0    77.9    .045       0   104.2      .1       0
#XS Ineff= 2 , 0
                          126.84          985.54
Permanent Ineff=
       F       F
Bank Sta=77.9,104.2
XS Rating Curve= 0 ,0
Exp/Cntr=0.3,0.1

Type RM Length L Ch R = 1 ,80467.4 ,204.6,216.6,227.9
XS GIS Cut Line= 2
     1892086.082      513828.152     1892224.376      514038.539
#Sta/Elev= 25
       0  994.12    19.4   992.3      29  991.26    38.7  990.07    48.4   988.7
    58.1   987.1    67.8  984.82    77.5  982.88    87.2  981.82   106.5   981.7
   125.9  981.37   145.2  981.29   154.9  981.09   164.6  980.28   166.7980.0426
   174.3  979.18     184  979.34   186.7979.9169   193.7  981.42   203.4  985.23
     213  988.14   222.7  990.21   232.4  994.56   242.1 1001.33   251.8 1006.78
#Mann= 3 , 0 , 0
       0     .06       0   166.7    .045       0   186.7      .1       0
Bank Sta=166.7,186.7
XS Rating Curve= 0 ,0
Exp/Cntr=0.3,0.1

Type RM Length L Ch R = 1 ,80250.8 ,263.4,236.4,209.7
XS GIS Cut Line= 4
     1891945.919      513886.518      1891964.79      513948.314
     1891978.198      514130.361     1892021.613      514193.462
#Sta/Elev= 28
       0  997.87     9.2  996.72    27.7  994.59    46.2   992.3    55.4  991.13
    64.6  989.74    74.2   986.9    83.8  982.12    93.4  978.44    94.5 978.275
     103     977   112.6  977.12   122.3  977.48   141.5  979.72   151.1  980.65
   160.7  981.27   179.9  982.21   199.1  982.91   237.6  983.72   247.2  984.26
   256.7     985   266.3  986.91   275.9  990.81   285.4  995.75     295  999.68
   304.6 1001.64   314.2 1002.73   323.8 1005.98
#Mann= 3 , 0 , 0
       0      .1       0    94.5    .045       0   122.3      .1       0
Bank Sta=94.5,122.3
XS Rating Curve= 0 ,0
Exp/Cntr=0.3,0.1

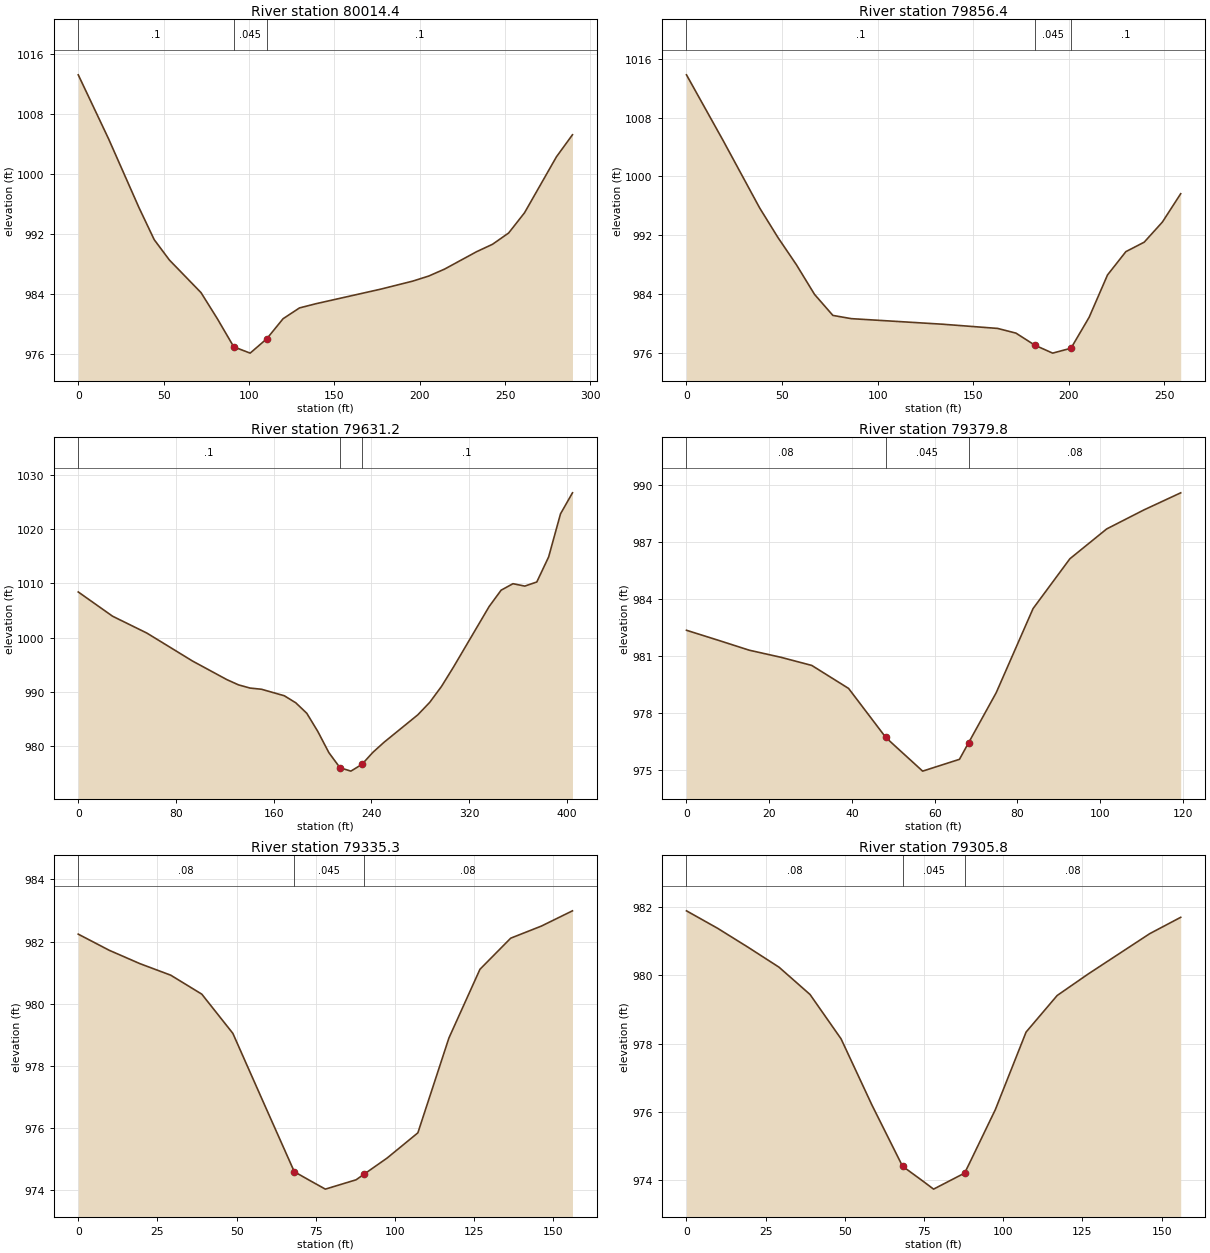
Type RM Length L Ch R = 1 ,80014.4 ,144.1,158,171.4
XS GIS Cut Line= 4
     1891709.635      514057.923     1891753.493      514102.087
      1891844.89      514132.144     1891922.626      514237.646
#Sta/Elev= 23
       0 1013.24    17.8 1004.67    35.6  995.48    44.5  991.21    53.4  988.49
    71.9  984.14    81.5  980.64    91.1  976.89   100.7  976.05   110.4  977.96
     120  980.65   129.6  982.09   139.2  982.65   177.2   984.6   195.9  985.67
   205.3  986.35   214.6  987.28   233.3   989.6   242.7   990.6   252.1   992.1
   261.4   994.8   280.1 1002.28   289.5 1005.23
#Mann= 3 , 0 , 0
       0      .1       0    91.1    .045       0   110.4      .1       0
Bank Sta=91.1,110.4
XS Rating Curve= 0 ,0
Exp/Cntr=0.3,0.1

Type RM Length L Ch R = 1 ,79856.4 ,244.2,225.2,204.7
XS GIS Cut Line= 2
     1891636.011      514111.455     1891792.955      514317.011
#Sta/Elev= 20
       0 1013.81    19.2 1004.86    38.3   995.7    47.9  991.67    57.5  987.99
      67  983.95    76.6  981.09    86.2  980.65   134.1  979.89   162.8  979.32
   172.4  978.68   182.3977.0357   191.6  975.96   201.2  976.63   210.7  980.84
   220.3  986.59   229.9  989.76   239.5  991.05     249  993.78   258.6  997.64
#Mann= 3 , 0 , 0
       0      .1       0   182.3    .045       0   201.2      .1       0
Bank Sta=182.3,201.2
XS Rating Curve= 0 ,0
Exp/Cntr=0.3,0.1

Type RM Length L Ch R = 1 ,79631.2 ,230.1,251.4,272.5
XS GIS Cut Line= 4
     1891422.318      514239.391     1891542.525      514370.791
     1891632.558      514376.631     1891728.432      514473.478
#Sta/Elev= 30
       0 1008.43    28.1 1003.96    56.2 1000.85    93.7  995.68   121.8  992.26
   131.2  991.31   140.6  990.72     150   990.5   168.7   989.3   178.1     988
   187.1  986.07   196.1  982.73   205.2  978.81   214.3976.0331   223.2  975.41
   232.2  976.65   241.2  978.87   250.3  980.72     278  985.79   287.8   988.1
   297.5  991.06   307.2  994.59   336.4 1005.75   346.2 1008.76   355.9 1009.95
   365.6 1009.51   375.4 1010.27   385.1 1014.89   394.8 1022.82   404.6  1026.7
#Mann= 3 , 0 , 0
       0      .1       0   214.3    .045       0   232.2      .1       0
Bank Sta=214.3,232.2
XS Rating Curve= 0 ,0
Exp/Cntr=0.3,0.1

Type RM Length L Ch R = 1 ,79379.8 ,27.1,44.5,59.2
XS GIS Cut Line= 3
     1891445.208      514529.272     1891448.589      514559.416
     1891496.824       514634.39
#Sta/Elev= 18
       0  982.34     7.6  981.82    15.2  981.29    22.8  980.92    30.3  980.49
    39.2  979.28    48.2   976.7    50.7   976.2    57.1  974.93    65.7  975.53
      66  975.55    68.2976.4177    74.9  979.06    83.8  983.48    92.7   986.1
   101.6  987.67   110.6  988.67   119.5  989.57
#Mann= 3 , 0 , 0
       0     .08       0    48.2    .045       0    68.2     .08       0
Bank Sta=48.2,68.2
XS Rating Curve= 0 ,0
Exp/Cntr=0.3,0.1

Type RM Length L Ch R = 1 ,79335.3 ,32.2,29.4,29.3
XS GIS Cut Line= 2
     1891433.307       514528.95      1891422.49      514684.576
#Sta/Elev= 19
       0  982.24     9.8  981.72    19.5  981.29    29.2  980.92      39  980.31
    48.8  979.05    58.5  976.82    68.2   974.6    72.7  974.34      78  974.04
    87.7  974.34    90.2974.5186    97.5  975.04   107.2  975.85     117   978.9
   126.8  981.11   136.5  982.11   146.2   982.5     156  982.99
#Mann= 3 , 0 , 0
       0     .08       0    68.2    .045       0    90.2     .08       0
Bank Sta=68.2,90.2
XS Rating Curve= 0 ,0
Exp/Cntr=0.3,0.1

Type RM Length L Ch R = 1 ,79305.8 ,121.9,120.6,118.3
XS GIS Cut Line= 2
     1891404.552       514531.79     1891393.735      514687.416
#Sta/Elev= 19
       0  981.89     9.8  981.38    19.5  980.82    29.2  980.24      39  979.44
    48.8  978.14    58.5  976.21    68.2  974.41    74.7  973.97      78  973.74
    87.8  974.21    89.7  974.57    97.5  976.07   107.2  978.34     117  979.41
   126.8  980.04   136.5  980.63   146.2  981.22     156   981.7
#Mann= 3 , 0 , 0
       0     .08       0    68.2    .045       0    87.8     .08       0
Bank Sta=68.2,87.8
XS Rating Curve= 0 ,0
Exp/Cntr=0.3,0.1

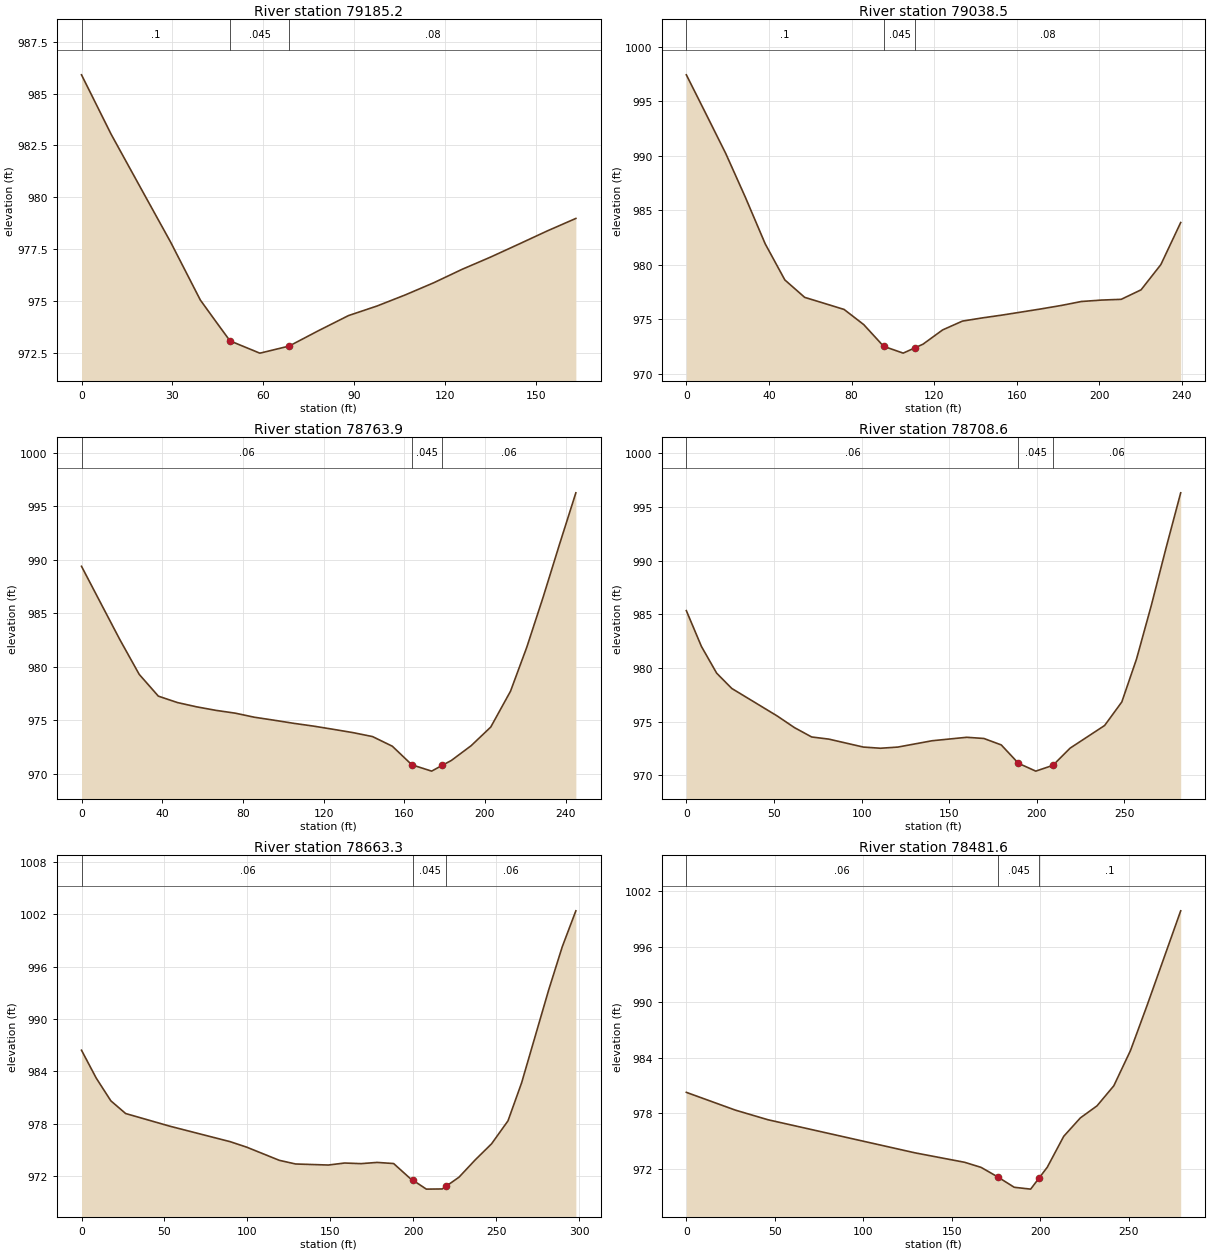
Type RM Length L Ch R = 1 ,79185.2 ,152.9,146.7,140.8
XS GIS Cut Line= 3
     1891283.182       514529.32     1891283.289      514617.441
     1891306.796      514688.625
#Sta/Elev= 20
       0   985.9     9.8  983.03    19.6  980.43    29.4  977.84    39.2  975.05
    44.2  974.04      49  973.08    58.8  972.49    59.2   972.5    68.5  972.83
    78.3  973.58    88.1   974.3    97.5  974.76   106.9   975.3   116.2  975.88
   125.6  976.53     135  977.12   144.4  977.75   153.7  978.38   163.1  978.98
#Mann= 3 , 0 , 0
       0      .1       0      49    .045       0    68.5     .08       0
Bank Sta=49,68.5
XS Rating Curve= 0 ,0
Exp/Cntr=0.3,0.1

Type RM Length L Ch R = 1 ,79038.5 ,278.9,274.6,270.4
XS GIS Cut Line= 3
     1891126.178      514529.867     1891165.019      514667.724
     1891169.296      514763.833
#Sta/Elev= 29
       0  997.44     9.6  993.82    19.1  990.21    28.6  986.19    38.2  981.92
    47.7  978.61    57.3  977.01    66.8  976.46    76.4   975.9    85.9  974.51
    93.4  972.96    95.5  972.52     105  971.89   108.4  972.18   110.9972.3937
   114.6  972.71   124.1  974.02   133.7  974.83   143.2  975.12   152.8  975.38
   162.5  975.67   172.1  975.96   181.7  976.27   191.3  976.63     201  976.76
   210.6  976.83   220.2   977.7   229.8  980.02   239.4  983.88
#Mann= 3 , 0 , 0
       0      .1       0    95.5    .045       0   110.9     .08       0
Bank Sta=95.5,110.9
XS Rating Curve= 0 ,0
Exp/Cntr=0.3,0.1

Type RM Length L Ch R = 1 ,78763.9 ,62.6,55.2,41.9
XS GIS Cut Line= 4
     1890846.818      514560.013     1890864.527      514643.867
     1890918.172      514758.971     1890920.777      514791.263
#Sta/Elev= 30
       0  989.38     9.5  985.95      19  982.53    28.6  979.28    38.1  977.24
    47.6  976.64    57.1  976.24    66.7  975.91    76.2  975.65    85.7  975.27
    95.5  974.99   105.2   974.7     115  974.44   124.8  974.14   134.6  973.83
   144.3  973.46   154.1  972.56   161.4  971.25   163.8  970.82   173.6  970.23
   176.4  970.52   178.9970.7736   183.4  971.23   193.2  972.61   202.9  974.35
   212.7   977.7   220.8  981.83   228.9  986.51     237  991.44   245.1  996.25
#Mann= 3 , 0 , 0
       0     .06       0   163.8    .045       0   178.9     .06       0
Bank Sta=163.8,178.9
XS Rating Curve= 0 ,0
Exp/Cntr=0.3,0.1

Type RM Length L Ch R = 1 ,78708.6 ,46.1,45.4,48.5
XS GIS Cut Line= 4
     1890737.977      514574.488     1890742.828       514626.08
      1890885.59      514761.421     1890892.544      514794.208
#Sta/Elev= 25
       0  985.34     8.6  982.01    17.3  979.52    25.9   978.1    51.8  975.54
    61.7  974.45    71.5  973.58    81.3  973.38     101  972.64   110.8  972.53
   120.7  972.64   140.3  973.23     160  973.55   169.8  973.44   179.7  972.84
   189.5  971.13   199.4   970.4   209.2  970.94     219  972.54   238.7  974.65
   248.5  976.84   256.9  980.84   265.3  985.81   273.7  991.15   282.1  996.31
#Mann= 3 , 0 , 0
       0     .06       0   189.5    .045       0   209.2     .06       0
Bank Sta=189.5,209.2
XS Rating Curve= 0 ,0
Exp/Cntr=0.3,0.1

Type RM Length L Ch R = 1 ,78663.3 ,170.6,181.7,191
XS GIS Cut Line= 4
     1890701.518      514571.449     1890709.745       514650.85
     1890838.266       514772.78     1890845.551      514813.006
#Sta/Elev= 27
       0  986.41     8.9  983.21    17.7  980.61    26.6  979.16    53.2  977.71
    89.7  975.93    99.5  975.31   119.2   973.8     129  973.38   148.7  973.26
   158.6  973.49   168.4  973.42   178.2  973.56   188.1  973.43   197.9  971.75
   199.9971.4967   207.8   970.5   217.4  970.52   219.9970.8542   227.5  971.87
   237.3  973.86   247.1  975.69     257  978.32   265.2  982.67   281.5   993.3
   289.7  998.26   297.9 1002.38
#Mann= 3 , 0 , 0
       0     .06       0   199.9    .045       0   219.9     .06       0
Bank Sta=199.9,219.9
XS Rating Curve= 0 ,0
Exp/Cntr=0.3,0.1

Type RM Length L Ch R = 1 ,78481.6 ,191.8,189.3,186.7
XS GIS Cut Line= 4
     1890567.838      514620.928     1890606.032      514734.644
     1890645.963      514829.262     1890675.911      514877.439
#Sta/Elev= 18
       0  980.26    27.7  978.34    46.1   977.3   129.3  973.72   157.3   972.7
   166.6  972.15     176  971.12   185.3     970   194.6   969.8  199.57 971.053
     204  972.17   213.3  975.51   222.7   977.5   232.1   978.8   241.6  980.97
     251  984.77   260.5  989.71   279.4  999.88
#Mann= 3 , 0 , 0
       0     .06       0     176    .045       0  199.57      .1       0
Bank Sta=176,199.57
XS Rating Curve= 0 ,0
Exp/Cntr=0.3,0.1

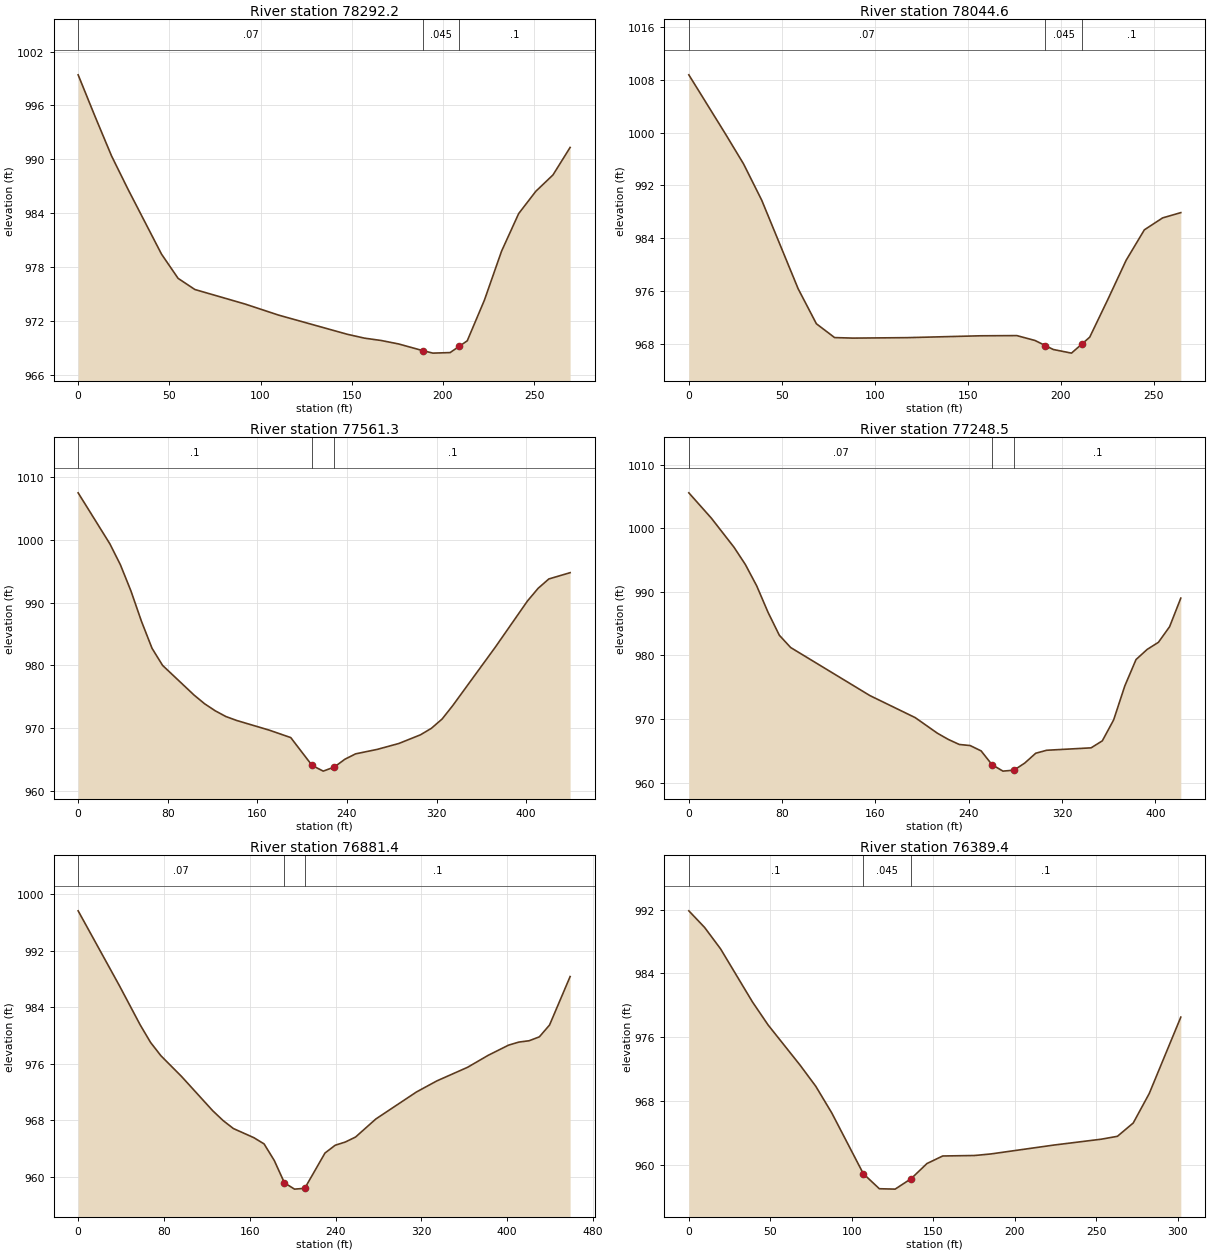
Type RM Length L Ch R = 1 ,78292.2 ,251.6,247.6,243.6
XS GIS Cut Line= 3
      1890357.11      514723.804     1890419.981      514802.216
     1890502.631      514949.856
#Sta/Elev= 24
       0  999.41     9.1  994.86    18.3  990.39    27.4  986.65    45.7  979.46
    54.8  976.76      64  975.52    91.4  973.91   109.9  972.67   147.5  970.54
   156.9  970.11   166.3  969.84   175.7  969.46   188.8 968.725   194.5  968.44
   203.9   968.5   208.8  969.18   213.3  969.81   222.7  974.33   232.1  979.78
   241.5  983.97   250.9  986.45   260.3  988.27   269.7  991.33
#Mann= 3 , 0 , 0
       0     .07       0   188.8    .045       0   208.8      .1       0
Bank Sta=188.8,208.8
XS Rating Curve= 0 ,0
Exp/Cntr=0.3,0.1

Type RM Length L Ch R = 1 ,78044.6 ,497.9,483.3,468.9
XS GIS Cut Line= 2
     1890170.033       514889.28     1890335.605      515095.625
#Sta/Elev= 22
       0 1008.72    19.6  999.83    29.4  995.27    39.2  989.77    58.8  976.38
    68.6  971.09    78.4     969    88.2  968.92   117.6  968.99   156.8  969.27
   176.4   969.3   186.2  968.56   191.7967.7969     196   967.2   205.8  966.65
   211.7968.1033   215.6  969.06   225.4  974.79   235.2  980.69     245  985.29
   254.8  987.09   264.6  987.89
#Mann= 3 , 0 , 0
       0     .07       0   191.7    .045       0   211.7      .1       0
Bank Sta=191.7,211.7
XS Rating Curve= 0 ,0
Exp/Cntr=0.3,0.1

Type RM Length L Ch R = 1 ,77561.3 ,302.4,312.8,323.1
XS GIS Cut Line= 4
     1889795.414      515085.955     1889814.164      515216.511
     1890000.969      515265.122     1890071.108        515355.4
#Sta/Elev= 30
       0 1007.48    28.3  999.37    37.7  996.04    47.1  991.88    56.5  987.04
      66  982.72    75.4  980.01   103.6  975.27     113  973.89   122.5  972.77
   131.9  971.87   141.6  971.24   170.5  969.71   189.8  968.52   208.8964.0918
   218.8  963.18   228.8963.8428   238.1  965.07   247.7  965.93     267  966.64
   286.3  967.58   305.6  968.96   315.3  969.99   324.9  971.47   334.4  973.61
   372.6  982.96   401.1  990.26   410.7  992.29   420.2  993.77   439.2  994.77
#Mann= 3 , 0 , 0
       0      .1       0   208.8    .045       0   228.8      .1       0
Bank Sta=208.8,228.8
XS Rating Curve= 0 ,0
Exp/Cntr=0.3,0.1

Type RM Length L Ch R = 1 ,77248.5 ,358.8,367.1,374.8
XS GIS Cut Line= 4
     1889522.358        515252.2     1889649.556      515411.403
     1889734.901      515484.439     1889797.269      515569.784
#Sta/Elev= 30
       0 1005.57    19.4 1001.57    38.8     997    48.5  994.29    58.2  990.94
    67.9  986.79    77.6  983.18    87.3  981.25   155.3  973.69   194.1  970.23
   213.1  967.78   222.5   966.8   231.9  966.01   241.2  965.84   250.6     965
   259.9  962.84   269.3  961.82   278.8961.9722     288  963.09   297.4  964.63
   306.8   965.1   344.9  965.48   354.5  966.58   364.2  969.87   373.8  975.22
   383.4  979.36     393  980.96   402.6  982.07   412.2  984.53   421.8  989.02
#Mann= 3 , 0 , 0
       0     .07       0   259.9    .045       0   278.8      .1       0
Bank Sta=259.9,278.8
XS Rating Curve= 0 ,0
Exp/Cntr=0.3,0.1

Type RM Length L Ch R = 1 ,76881.4 ,501.8,492,482.2
XS GIS Cut Line= 4
     1889260.312      515558.157     1889406.561      515607.881
     1889484.365      515748.865     1889573.284      515861.184
#Sta/Elev= 30
       0  997.63    38.6  987.02    57.9   981.5    67.6  979.02    77.2  977.15
    96.5  974.21   125.5  969.38   135.2  967.99   144.8  966.86   163.9  965.57
   173.4  964.69   182.9  962.35   192.4959.1813   201.8   958.3   211.3  958.41
   230.2   963.4   239.7   964.5   249.2  964.96   258.7  965.66   277.6  968.21
   315.5  972.03   334.6   973.6   363.2  975.52   382.4  977.21   401.4  978.65
     411  979.08   420.6  979.27   430.1  979.82   439.6  981.49   458.8  988.34
#Mann= 3 , 0 , 0
       0     .07       0   192.4    .045       0   211.3      .1       0
Bank Sta=192.4,211.3
XS Rating Curve= 0 ,0
Exp/Cntr=0.3,0.1

Type RM Length L Ch R = 1 ,76389.4 ,98.7,97.8,96.7
XS GIS Cut Line= 2
     1889065.918      515964.559     1889309.841       516142.51
#Sta/Elev= 22
       0  991.84     9.7  989.75    19.5  987.06      39  980.42    48.7   977.5
    68.2  972.49    77.9  969.82    87.7  966.48   107.1  958.84   116.9  956.96
   126.6  956.91   136.4  958.22   146.1  960.12   155.8  961.07   175.3  961.13
   185.1  961.32     224  962.44   253.2  963.18     263  963.54   272.7  965.21
   282.5   968.9   301.9   978.5
#Mann= 3 , 0 , 0
       0      .1       0   107.1    .045       0   136.4      .1       0
Bank Sta=107.1,136.4
XS Rating Curve= 0 ,0
Exp/Cntr=0.3,0.1

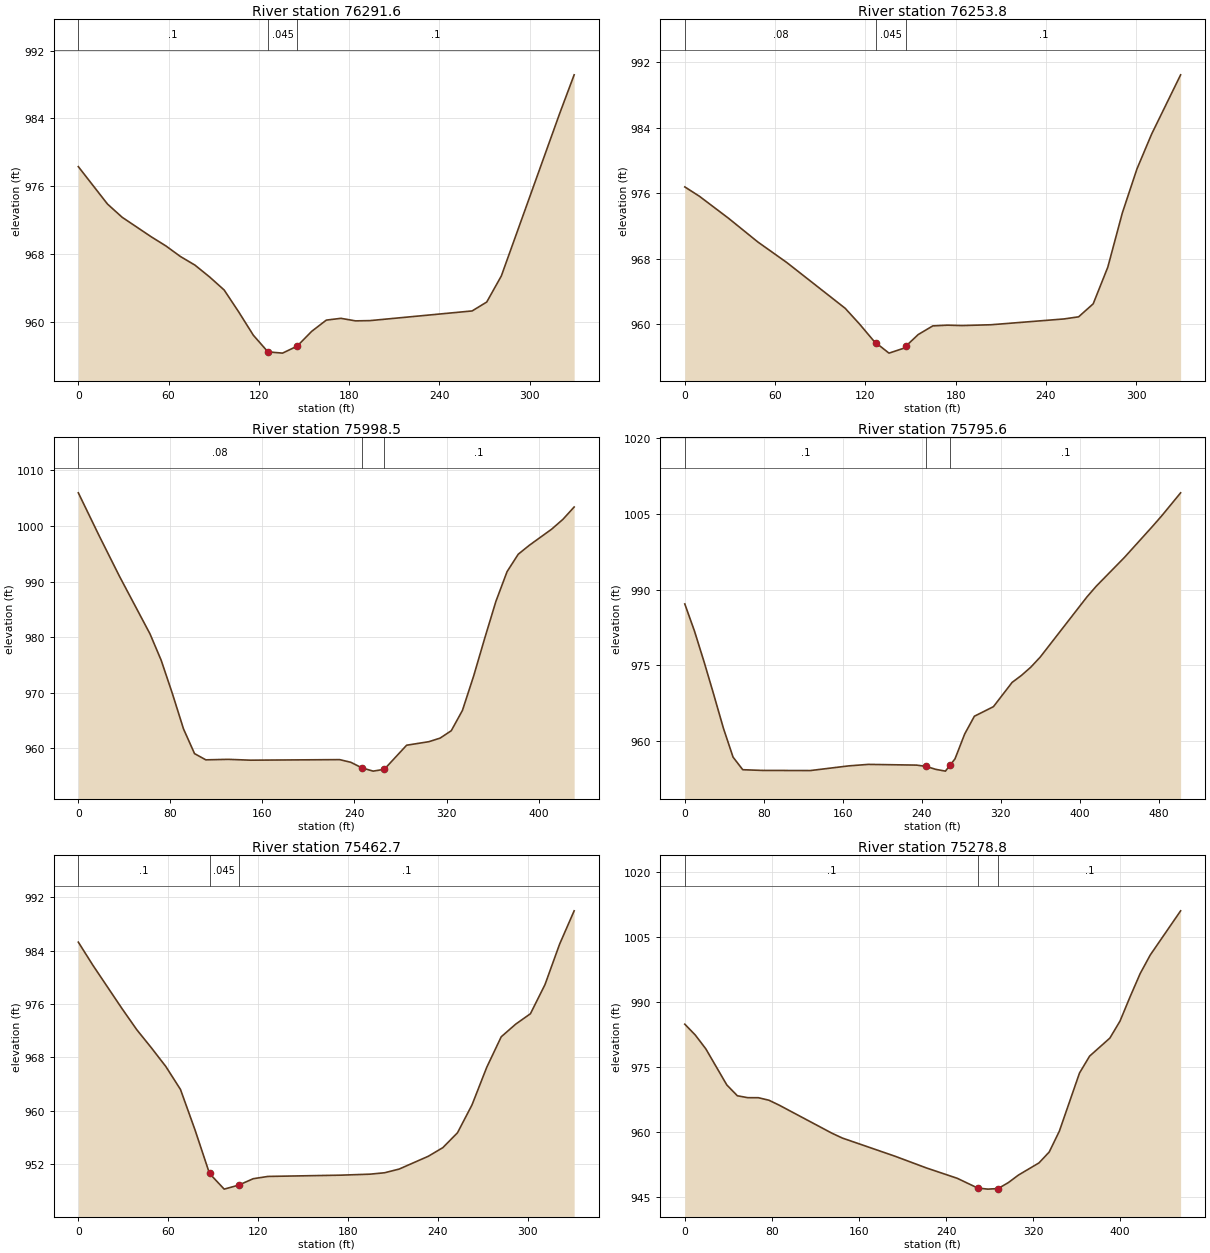
Type RM Length L Ch R = 1 ,76291.6 ,37.7,37.8,37.7
XS GIS Cut Line= 2
     1888999.553      516044.359     1889274.075       516226.65
#Sta/Elev= 24
       0  978.32    19.4  973.91    29.1  972.36    48.5  970.05    58.2  968.98
    67.8  967.74    77.5  966.72    87.2  965.33    96.9  963.79   106.6   961.2
   116.3  958.46     126   956.5   135.7  956.35   145.4  957.17   155.1  958.92
   164.8  960.24   174.5  960.45   184.2  960.15   193.8  960.18   261.7  961.32
   271.4  962.37   281.1  965.44   319.8  984.55   329.5  989.14
#Mann= 3 , 0 , 0
       0      .1       0     126    .045       0   145.4      .1       0
Bank Sta=126,145.4
XS Rating Curve= 0 ,0
Exp/Cntr=0.3,0.1

Type RM Length L Ch R = 1 ,76253.8 ,267.7,255.3,241.2
XS GIS Cut Line= 2
     1888978.532      516075.684     1889253.054      516257.976
#Sta/Elev= 25
       0  976.77     9.7  975.63    29.1  972.93    48.5  970.04    67.8  967.52
   106.6  961.92   116.3  959.96     126  957.84   127.1957.6812   135.7  956.44
   145.4  957.03   147.1957.3245   155.1  958.71   164.8  959.77   174.5  959.86
   184.2  959.81   203.5  959.91     252  960.62   261.7  960.88   271.4  962.47
   281.1  966.95   290.8  973.61   300.5  978.98   310.2  983.22   329.5  990.48
#Mann= 3 , 0 , 0
       0     .08       0   127.1    .045       0   147.1      .1       0
Bank Sta=127.1,147.1
XS Rating Curve= 0 ,0
Exp/Cntr=0.3,0.1

Type RM Length L Ch R = 1 ,75998.5 ,198.4,202.8,206.8
XS GIS Cut Line= 4
     1888807.365      516381.974     1888868.789      516392.135
     1889179.144      516392.597     1889237.335      516395.368
#Sta/Elev= 30
       0 1005.96    17.8  998.36    35.6     991    62.3  980.57      72  975.83
    81.7  969.86    91.4  963.48     101  959.03   110.8  957.91   130.2     958
   149.6  957.85   227.1  957.95   236.8  957.47   246.5  956.46   256.2  955.88
   265.9  956.21   285.3  960.54   304.7  961.18   314.4  961.82   324.1  963.15
   333.8   966.8   343.5  972.96   353.2  979.81   362.9  986.43   372.6  991.78
   382.3  994.91     392  996.53   411.4  999.43   421.2  1001.2   430.9 1003.41
#Mann= 3 , 0 , 0
       0     .08       0   246.5    .045       0   265.9      .1       0
Bank Sta=246.5,265.9
XS Rating Curve= 0 ,0
Exp/Cntr=0.3,0.1

Type RM Length L Ch R = 1 ,75795.6 ,325.7,332.9,339.9
XS GIS Cut Line= 3
     1888810.874      516543.092     1889108.548      516600.046
     1889304.366      516563.969
#Sta/Elev= 30
       0  987.15     9.8   981.8    19.6  975.67    29.3  969.27    39.1  962.61
    48.9  956.89    58.7  954.41    78.2  954.27   127.1  954.24   166.2  955.17
   185.8  955.46   234.6  955.32   244.4  955.07   254.2  954.48     264  954.13
   268.6955.2825   273.7  956.56   283.5  961.47   293.3  964.97   312.6  966.86
   331.5  971.65     341  973.04   350.5  974.67     360  976.66   407.4  988.56
   416.8  990.67   445.3  996.34   473.7 1002.47   483.2 1004.59   502.2  1009.1
#Mann= 3 , 0 , 0
       0      .1       0   244.4    .045       0   268.6      .1       0
Bank Sta=244.4,268.6
XS Rating Curve= 0 ,0
Exp/Cntr=0.3,0.1

Type RM Length L Ch R = 1 ,75462.7 ,191.7,183.9,174.8
XS GIS Cut Line= 2
     1888721.203      516703.576     1889010.664       516864.29
#Sta/Elev= 28
       0  985.27     9.7  981.82    29.2  975.31      39  972.17    48.7  969.47
    58.4  966.66    68.2  963.22    77.9  957.17    87.6  950.63    97.4  948.29
   107.1  948.89   116.8  949.85   126.6  950.19   175.3  950.38   194.8  950.53
   204.5  950.74   214.2  951.29   233.7  953.21   243.4   954.5   253.2  956.73
   262.9  960.91   272.7  966.52   282.4   971.1   292.1     973   301.9  974.55
   311.6   978.9   321.4  984.98   331.1  989.96
#Mann= 3 , 0 , 0
       0      .1       0    87.6    .045       0   107.1      .1       0
Bank Sta=87.6,107.1
XS Rating Curve= 0 ,0
Exp/Cntr=0.3,0.1

Type RM Length L Ch R = 1 ,75278.8 ,536.3,547.4,558.2
XS GIS Cut Line= 4
     1888589.179      516798.068      1888781.94      516908.413
     1888893.659      516923.065     1888990.269      516995.408
#Sta/Elev= 30
       0  984.89     9.7  982.37    19.3   979.2    38.6  970.86    48.3  968.36
    57.9  967.92    67.6  967.91    77.3  967.33    86.9  966.17   135.2  959.71
   144.8  958.59   193.1   954.4   222.1  951.68   250.3   949.3   269.1  947.05
   278.4   946.8   287.8  946.93   297.2   948.3   306.6  950.06   325.4  952.86
   334.8  955.38   344.1  960.19   362.6  973.61   371.9  977.52   390.5  981.68
   399.8   985.6   409.1  991.23   418.3  996.56   427.6 1000.87   455.5 1011.07
#Mann= 3 , 0 , 0
       0      .1       0   269.1    .045       0   287.8      .1       0
Bank Sta=269.1,287.8
XS Rating Curve= 0 ,0
Exp/Cntr=0.3,0.1

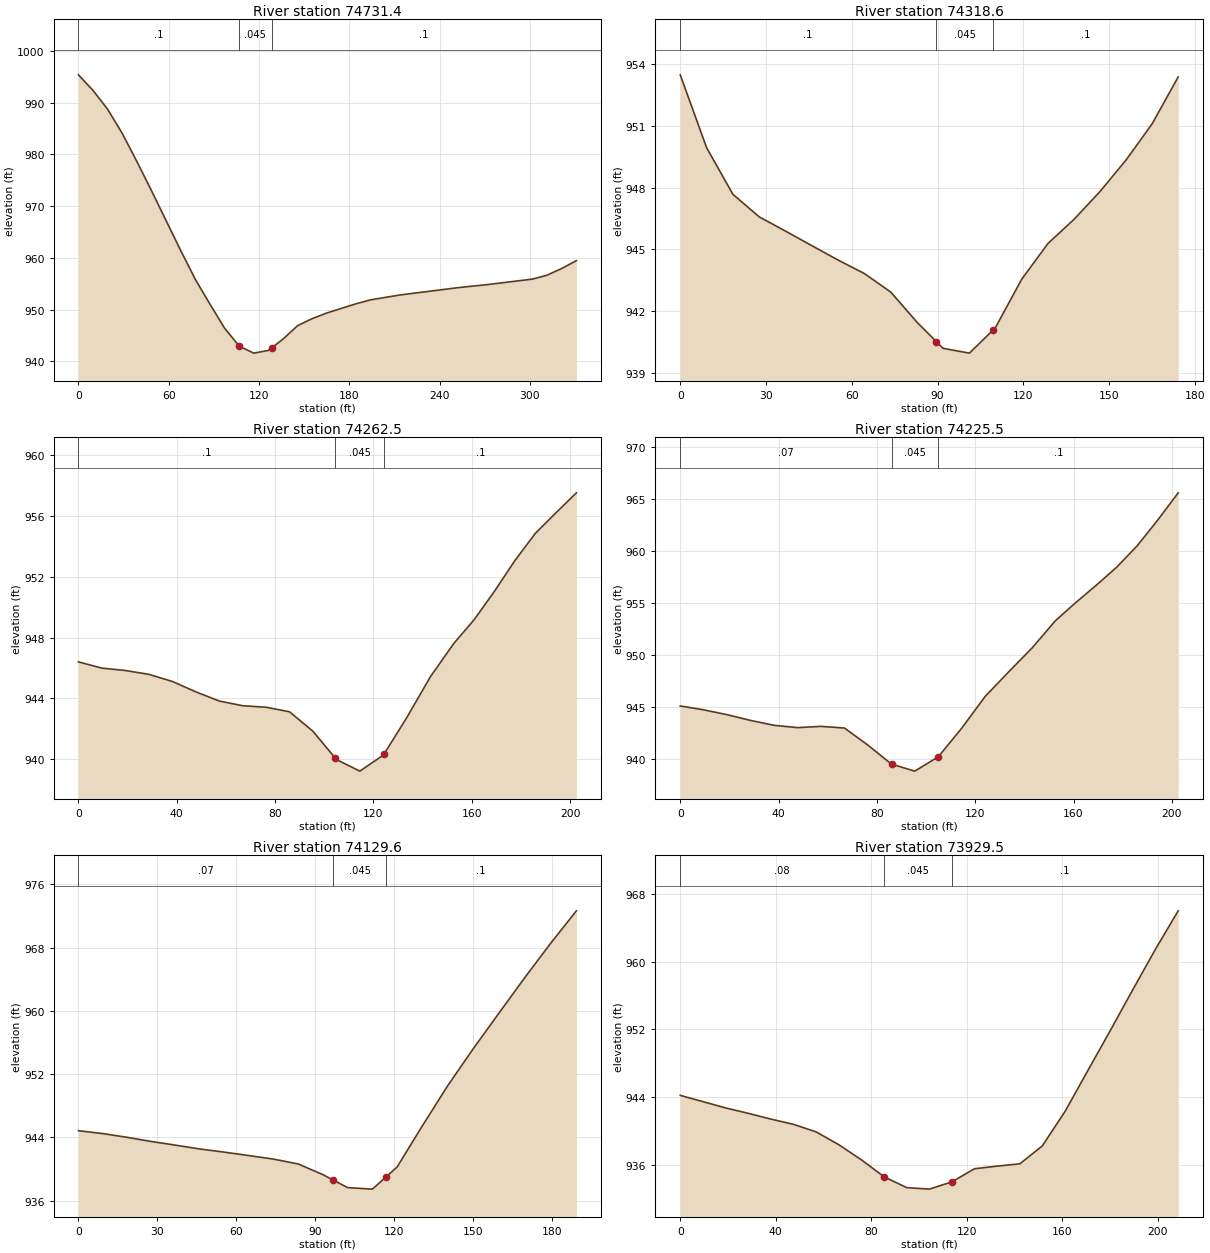
Type RM Length L Ch R = 1 ,74731.4 ,412.2,412.8,413.3
XS GIS Cut Line= 3
     1888392.385       517238.43     1888542.776      517345.201
     1888644.338       517450.67
#Sta/Elev= 27
       0  995.37     9.7  992.36    19.4  988.72    29.1  984.06    38.8  978.64
    48.5  973.01      68  961.39    77.7  955.82    87.4  951.06    97.1  946.42
   106.8  942.95   116.5  941.59   126.2  942.11   128.3 942.582   135.9  944.29
   145.6  946.89   155.3  948.25     165  949.34   184.4  951.12   194.2  951.89
   213.7  952.83   252.8  954.26   272.3  954.85   301.6  955.89   311.3  956.64
   321.1  957.94   330.9  959.46
#Mann= 3 , 0 , 0
       0      .1       0   106.8    .045       0   128.3      .1       0
Bank Sta=106.8,128.3
XS Rating Curve= 0 ,0
Exp/Cntr=0.3,0.1

Type RM Length L Ch R = 1 ,74318.6 ,60.5,56.1,51.5
XS GIS Cut Line= 4
       1888161.8      517556.755     1888195.887      517600.281
     1888261.962      517649.575     1888287.658      517675.271
#Sta/Elev= 24
       0  953.49     9.2  949.95    18.4  947.68    27.6  946.58    36.9  945.88
    46.1  945.17    55.3  944.47    64.4  943.82    73.6  942.92    82.8  941.45
    89.5 940.515    91.9  940.18      92  940.18   101.1  939.95     107  940.75
   109.5941.0938   110.2  941.19   119.4  943.55   128.6  945.29   137.7  946.46
   146.8  947.82   155.9  949.35     165  951.11   174.1  953.39
#Mann= 3 , 0 , 0
       0      .1       0    89.5    .045       0   109.5      .1       0
Bank Sta=89.5,109.5
XS Rating Curve= 0 ,0
Exp/Cntr=0.3,0.1

Type RM Length L Ch R = 1 ,74262.5 ,37,37,37
XS GIS Cut Line= 3
     1888095.385      517622.645     1888233.305      517688.196
     1888283.123       517689.77
#Sta/Elev= 27
       0   946.4     9.5  945.99    19.1  945.83    28.6  945.58    38.2  945.11
    47.7  944.43    57.3  943.82    66.8  943.51    76.4  943.41    85.9  943.11
    95.4  941.83   104.4940.0769     105  939.96   106.9  939.81   114.5   939.2
   121.9  940.02   124.1  940.26   124.4 940.338   133.6  942.73   143.2  945.42
   152.7  947.61     161  949.18   169.3  951.06   177.6  953.08   185.9  954.87
   194.2  956.21   202.6  957.54
#Mann= 3 , 0 , 0
       0      .1       0   104.4    .045       0   124.4      .1       0
Bank Sta=104.4,124.4
XS Rating Curve= 0 ,0
Exp/Cntr=0.3,0.1

Type RM Length L Ch R = 1 ,74225.5 ,81.2,95.9,110.4
XS GIS Cut Line= 3
     1888096.159      517663.944     1888234.079      517729.495
     1888283.897      517731.068
#Sta/Elev= 26
       0  945.12     9.5  944.75    19.1  944.28    28.6  943.73    38.2  943.26
    47.7  943.04    57.3  943.16    66.8     943    76.4  941.35    85.9  939.54
    86.2939.5186    88.7  939.34    95.4  938.86   103.7  940.05     105  940.24
   114.5  942.98   124.1  946.05   133.6  948.39   143.2  950.71   152.7  953.33
     161  955.07   169.3  956.73   177.6  958.46   185.9  960.51   194.2  962.96
   202.6   965.6
#Mann= 3 , 0 , 0
       0     .07       0    86.2    .045       0     105      .1       0
Bank Sta=86.2,105
XS Rating Curve= 0 ,0
Exp/Cntr=0.3,0.1

Type RM Length L Ch R = 1 ,74129.6 ,202.4,200.1,197.5
XS GIS Cut Line= 4
     1888078.337      517673.368     1888104.684      517742.655
     1888131.335      517792.502     1888171.342      517835.535
#Sta/Elev= 25
       0  944.84     9.3  944.47    18.5     944    27.8  943.47    37.1     943
    46.3  942.52    55.6  942.12    64.9  941.69    74.1  941.25    83.6  940.63
      93  939.28    96.9938.5975    99.4  938.16   102.4  937.64   111.8  937.45
   114.4  938.22   116.9938.9626   121.2  940.24   130.6  945.34   140.4   950.5
   150.2  955.22     160  959.73   169.8  964.21   179.6  968.53   189.4  972.64
#Mann= 3 , 0 , 0
       0     .07       0    96.9    .045       0   116.9      .1       0
Bank Sta=96.9,116.9
XS Rating Curve= 0 ,0
Exp/Cntr=0.3,0.1

Type RM Length L Ch R = 1 ,73929.5 ,337.9,338.5,338.2
XS GIS Cut Line= 2
     1887902.042      517801.798     1888020.098      517973.673
#Sta/Elev= 25
       0  944.24     9.5   943.5      19  942.76    28.4  942.13    37.9  941.45
    47.4  940.83    56.9  939.94    66.4  938.43    75.8  936.66    82.9  935.17
    85.3  934.66    94.8  933.38    97.9  933.32   104.3   933.2   113.7  934.05
   123.2   935.6   132.7  935.91   142.2  936.18   151.6  938.29   161.1  942.34
   170.6  947.13   180.1  951.89   189.6  956.74     199  961.46   208.5  965.97
#Mann= 3 , 0 , 0
       0     .08       0    85.3    .045       0   113.7      .1       0
Bank Sta=85.3,113.7
XS Rating Curve= 0 ,0
Exp/Cntr=0.3,0.1