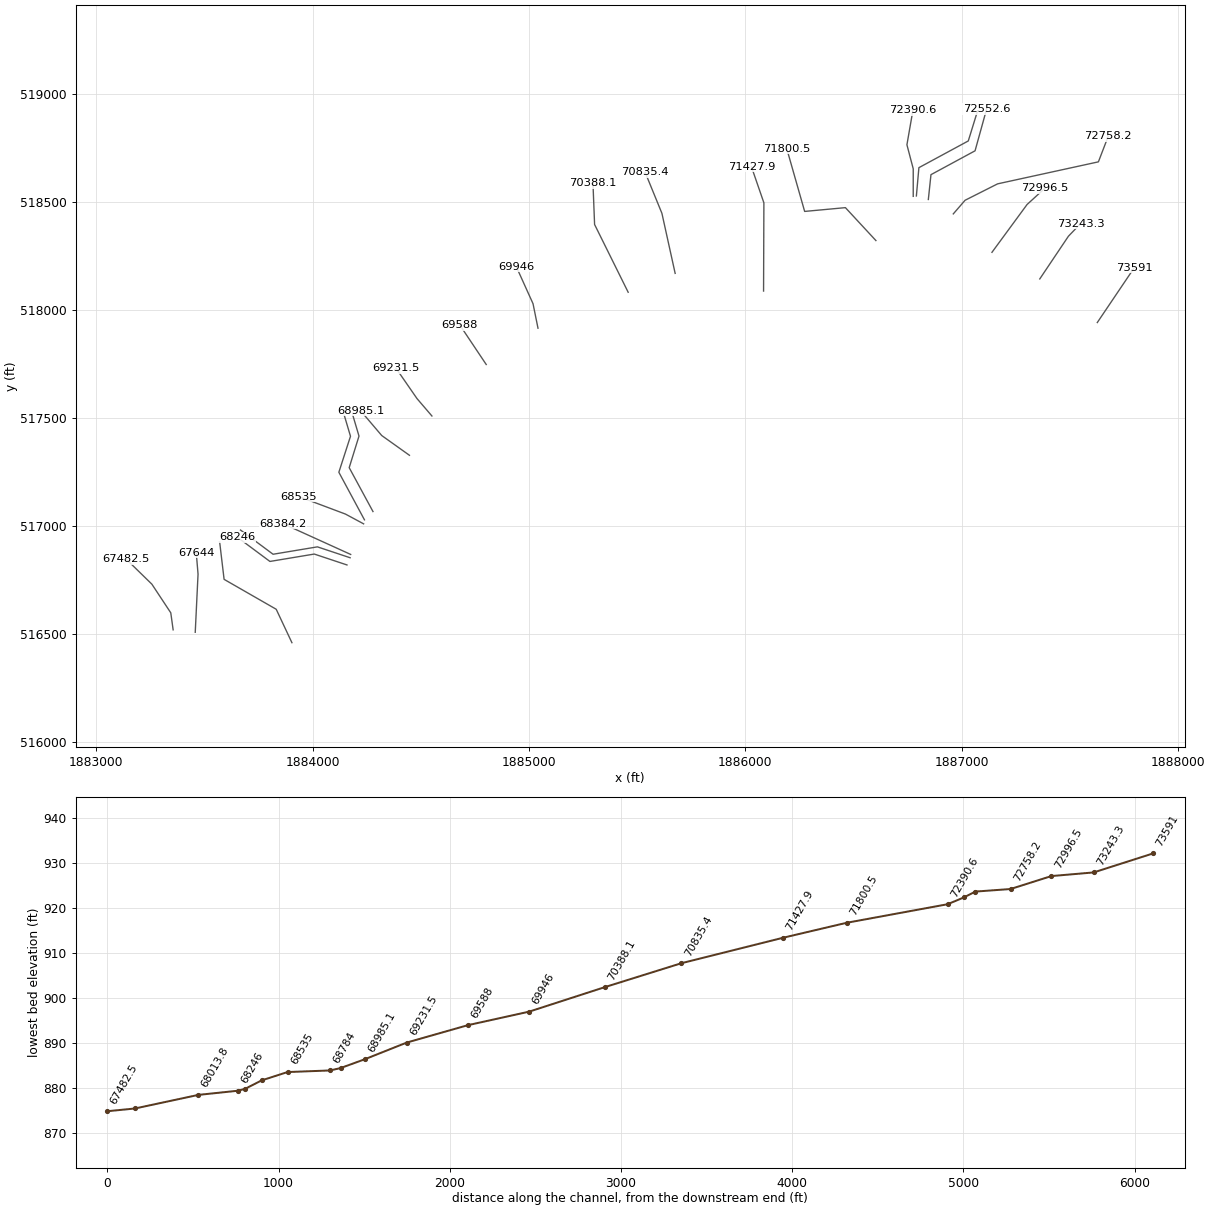
HEC-RAS study FALLINGRCR.prj: FALLINGRCR

--- FALLINGRCR.g01 (geometry) --- (continued)

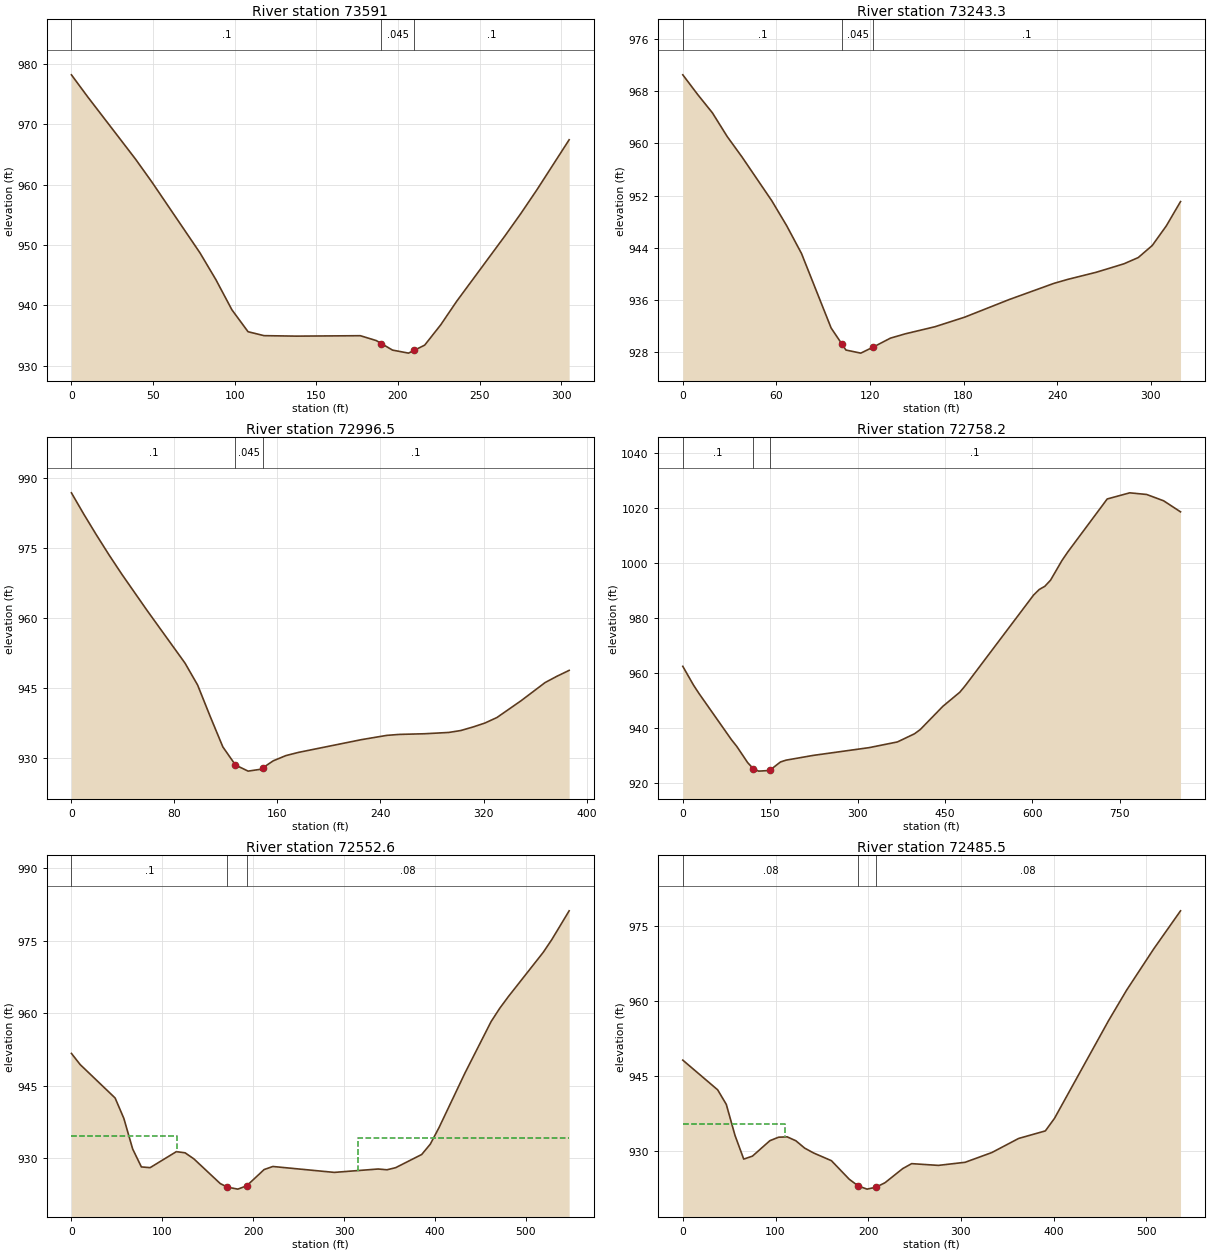
Type RM Length L Ch R = 1 ,73591   ,347.3,347.8,347.4
XS GIS Cut Line= 2
     1887626.521      517942.781     1887796.877      518195.602
#Sta/Elev= 23
       0  978.14     9.8  974.56    39.3  964.19    49.2  960.45    78.7  948.72
    88.5  944.27    98.3  939.29   108.2  935.66     118  935.01   137.7  934.93
     177     935   186.8  934.19   189.9933.6973   196.7  932.62   206.5  932.12
   209.9932.5733   216.4  933.44   226.2  936.79     236  940.69   265.5  951.48
   275.4  955.24   285.2  959.15   304.9   967.4
#Mann= 3 , 0 , 0
       0      .1       0   189.9    .045       0   209.9      .1       0
Bank Sta=189.9,209.9
XS Rating Curve= 0 ,0
Exp/Cntr=0.3,0.1

Type RM Length L Ch R = 1 ,73243.3 ,247.6,246.8,245.7
XS GIS Cut Line= 3
     1887360.679      518144.604     1887493.058      518342.087
     1887549.481       518400.68
#Sta/Elev= 27
       0  970.46     9.5  967.46      19  964.64    28.5  961.01      38  957.88
    57.1  951.18    66.6  947.38    76.1  943.13    95.1  931.73   102.2929.2114
   104.6  928.36   114.1  927.89   122.2928.8284   133.1  930.18   142.6  930.84
   161.7  931.93   180.7  933.39   209.2  936.08   237.8  938.55   246.8  939.17
   264.9  940.25   273.9   940.9   282.9  941.56     292  942.51     301  944.36
     310  947.36   319.1  951.07
#Mann= 3 , 0 , 0
       0      .1       0   102.2    .045       0   122.2      .1       0
Bank Sta=102.2,122.2
XS Rating Curve= 0 ,0
Exp/Cntr=0.3,0.1

Type RM Length L Ch R = 1 ,72996.5 ,248.9,238.4,225.6
XS GIS Cut Line= 3
     1887139.607       518267.63     1887301.867      518488.794
     1887384.628      518564.492
#Sta/Elev= 30
       0   986.8     9.8  982.13    19.6  977.68    29.4   973.4    39.2  969.31
    58.8  961.54    88.2  950.26      98  945.55   107.8  938.79   117.6  932.27
   127.4  928.39   137.2  927.08     147  927.48   148.8927.8159   156.7  929.29
   166.5  930.41   176.3   931.1   225.3  933.84   244.9  934.75   254.7  934.96
   274.3   935.1     293  935.38   302.3  935.79   311.7  936.54     321  937.39
   330.4  938.58   349.1  942.17   367.8  946.08   377.1  947.45   386.5   948.7
#Mann= 3 , 0 , 0
       0      .1       0   127.4    .045       0   148.8      .1       0
Bank Sta=127.4,148.8
XS Rating Curve= 0 ,0
Exp/Cntr=0.3,0.1

Type RM Length L Ch R = 1 ,72758.2 ,206.1,205.6,204.6
XS GIS Cut Line= 5
     1886960.908       518445.44     1887015.369        518508.5
     1887165.854      518584.459     1887631.639      518686.215
     1887676.785      518803.737
#Sta/Elev= 30
       0  962.34    18.5  955.47    27.8  952.46    83.3  935.71    92.7  933.19
   111.4  927.29   120.8  925.13   130.2   924.2   148.9  924.43   167.6  927.52
     177  928.18   223.8  929.92     320  932.75   368.6  934.83   397.8  937.79
   407.6  939.31   446.5  947.78   475.7  952.93   485.4  955.42   602.2  988.26
   611.9  990.29   621.6  991.47   631.4  993.69   650.8 1000.78   660.6 1003.84
   728.7 1023.25   767.4 1025.49   796.4 1024.89   825.5  1022.6   854.6 1018.57
#Mann= 3 , 0 , 0
       0      .1       0   120.8    .045       0   148.9      .1       0
Bank Sta=120.8,148.9
XS Rating Curve= 0 ,0
Exp/Cntr=0.3,0.1

Type RM Length L Ch R = 1 ,72552.6 ,66.5,67.1,66.1
XS GIS Cut Line= 4
     1886845.537      518512.083     1886857.675       518626.93
     1887061.508      518737.299     1887114.976      518930.574
#Sta/Elev= 30
       0  951.69     9.6  949.39    48.1  942.47    57.7  938.25    67.4  931.93
      77  928.22    86.6  928.07   115.5  931.38   125.1  931.14   134.8  929.88
   163.8  924.78   171.6924.0488   183.1  923.63   192.8   924.3   212.1  927.68
   221.7  928.31   289.3  927.09   337.6  927.79   347.3  927.63   356.8  928.06
   385.5  930.79     395  932.94   404.6  936.36   433.2  947.66   461.9  958.27
   471.4  961.02     481  963.46   519.2  972.57   528.7  975.22   547.8  981.17
#Mann= 3 , 0 , 0
       0      .1       0   171.6    .045       0   192.8     .08       0
#XS Ineff= 2 , 0
          116.01  934.58   315.3          934.12
Permanent Ineff=
       F       F
Bank Sta=171.6,192.8
XS Rating Curve= 0 ,0
Exp/Cntr=0.3,0.1

Type RM Length L Ch R = 1 ,72485.5 ,63.7,94.9,127.6
XS GIS Cut Line= 4
      1886790.27       518528.41     1886801.901       518659.31
     1887030.195      518782.923     1887073.164      518922.246
#Sta/Elev= 30
       0  948.14    37.6   942.2    46.9  939.29    56.3  933.08    65.7  928.34
    75.1  928.93    93.9  932.02   103.3  932.72   112.6  932.79     122     932
   131.4  930.54     141  929.57   160.3  928.02   179.5  924.31   189.1  922.98
   198.7  922.33   208.3  922.72     218   923.6   237.2  926.44   246.8  927.43
   275.6  927.08   304.5   927.7   333.3  929.65   362.2  932.47     391  933.98
   400.8  936.47   459.1  956.02   478.5   962.1   507.7  970.35   536.8  978.02
#Mann= 3 , 0 , 0
       0     .08       0   189.1    .045       0   208.3     .08       0
#XS Ineff= 2 , 0
          110.06   935.4
Permanent Ineff=
       F       F
Bank Sta=189.1,208.3
XS Rating Curve= 0 ,0
Exp/Cntr=0.3,0.1

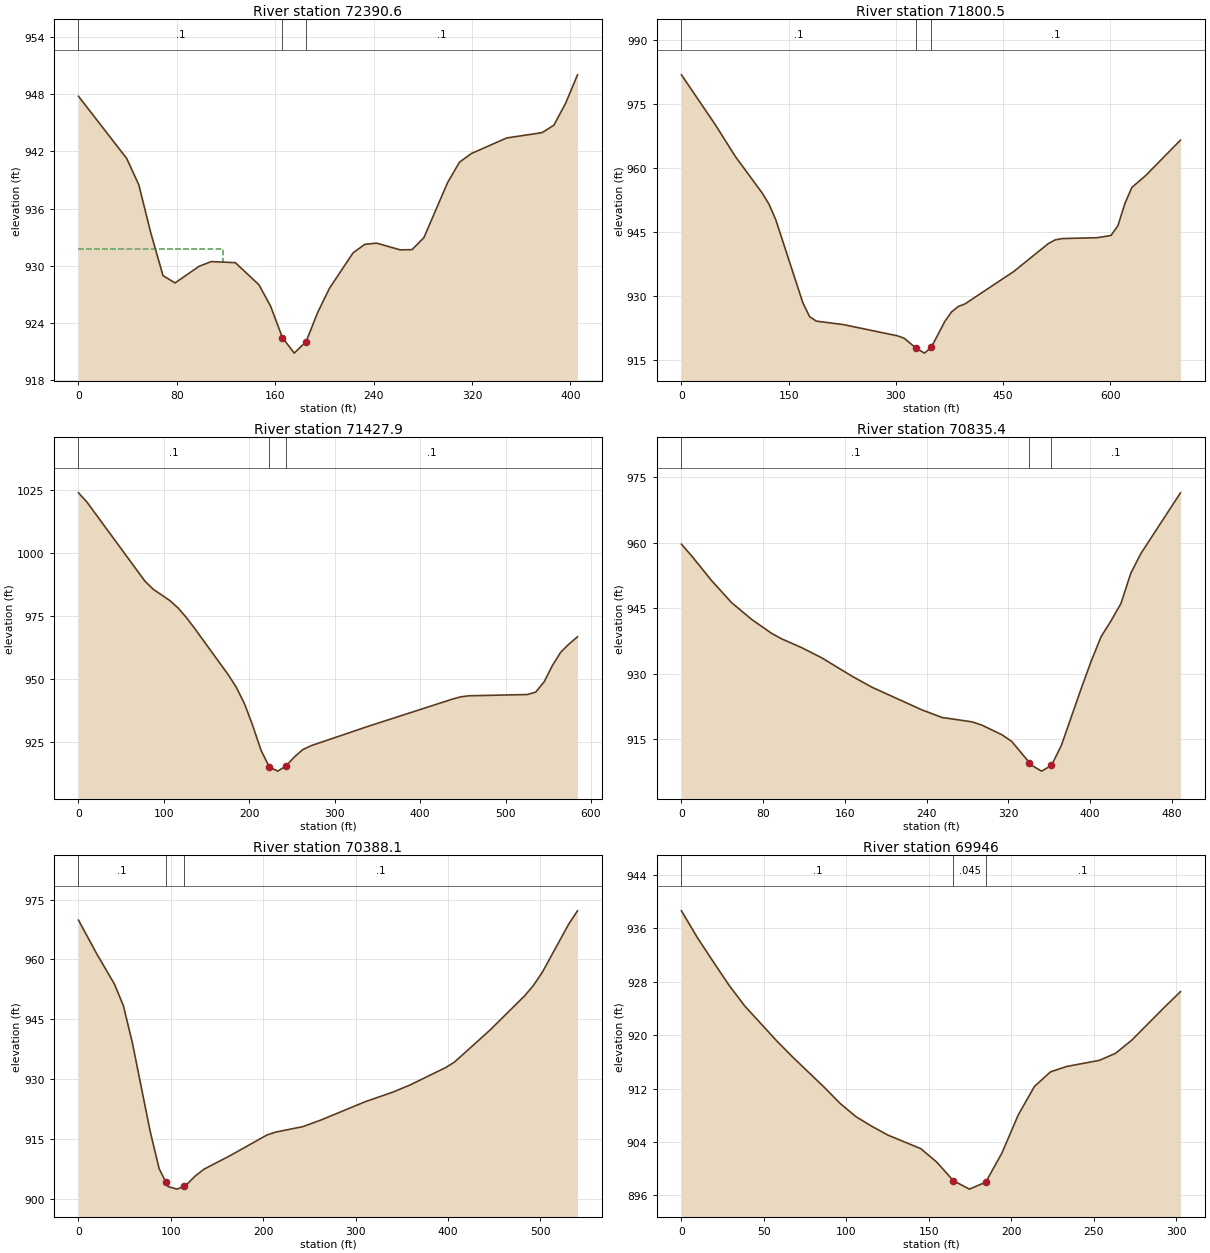
Type RM Length L Ch R = 1 ,72390.6 ,557,590.1,621.6
XS GIS Cut Line= 4
     1886775.696      518526.588     1886775.696      518654.111
     1886746.548      518765.237     1886774.482      518926.159
#Sta/Elev= 30
       0  947.79    39.2  941.26      49  938.51    58.9  933.39    68.7  928.96
    78.5  928.19    98.1  929.94   107.9  930.43   127.5  930.32   146.7     928
   156.2  925.75   165.8  922.45   175.4  920.82     185  922.02   194.5   925.1
   204.1  927.64   223.3  931.36   232.8  932.24   242.4  932.37   261.6  931.66
   271.2  931.69   280.8  932.94     300   938.7   309.7  940.86   319.3  941.77
   348.1  943.41   376.9  943.97   386.5  944.75   396.1  947.07   405.7  950.04
#Mann= 3 , 0 , 0
       0      .1       0   165.8    .045       0     185      .1       0
#XS Ineff= 2 , 0
          117.56  931.72
Permanent Ineff=
       F       F
Bank Sta=165.8,185
XS Rating Curve= 0 ,0
Exp/Cntr=0.3,0.1

Type RM Length L Ch R = 1 ,71800.5 ,410.8,372.6,334.2
XS GIS Cut Line= 4
     1886603.134      518322.095     1886462.186      518474.356
     1886273.822      518456.853     1886191.283      518746.581
#Sta/Elev= 30
       0  981.82    47.2  970.18    75.4  962.71   113.2  954.09   122.6  951.49
     132  947.86   169.8  928.46   179.2  925.23   188.6  924.18   226.4  923.37
   302.1  920.74   311.5  920.17   328.3917.8495   339.9  916.69   349.4  918.05
   368.3  924.09   377.7  926.33   387.2  927.61   396.7  928.22   464.7  935.79
   513.3  942.35     523  943.21   532.7   943.5   581.3   943.7   600.7  944.22
   610.4   946.5   620.2  951.71   629.9  955.46   649.3  958.26   697.9  966.54
#Mann= 3 , 0 , 0
       0      .1       0   328.3    .045       0   349.4      .1       0
Bank Sta=328.3,349.4
XS Rating Curve= 0 ,0
Exp/Cntr=0.3,0.1

Type RM Length L Ch R = 1 ,71427.9 ,583.7,592.5,600.8
XS GIS Cut Line= 3
       1886083.9      518088.448     1886085.394      518496.677
     1886028.035       518663.01
#Sta/Elev= 30
       0 1023.85     9.7 1020.27    77.8  988.77    87.5  985.56   106.9  981.09
   116.6  978.13   126.4   974.3   136.1  969.97     175  951.78   184.7  946.68
   194.4  940.08   204.1  931.33   213.8  921.56   223.6   914.9   233.3  913.35
     243   915.4   252.7  918.96   262.4  921.85   272.2  923.44   340.2  931.26
   437.6  941.92   447.3  942.83   457.1  943.27   525.5  943.76   535.3  944.73
   545.1  948.78   554.8  955.26   564.6  960.59   574.4  963.86   584.2  966.69
#Mann= 3 , 0 , 0
       0      .1       0   223.6    .045       0     243      .1       0
Bank Sta=223.6,243
XS Rating Curve= 0 ,0
Exp/Cntr=0.3,0.1

Type RM Length L Ch R = 1 ,70835.4 ,445.6,447.3,449
XS GIS Cut Line= 3
     1885675.263      518170.244     1885614.055      518448.086
     1885536.819      518637.052
#Sta/Elev= 30
       0   959.7     9.8  957.07    29.4  951.39      49  946.33    68.7  942.47
    88.3  939.27    98.1  938.01   117.7     936   137.4  933.66   166.8  929.48
   186.4  926.94   235.4  921.74   255.1     920   284.5  918.99   294.2  918.24
   313.7  916.04   323.4  914.51   340.7909.6532   342.8  909.06   352.6   907.7
   362.3  909.01     372   913.6   391.4  926.62   401.2  932.91   410.9  938.52
   420.6  942.13   430.3   946.1     440  953.06   449.8  957.54   488.6  971.47
#Mann= 3 , 0 , 0
       0      .1       0   340.7    .045       0   362.3      .1       0
Bank Sta=340.7,362.3
XS Rating Curve= 0 ,0
Exp/Cntr=0.3,0.1

Type RM Length L Ch R = 1 ,70388.1 ,442.6,442,441.2
XS GIS Cut Line= 3
     1885458.083      518082.902     1885302.861      518396.346
     1885295.362      518586.811
#Sta/Elev= 30
       0  969.85    19.4  961.55    38.9  953.82    48.6   948.4    58.3  939.14
    77.7  916.79    87.4  907.49    94.6904.1647    97.1  903.01   106.9  902.38
   114.6903.1911   116.6   903.4   126.3  905.65     136  907.39   165.2  910.91
     204  915.95   213.8   916.7   242.9  918.05   262.3  919.69   310.9  924.34
   340.1  926.68   359.3  928.53   397.4  932.84     407  934.21   445.1  942.15
   483.2  950.87   492.7  953.48   502.3  956.77   530.8  968.82   540.4  972.18
#Mann= 3 , 0 , 0
       0      .1       0    94.6    .045       0   114.6      .1       0
Bank Sta=94.6,114.6
XS Rating Curve= 0 ,0
Exp/Cntr=0.3,0.1

Type RM Length L Ch R = 1 ,69946   ,354.3,358,361.8
XS GIS Cut Line= 3
     1885041.245      517916.581     1885018.322      518029.861
     1884941.419      518200.298
#Sta/Elev= 27
       0  938.62     9.6  934.63    19.3  930.99    28.9  927.46    38.5  924.33
    57.8  919.13    67.4  916.73    86.7  912.16    96.3  909.75   105.9  907.77
   115.6  906.32   125.4     905   145.1     903   154.9  900.96   164.8  898.21
   174.6  896.93   184.5  897.97   194.3  902.32   204.2  908.02     214   912.3
   223.8   914.5   233.7  915.31   253.4  916.22   263.2  917.27     273  919.23
   292.7  924.13   302.6  926.51
#Mann= 3 , 0 , 0
       0      .1       0   164.8    .045       0   184.5      .1       0
Bank Sta=164.8,184.5
XS Rating Curve= 0 ,0
Exp/Cntr=0.3,0.1

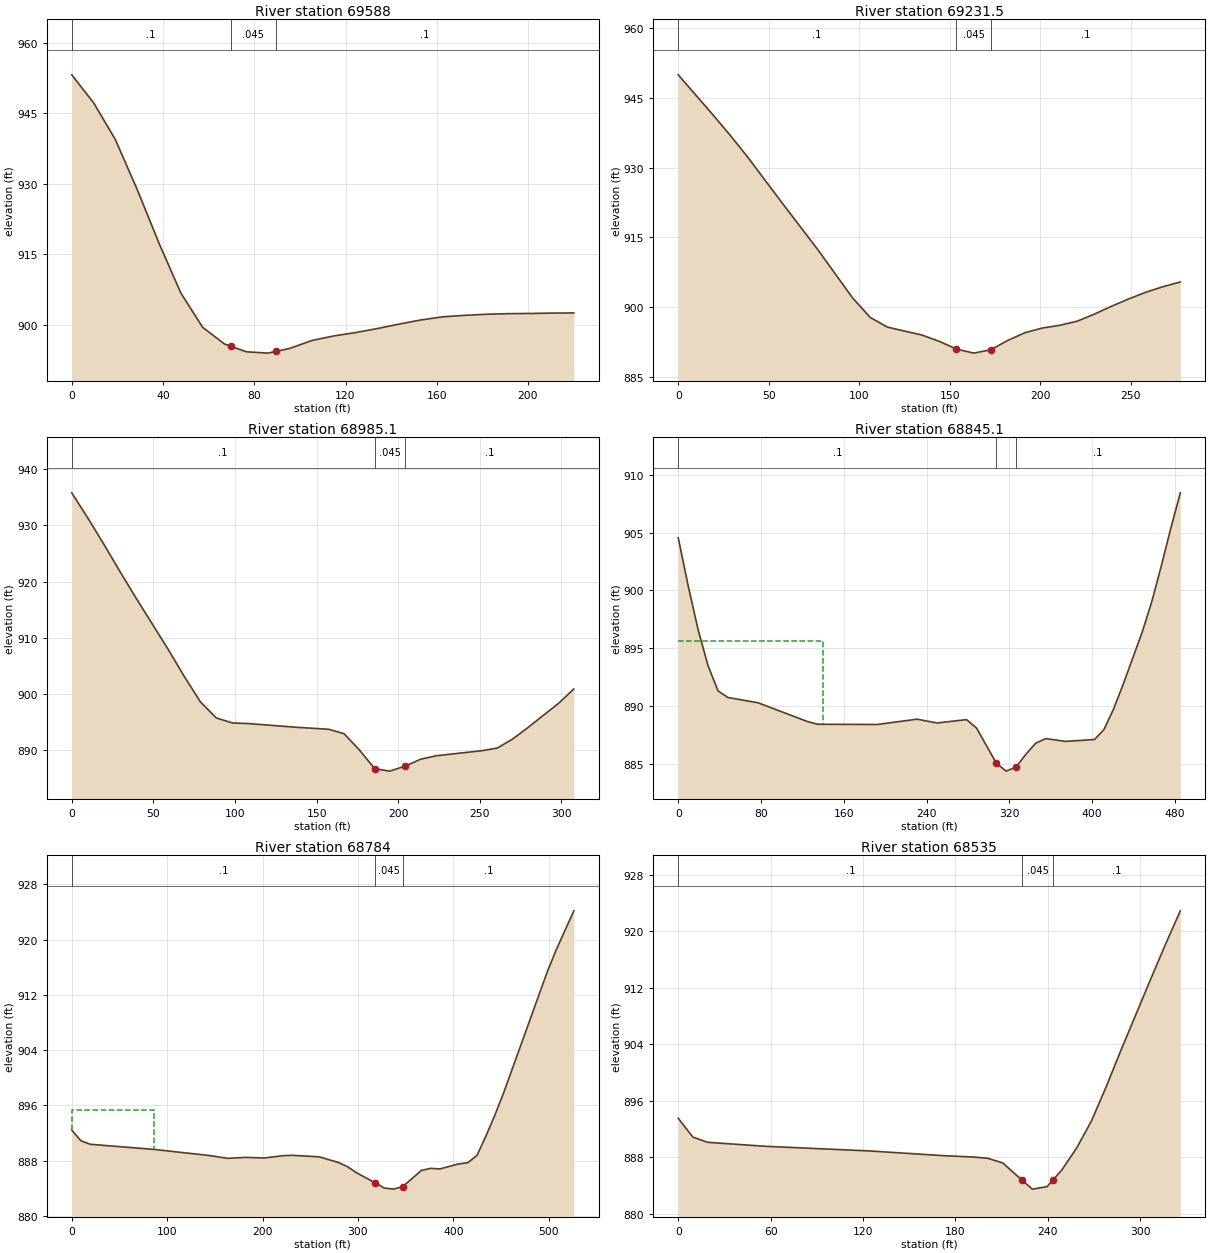
Type RM Length L Ch R = 1 ,69588   ,356.1,356.5,356.8
XS GIS Cut Line= 2
     1884801.916      517748.723     1884679.674      517931.712
#Sta/Elev= 28
       0  953.15     9.6  947.19    19.1  939.38    28.7  928.72    38.3  917.25
    47.8  906.73    57.4   899.4      67  895.85    69.6895.4014    72.1  894.97
    76.5  894.21    86.1  893.92    87.1  894.03    89.6894.2946    95.7  894.94
   105.2   896.6   114.8  897.57   124.4  898.29     134  899.15   143.5   900.1
   153.1  900.98   162.7  901.65   172.2  901.96   181.8  902.19   191.4  902.32
   200.9  902.36   210.5  902.44   220.1  902.47
#Mann= 3 , 0 , 0
       0      .1       0    69.6    .045       0    89.6      .1       0
Bank Sta=69.6,89.6
XS Rating Curve= 0 ,0
Exp/Cntr=0.3,0.1

Type RM Length L Ch R = 1 ,69231.5 ,244,246.4,248.5
XS GIS Cut Line= 3
     1884550.952       517510.41     1884481.981      517590.983
     1884384.625      517731.953
#Sta/Elev= 25
       0  950.01    19.3  941.34    28.9   936.9    38.6  932.18    57.8  922.21
    77.1  912.36    96.4  901.92   106.1  897.74   115.6  895.66   134.6  893.96
   144.1  892.62   153.6  890.95   163.2  890.06   172.7  890.78   182.2  892.82
   191.7  894.48   201.2  895.47   210.8  896.05   220.3  896.92   229.8  898.44
   239.3  900.14   248.8  901.72   258.4  903.18   267.9  904.38   277.4  905.38
#Mann= 3 , 0 , 0
       0      .1       0   153.6    .045       0   172.7      .1       0
Bank Sta=153.6,172.7
XS Rating Curve= 0 ,0
Exp/Cntr=0.3,0.1

Type RM Length L Ch R = 1 ,68985.1 ,167.8,140,112.2
XS GIS Cut Line= 3
     1884447.042      517328.641     1884318.919      517420.036
     1884221.546      517534.492
#Sta/Elev= 26
       0  935.78     9.8  931.32    19.7  926.63    29.5  921.81    39.3  917.13
      59  907.99    68.8  903.22    78.7  898.68    88.5  895.79    98.4  894.89
   108.2  894.78   137.7  894.12   157.4  893.77   166.8  892.98   176.2   890.1
   185.6  886.76   194.8  886.33   204.3  887.22   213.7  888.44   223.1  889.05
   251.3  889.96   260.7  890.43   270.1  892.03   279.5  894.08   298.3  898.39
   307.6  900.93
#Mann= 3 , 0 , 0
       0      .1       0   185.6    .045       0   204.3      .1       0
Bank Sta=185.6,204.3
XS Rating Curve= 0 ,0
Exp/Cntr=0.3,0.1

Type RM Length L Ch R = 1 ,68845.1 ,78.6,61.1,54.7
XS GIS Cut Line= 4
     1884278.525      517068.335     1884168.589      517271.413
     1884213.859      517417.473     1884185.022       517514.76
#Sta/Elev= 30
       0  904.56     9.6  900.41    19.2  896.61    28.9  893.48    38.5  891.32
    48.1  890.75      77   890.3   125.1  888.67   134.7  888.44   192.4  888.42
   230.9  888.88     250  888.55   278.7  888.84   288.3  888.12   307.4  885.09
   316.9  884.39   326.5  884.74     336  885.84   345.6  886.81   355.2   887.2
   374.3  886.96   402.3  887.12   411.5  887.98   420.7  889.74     430  891.87
   448.4  896.39   457.6  898.99   466.9  902.11   476.1  905.37   485.3  908.44
#Mann= 3 , 0 , 0
       0      .1       0   307.4    .045       0   326.5      .1       0
#XS Ineff= 2 , 0
          140.23   895.6
Permanent Ineff=
       F       F
Bank Sta=307.4,326.5
XS Rating Curve= 0 ,0
Exp/Cntr=0.3,0.1

Type RM Length L Ch R = 1 ,68784   ,192.2,248.9,294.7
XS GIS Cut Line= 4
     1884239.082      517030.087     1884120.756       517250.06
     1884174.568      517416.619     1884145.731      517513.905
#Sta/Elev= 30
       0  892.42     9.6  890.87    19.2  890.36    86.5  889.61   144.1  888.73
   163.3  888.32   182.5  888.46   201.7  888.37     221   888.7   230.6  888.76
   259.5  888.54     279  887.74   288.7  887.14   298.4  886.24   317.8  884.79
   327.6  884.02   337.3  883.86     347  884.23   366.5  886.57   376.2  886.87
   385.9  886.79   405.4  887.51   415.1  887.68   424.8  888.76     434   891.5
   443.3  894.51   452.5  897.73   498.6   915.4   507.8  918.52   526.3  924.18
#Mann= 3 , 0 , 0
       0      .1       0   317.8    .045       0     347      .1       0
#XS Ineff= 2 , 0
           86.26  895.33
Permanent Ineff=
       F       F
Bank Sta=317.8,347
XS Rating Curve= 0 ,0
Exp/Cntr=0.3,0.1

Type RM Length L Ch R = 1 ,68535   ,152.3,150.8,149.3
XS GIS Cut Line= 3
     1884235.174      517011.504     1884151.269      517056.655
     1883935.297      517137.926
#Sta/Elev= 21
       0  893.54     9.5  890.87    19.1  890.13    57.2  889.56   124.1  888.91
   172.2  888.24   191.4  888.05     201  887.87   210.7  887.21   223.4884.7332
   229.9   883.5   239.5  883.85   243.4884.8188   249.1  886.23   258.7  889.32
   268.4   893.2     278  898.06   287.6  903.25   306.8  913.26   316.4  918.18
     326  922.92
#Mann= 3 , 0 , 0
       0      .1       0   223.4    .045       0   243.4      .1       0
Bank Sta=223.4,243.4
XS Rating Curve= 0 ,0
Exp/Cntr=0.3,0.1

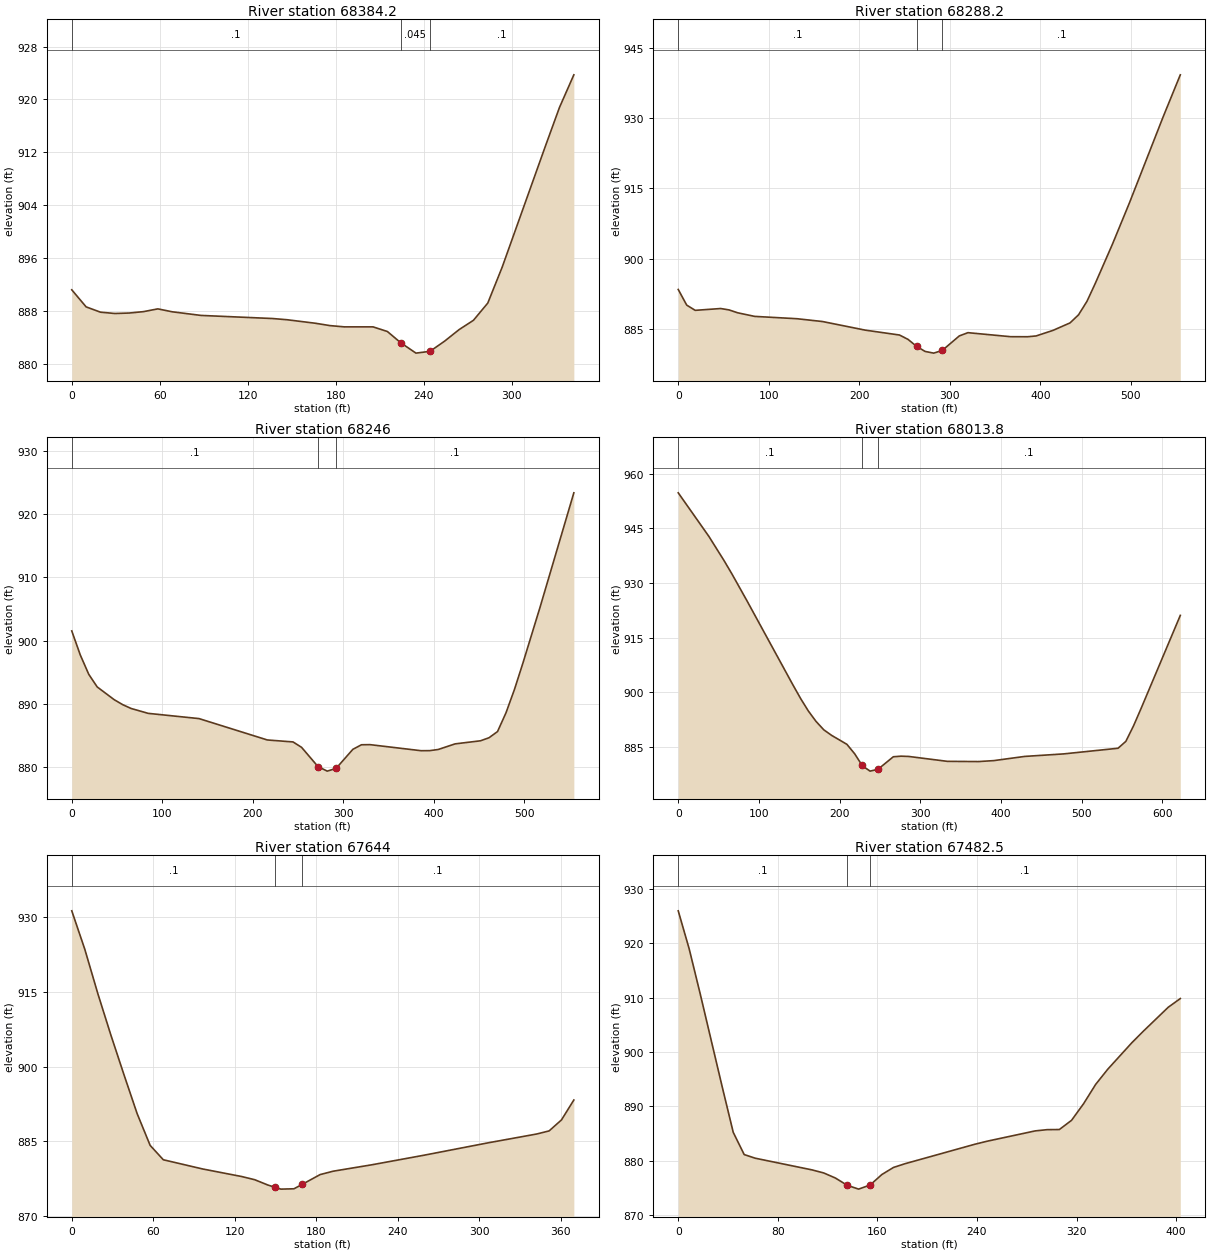
Type RM Length L Ch R = 1 ,68384.2 ,79.5,96,114.2
XS GIS Cut Line= 2
     1884175.422      516869.963     1883863.657      517011.752
#Sta/Elev= 27
       0  891.22     9.8  888.64    19.6  887.84    29.4  887.64    39.1  887.71
    48.9  887.92    58.7  888.34    68.5   887.9    88.1  887.35     137  886.88
   146.8   886.7   166.4  886.16   176.1  885.81   185.9  885.62   205.5  885.62
   215.3  884.92   224.4883.2208   234.8  881.65   244.4881.9241   254.4  883.47
   264.2   885.2     274  886.61   283.8  889.22   293.6  894.64   322.9  912.82
   332.7  918.79   342.5  923.72
#Mann= 3 , 0 , 0
       0      .1       0   224.4    .045       0   244.4      .1       0
Bank Sta=224.4,244.4
XS Rating Curve= 0 ,0
Exp/Cntr=0.3,0.1

Type RM Length L Ch R = 1 ,68288.2 ,41.6,42.2,41.6
XS GIS Cut Line= 4
     1884172.859      516854.588     1884021.675      516904.983
     1883816.678      516870.817     1883666.348       516982.71
#Sta/Elev= 30
       0  893.39     9.4  890.04    18.8  888.93    46.9  889.32    56.2  889.02
    65.6  888.41    84.4  887.64   131.2  887.14   159.4  886.54   206.6   884.7
   244.4  883.66   253.8  882.73   263.3  881.24   272.7  880.15   282.2  879.79
   291.6  880.36   310.5  883.47     320  884.16   367.2   883.3   385.9  883.29
   395.3  883.46     414  884.65   432.8  886.25   442.2  887.98   451.5  890.86
   460.9  894.78   479.6  903.05   498.4  911.89   535.8  930.35   554.6  939.25
#Mann= 3 , 0 , 0
       0      .1       0   263.3    .045       0   291.6      .1       0
Bank Sta=263.3,291.6
XS Rating Curve= 0 ,0
Exp/Cntr=0.3,0.1

Type RM Length L Ch R = 1 ,68246   ,251.5,232.3,212.5
XS GIS Cut Line= 4
     1884158.339      516821.276     1884007.154      516871.671
     1883802.158      516837.505     1883651.827      516949.399
#Sta/Elev= 30
       0  901.53     9.4  897.73    18.8  894.66    28.1  892.67    46.9  890.65
    56.2  889.87    65.6  889.26    84.4  888.49   140.6  887.66     216  884.28
   244.4  883.97   253.8  883.12     272880.0677   282.2  879.35     292879.7827
   310.5   882.8     320  883.52   329.4  883.54   385.9  882.58   395.3  882.59
   404.7  882.77   423.4  883.66   451.5  884.15   460.9  884.63   470.3  885.61
   479.6  888.56     489  892.27   498.4  896.47   517.1   905.2   554.6  923.38
#Mann= 3 , 0 , 0
       0      .1       0     272    .045       0     292      .1       0
Bank Sta=272,292
XS Rating Curve= 0 ,0
Exp/Cntr=0.3,0.1

Type RM Length L Ch R = 1 ,68013.8 ,394.8,369.7,344.5
XS GIS Cut Line= 4
     1883903.802      516461.678     1883831.199       516616.28
     1883590.328      516754.652     1883569.829      516927.191
#Sta/Elev= 30
       0  954.72      38  942.77    56.9   936.1    66.4  932.54    85.4  925.04
   142.3     902   151.8  898.28   161.3   894.9   170.8  892.05   180.4  889.75
     190  888.24   209.1  885.76   218.7  883.17   227.5880.1358   228.3  879.86
   237.8  878.42   247.5878.9093   266.6  882.36   276.2  882.52   285.8  882.44
   333.6   881.1     372  881.04   391.1   881.3   429.4  882.45   477.6  883.14
   545.1  884.69   554.8  886.58   564.4  890.87   574.1  895.82   622.3  921.12
#Mann= 3 , 0 , 0
       0      .1       0   227.5    .045       0   247.5      .1       0
Bank Sta=227.5,247.5
XS Rating Curve= 0 ,0
Exp/Cntr=0.3,0.1

Type RM Length L Ch R = 1 ,67644   ,147.6,161.6,175.9
XS GIS Cut Line= 3
     1883456.951      516509.821      1883469.91      516778.906
     1883461.525      516878.765
#Sta/Elev= 25
       0  931.33     9.6   923.6    19.2  914.68    28.9  906.27    38.5  898.34
    48.1  890.59    57.7  884.19    67.4   881.3    96.2  879.46   125.1  877.93
   134.7  877.29   144.3  876.23   149.5875.7775   153.9   875.4   163.6  875.47
   169.5876.3369   182.8  878.32   192.4     879   221.3  880.31   259.8  882.24
   305.8  884.67   342.3  886.48   351.4   887.1   360.5  889.31   369.6  893.31
#Mann= 3 , 0 , 0
       0      .1       0   149.5    .045       0   169.5      .1       0
Bank Sta=149.5,169.5
XS Rating Curve= 0 ,0
Exp/Cntr=0.3,0.1

Type RM Length L Ch R = 1 ,67482.5 ,529.6,529.7,529.4
XS GIS Cut Line= 4
     1883354.809      516521.059      1883343.89      516599.867
     1883256.536      516732.322     1883138.323      516847.686
#Sta/Elev= 29
       0  925.93     8.8  918.94    17.7  910.63    35.4  893.52    44.2  885.22
      53  881.14    61.9  880.47   107.6  878.32   116.9  877.76   126.2  876.84
   135.6  875.52   144.9  874.79   154.2  875.55   163.6  877.47   172.9  878.77
   182.2  879.46   238.2  883.03   247.9  883.58   286.8  885.49   296.5  885.72
   306.2  885.74     316  887.43   325.7  890.49   335.4  894.04   345.1  896.82
   364.5   901.7   374.2  903.92   393.7  908.21   403.4  909.81
#Mann= 3 , 0 , 0
       0      .1       0   135.6    .045       0   154.2      .1       0
Bank Sta=135.6,154.2
XS Rating Curve= 0 ,0
Exp/Cntr=0.3,0.1