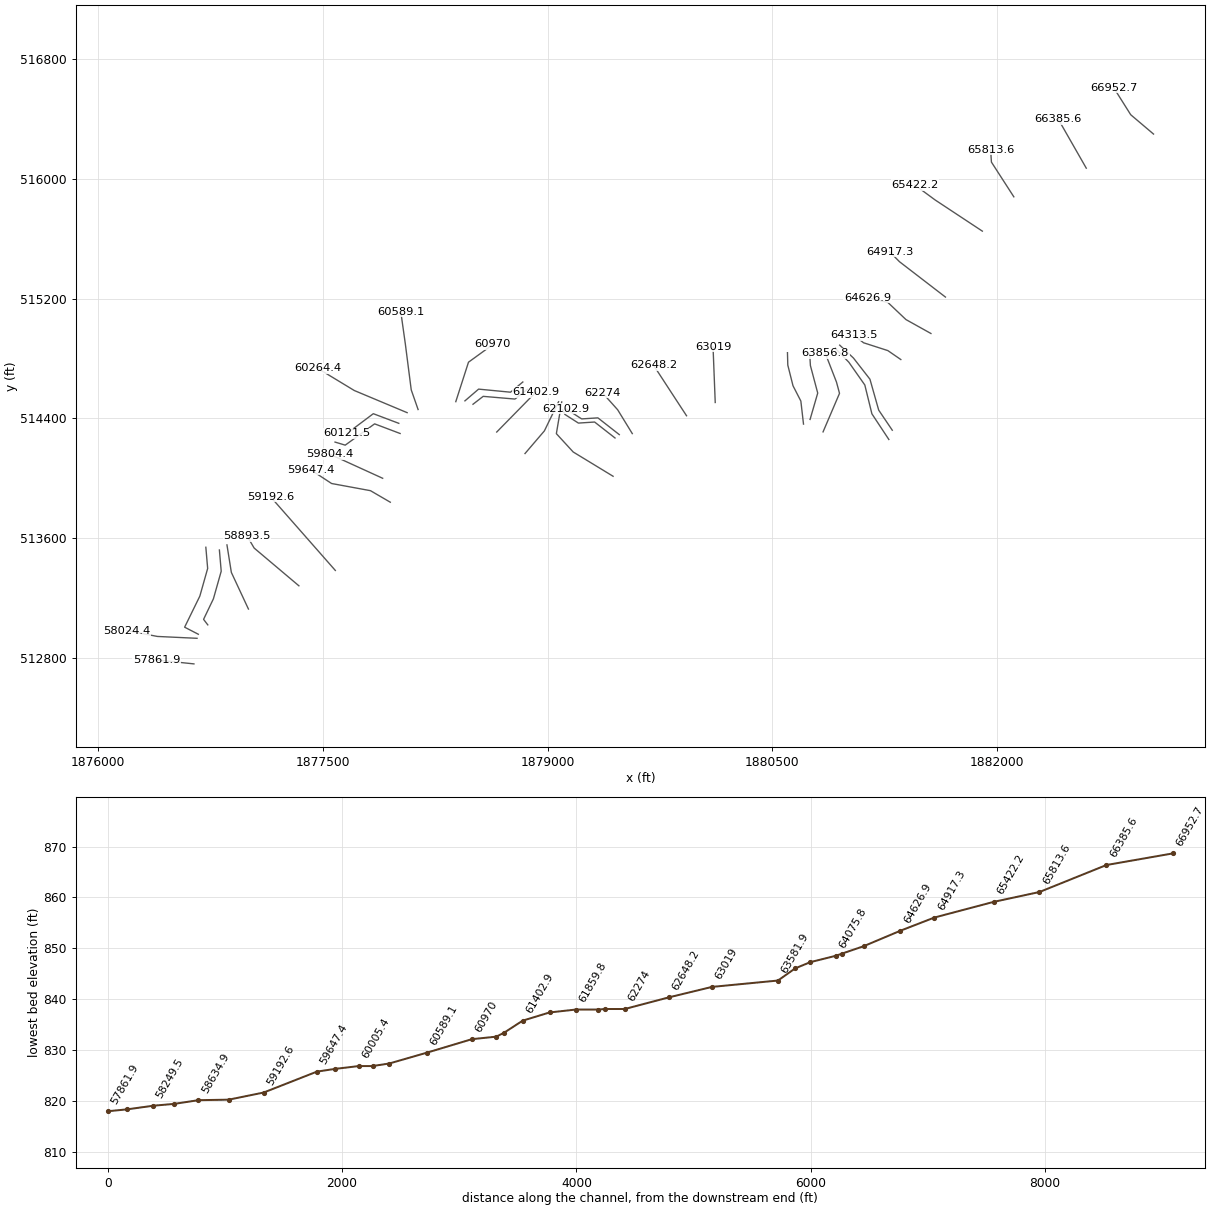
HEC-RAS study FALLINGRCR.prj: FALLINGRCR

--- FALLINGRCR.g01 (geometry) --- (continued)

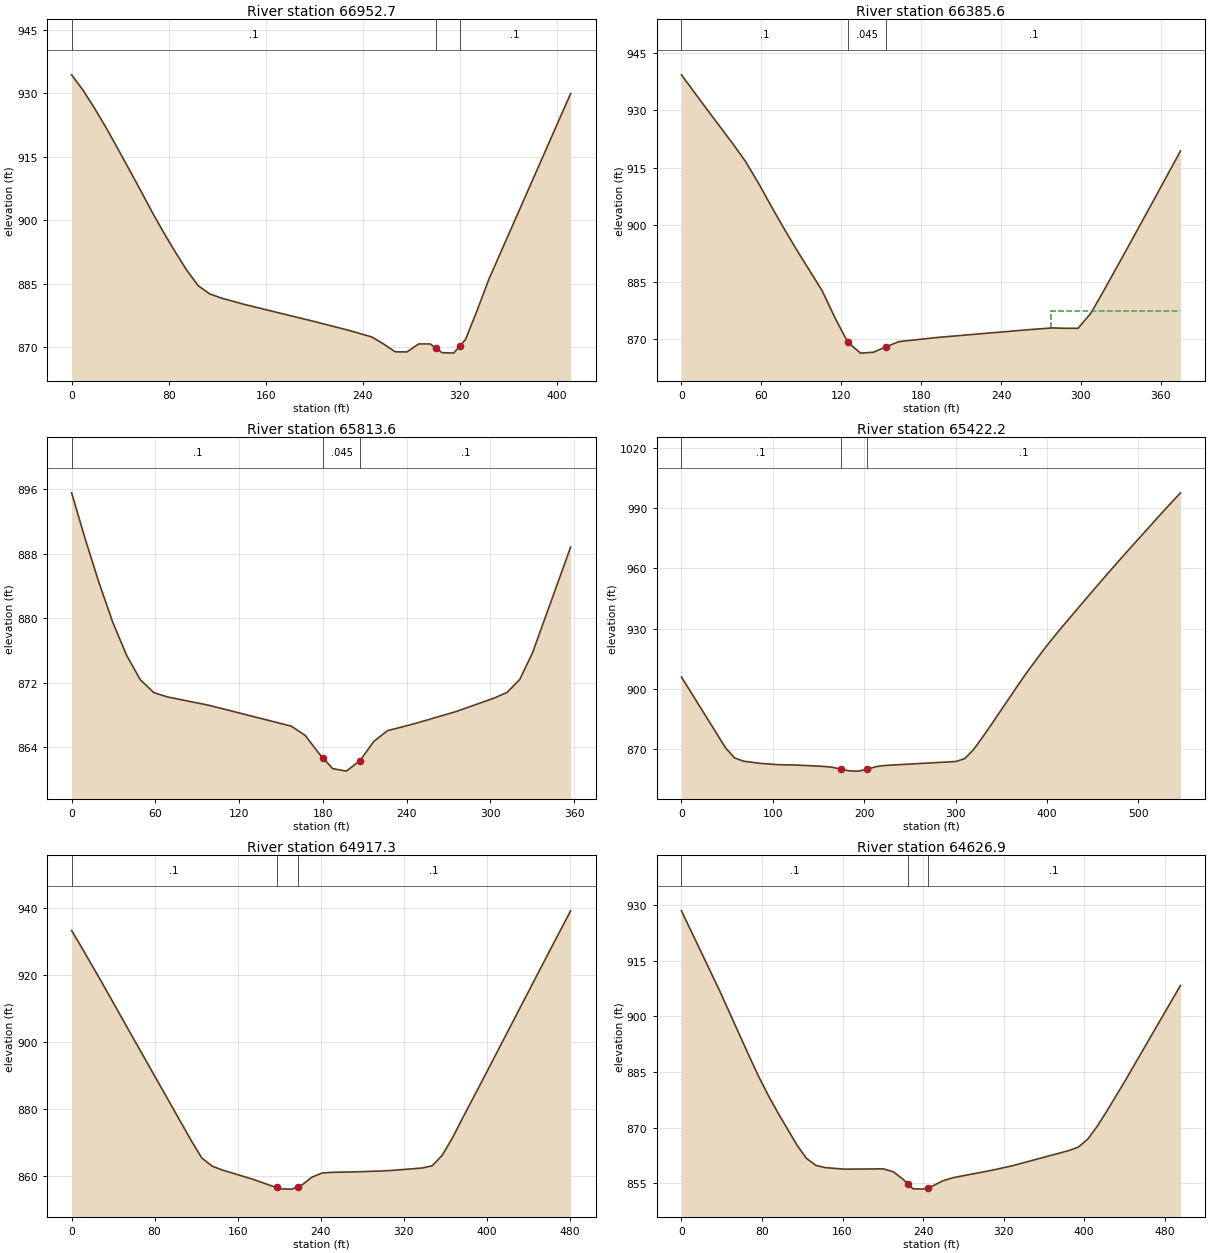
Type RM Length L Ch R = 1 ,66952.7 ,567.3,567.1,566.7
XS GIS Cut Line= 3
     1883042.234      516296.313     1882890.125       516425.13
     1882777.046      516604.582
#Sta/Elev= 30
       0  934.41     9.5  930.74      19  926.47    28.5  921.89      38  917.01
      57  907.04    66.4  901.97    75.9  897.15    85.4  892.57    94.9  888.26
   104.4  884.57   113.9  882.64   123.4  881.67   142.4  880.16   199.3  876.18
   228.2  874.06   247.5  872.47   257.2  870.81   266.8  868.96   276.5  868.94
   286.1  870.82   295.7  870.82     300869.9094   305.4  868.77     315  868.65
     320870.3064   324.7  871.86   334.3  878.73     344   886.1   411.4  929.96
#Mann= 3 , 0 , 0
       0      .1       0     300    .045       0     320      .1       0
Bank Sta=300,320
XS Rating Curve= 0 ,0
Exp/Cntr=0.3,0.1

Type RM Length L Ch R = 1 ,66385.6 ,570.6,572,573.2
XS GIS Cut Line= 2
     1882593.542      516068.906     1882407.505      516394.143
#Sta/Elev= 26
       0  939.34    19.2  930.27    38.4  921.36      48  916.68    57.6  911.07
    67.2  905.03    76.9   899.1    86.5  893.47   105.7  882.69   115.3  875.62
   124.7869.3729   124.9  869.24   134.5  866.37   144.1   866.6   153.7  868.03
   163.3  869.39   192.2  870.48   259.4  872.48   278.6  872.98   288.2  872.88
   297.8  872.88   307.4  876.82     317  882.67   336.3  894.82   355.5  907.04
   374.7  919.37
#Mann= 3 , 0 , 0
       0      .1       0   124.7    .045       0   153.7      .1       0
#XS Ineff= 2 , 0
                          277.34          877.47
Permanent Ineff=
       F       F
Bank Sta=124.7,153.7
XS Rating Curve= 0 ,0
Exp/Cntr=0.3,0.1

Type RM Length L Ch R = 1 ,65813.6 ,382.1,391.3,400.7
XS GIS Cut Line= 3
     1882110.231      515877.932     1881960.784      516109.392
      1881955.53       516191.23
#Sta/Elev= 25
       0  895.53     9.8  889.78    19.7  884.36    29.5  879.49    39.4  875.41
    49.2  872.39      59  870.78    68.9  870.25    98.4  869.22   157.4  866.64
   167.3   865.5   177.1  863.29   180.4862.6527     187  861.38   196.8  861.07
   206.6  862.36   216.5  864.75   226.3  866.08     246  866.96   275.5  868.45
   302.8  870.12     312  870.82   321.1  872.43   330.2  875.72   357.5   888.8
#Mann= 3 , 0 , 0
       0      .1       0   180.4    .045       0   206.6      .1       0
Bank Sta=180.4,206.6
XS Rating Curve= 0 ,0
Exp/Cntr=0.3,0.1

Type RM Length L Ch R = 1 ,65422.2 ,506.6,504.9,503.5
XS GIS Cut Line= 3
     1881900.321      515649.057     1881585.217      515856.956
     1881449.454      515956.681
#Sta/Elev= 30
       0  905.92    48.4  870.61    58.1  865.72    67.8  864.08    87.1  862.94
   106.5  862.33   125.8  862.14   154.9   861.5   164.6   861.1   174.4860.1022
   183.9  859.24   193.6  859.13   203.3  860.05     213  861.36   222.6  861.95
   300.1  863.91   309.8  865.32   319.4   869.7   329.1  875.76   338.8  882.12
   367.8  901.56   377.5  907.94   396.2  919.41   405.6   924.8   414.9  929.96
     443  944.99   461.7  954.89   480.4  964.62   527.2  988.27     546  997.48
#Mann= 3 , 0 , 0
       0      .1       0   174.4    .045       0   203.3      .1       0
Bank Sta=174.4,203.3
XS Rating Curve= 0 ,0
Exp/Cntr=0.3,0.1

Type RM Length L Ch R = 1 ,64917.3 ,292.5,290.4,288.8
XS GIS Cut Line= 3
     1881653.951      515209.619     1881347.701      515445.036
     1881281.034      515512.397
#Sta/Elev= 29
       0   933.4     9.7  928.35      29  917.96    57.9  902.04   115.9  870.26
   125.5  865.38   135.2  862.98   144.8  861.82   173.8   859.1   193.1  857.01
   197.8856.5726   202.8  856.11   212.4  856.06   217.8856.7635   222.1  857.32
   231.8  859.66   241.4  860.87   251.1  861.09   270.4   861.2   299.4  861.49
     309  861.66     338  862.38   347.6  863.05   357.3  866.21     367  871.34
   376.6  877.14   395.8  888.49   462.1  928.12     481   939.3
#Mann= 3 , 0 , 0
       0      .1       0   197.8    .045       0   217.8      .1       0
Bank Sta=197.8,217.8
XS Rating Curve= 0 ,0
Exp/Cntr=0.3,0.1

Type RM Length L Ch R = 1 ,64626.9 ,303.3,313.4,322.5
XS GIS Cut Line= 4
     1881557.288      514966.726     1881390.565      515059.556
     1881269.564      515174.091     1881134.707      515204.572
#Sta/Elev= 30
       0  928.46    38.2  906.77    66.8  889.59    76.3  884.03    85.9  878.91
    95.4  874.24   114.5  865.45     124   861.8   133.6  859.85   143.1  859.26
   162.2  858.85   200.6  858.93   210.4  858.15   220.2  856.11   224.6854.9622
     230  853.56   239.8  853.47   244.6853.8833   249.6  854.31   259.4  855.68
   269.2  856.52   308.4  858.55     328  859.72   385.1  863.88   394.3  864.81
   403.5   866.9   412.7  870.28     422  874.24   440.4  882.51   495.7  908.36
#Mann= 3 , 0 , 0
       0      .1       0   224.6    .045       0   244.6      .1       0
Bank Sta=224.6,244.6
XS Rating Curve= 0 ,0
Exp/Cntr=0.3,0.1

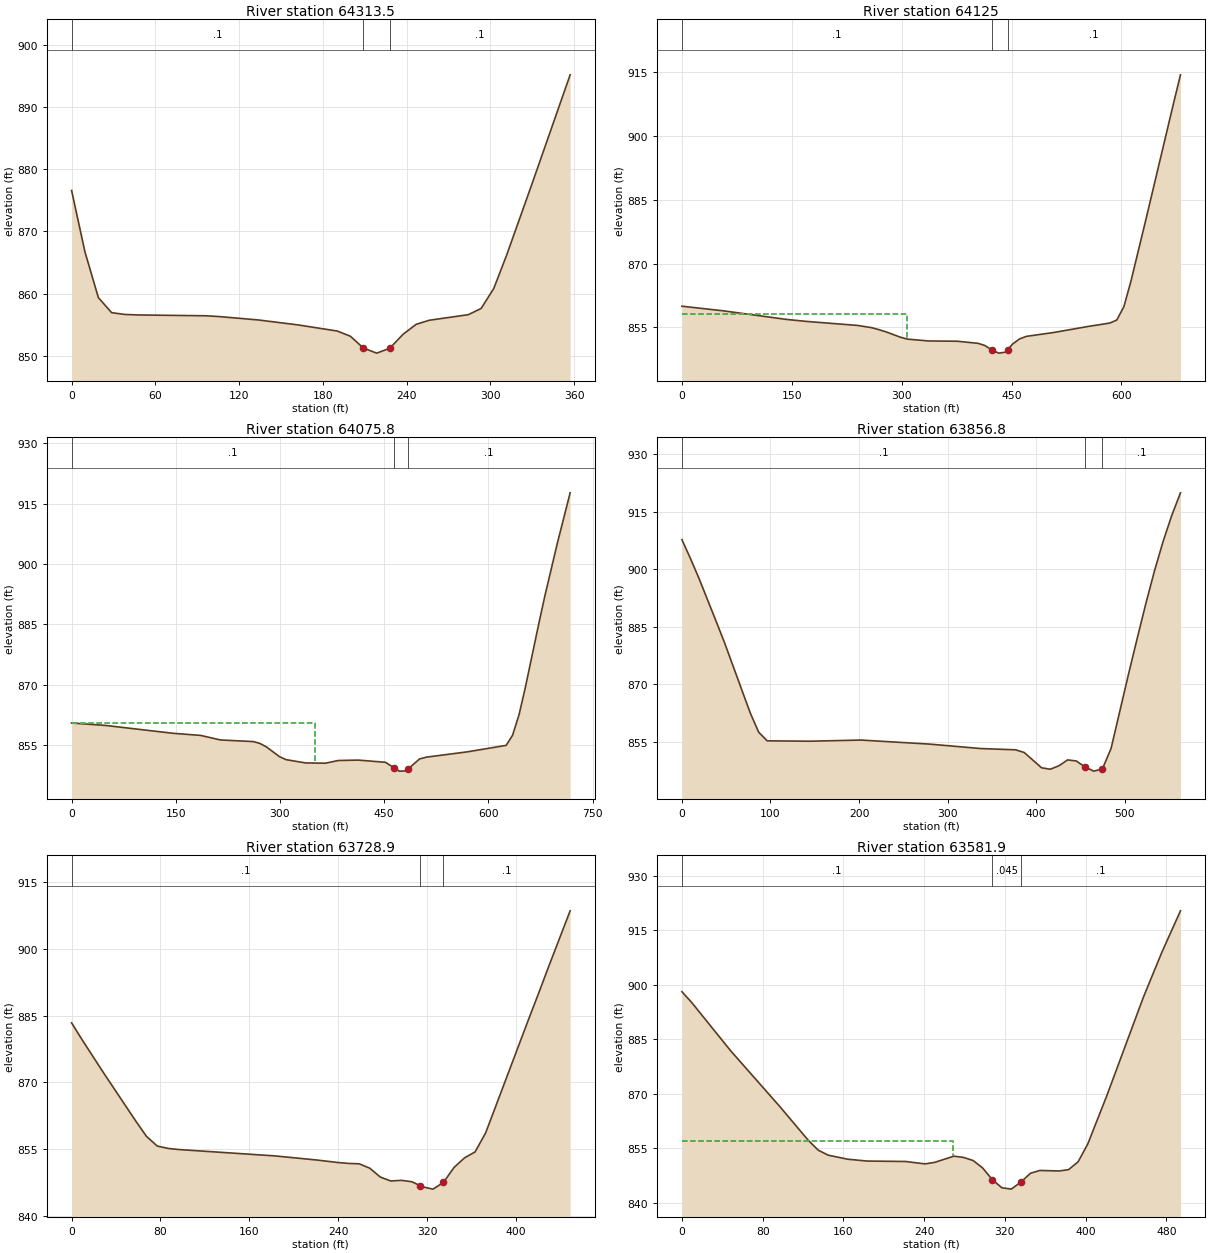
Type RM Length L Ch R = 1 ,64313.5 ,202.6,188.5,173.2
XS GIS Cut Line= 4
     1881356.435      514793.078      1881269.63      514852.757
     1881107.954       514904.84      1881042.85      514954.753
#Sta/Elev= 24
       0  876.55     9.6  866.67    19.2  859.34    28.7  856.93    38.3  856.64
    47.9  856.56    95.8  856.43   105.3  856.31   133.6  855.76     162  854.97
   190.3  853.98   199.7  853.15   209.1  851.24   218.6  850.43     228  851.21
   237.4  853.44   246.9  855.06   256.3  855.71   284.3  856.61   293.4   857.6
   302.5  860.82   311.7  866.17   329.9  877.63   357.2  895.13
#Mann= 3 , 0 , 0
       0      .1       0   209.1    .045       0     228      .1       0
Bank Sta=209.1,228
XS Rating Curve= 0 ,0
Exp/Cntr=0.3,0.1

Type RM Length L Ch R = 1 ,64125   ,50.2,49.2,49.4
XS GIS Cut Line= 5
     1881299.368      514321.882     1881208.772       514455.82
     1881150.425      514661.818     1881040.298       514803.13
     1880948.707      514889.088
#Sta/Elev= 30
       0  859.99    57.1  858.89   142.7  856.88   171.4  856.39   239.6  855.47
     259  854.94   268.8  854.48   278.5  853.96     298  852.71   307.7  852.25
   336.9  851.81   375.8  851.75   404.1  851.26   413.5  850.75     423  849.69
   432.4  848.95   441.8  849.18   444.6  849.74   451.2  851.06   460.7  852.27
   470.1  852.89   507.8  853.81     555  855.24     584  856.02   593.6  856.73
   603.3  859.87   612.9  865.83   632.3  879.61   670.9  907.57   680.6  914.43
#Mann= 3 , 0 , 0
       0      .1       0     423    .045       0   444.6      .1       0
#XS Ineff= 2 , 0
          307.86  858.13
Permanent Ineff=
       F       F
Bank Sta=423,444.6
XS Rating Curve= 0 ,0
Exp/Cntr=0.3,0.1

Type RM Length L Ch R = 1 ,64075.8 ,223.7,219,213.7
XS GIS Cut Line= 5
     1881276.451      514260.076     1881163.427      514431.122
     1881116.133      514623.491     1881009.311      514775.515
     1880919.121      514867.571
#Sta/Elev= 30
       0   860.5    48.8   859.9   146.4  857.94   185.5  857.43   214.4  856.29
   261.6  855.89     271  855.44   280.5  854.57   299.4  852.14   308.8   851.4
   337.1  850.58   365.4  850.52   384.2  851.19   412.9  851.29     452  850.74
   464.3 849.375   471.6  848.55   481.3  848.59   484.3 849.049   500.9  851.57
   510.7  852.02   569.4  853.33   625.7  854.95   634.9  857.46   644.2  862.54
   653.4  869.42   671.8  884.47     681  891.77   699.4  905.18   717.8  917.68
#Mann= 3 , 0 , 0
       0      .1       0   464.3    .045       0   484.3      .1       0
#XS Ineff= 2 , 0
          350.14   860.4
Permanent Ineff=
       F       F
Bank Sta=464.3,484.3
XS Rating Curve= 0 ,0
Exp/Cntr=0.3,0.1

Type RM Length L Ch R = 1 ,63856.8 ,130.8,127.9,125.2
XS GIS Cut Line= 4
     1880837.562      514310.771     1880947.362      514567.683
     1880927.146      514642.715     1880852.554      514834.624
#Sta/Elev= 30
       0  907.72     9.6  902.82    19.3  897.59    38.5  886.48    48.2  880.77
    77.1  862.51    86.7  857.44    96.3   855.2   144.5   855.1   202.3   855.4
   279.4  854.35   337.7  853.18   376.7  852.86   386.5  852.16   406.1  848.17
   415.9  847.78   425.7  848.68   435.5  850.22   445.3  849.94   455.2  848.38
     465  847.29   474.8  847.85   484.6   853.2   504.2   872.5     514  881.82
   523.8  890.96   533.6  899.55   543.4  907.27   553.2  914.08     563  919.95
#Mann= 3 , 0 , 0
       0      .1       0   455.2    .045       0   474.8      .1       0
Bank Sta=455.2,474.8
XS Rating Curve= 0 ,0
Exp/Cntr=0.3,0.1

Type RM Length L Ch R = 1 ,63728.9 ,147.4,147,146.7
XS GIS Cut Line= 4
     1880750.966      514393.772     1880801.965      514569.554
     1880753.137       514752.93     1880748.796      514828.885
#Sta/Elev= 30
       0  883.35     9.6  879.52    28.9  872.11    57.8  861.34    67.4  857.92
    77.1  855.74    86.7  855.21    96.3  854.96     183  853.53     221   852.6
     240  852.04   249.4  851.84   258.9  851.76   268.4  850.79   277.9   848.8
   287.4   847.9   296.9  848.05   306.4  847.74   313.7 846.864   315.9   846.6
   325.4  846.08   334.8  847.57   344.3  850.92   353.8  853.09   363.3  854.42
   372.8  858.67   410.8   883.7   420.4  889.92   429.8  896.12   448.9  908.47
#Mann= 3 , 0 , 0
       0      .1       0   313.7    .045       0   334.8      .1       0
Bank Sta=313.7,334.8
XS Rating Curve= 0 ,0
Exp/Cntr=0.3,0.1

Type RM Length L Ch R = 1 ,63581.9 ,567,562.9,558.1
XS GIS Cut Line= 5
     1880707.128      514362.625     1880689.455       514516.11
     1880636.973      514618.482     1880602.312      514756.186
     1880600.142      514838.651
#Sta/Elev= 30
       0  898.03     9.7  895.06    48.3  881.77    96.6  866.55   125.5  857.03
   135.2  854.39   144.8  853.05   164.1  851.93   183.3  851.42   221.6   851.3
   240.8  850.64   250.4  851.05   269.5  852.77     279  852.42   288.5  851.57
   297.9  849.54   307.4  846.34   316.9  844.08   326.3  843.69   335.8  845.61
   345.3  848.05   354.7  848.83   373.7  848.69   383.1  849.05   392.6  851.23
   402.1   856.1   420.7  869.19   457.4  896.63   475.7  908.99     494   920.3
#Mann= 3 , 0 , 0
       0      .1       0   307.4    .045       0   335.8      .1       0
#XS Ineff= 2 , 0
          268.77  856.83
Permanent Ineff=
       F       F
Bank Sta=307.4,335.8
XS Rating Curve= 0 ,0
Exp/Cntr=0.3,0.1

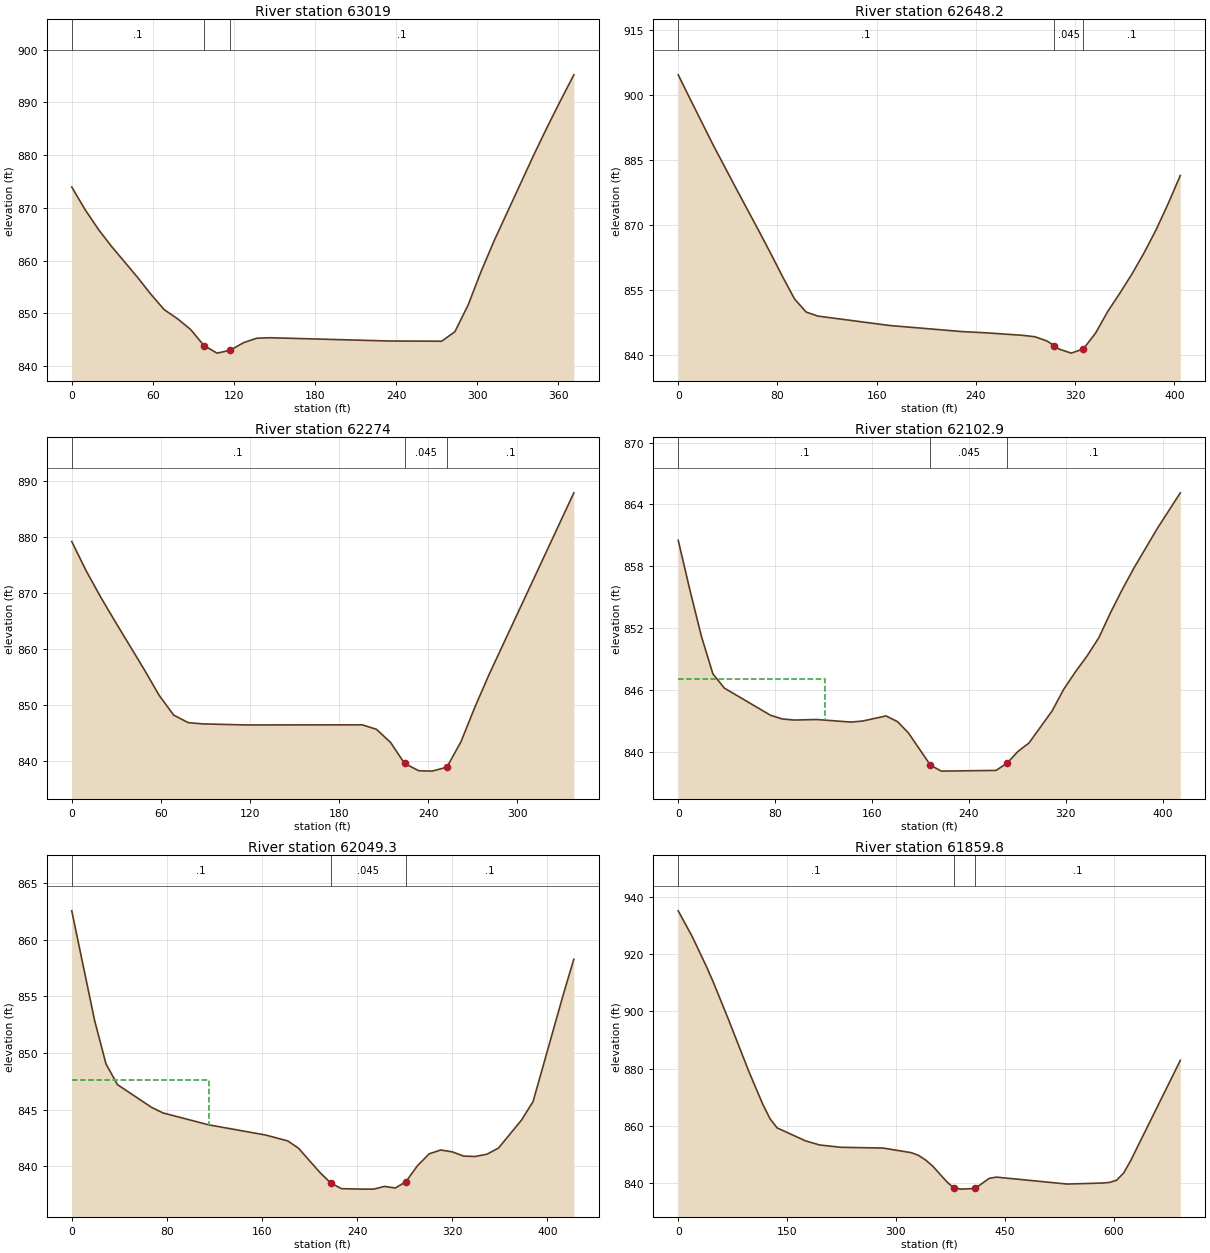
Type RM Length L Ch R = 1 ,63019   ,358.3,370.8,383
XS GIS Cut Line= 2
     1880118.235      514506.698     1880103.586      514877.875
#Sta/Elev= 25
       0  873.95     9.8  869.69    19.6  865.96    29.3  862.73    48.9  856.75
    58.6  853.59    68.4  850.69    78.2  848.97      88  846.91    97.8  843.88
   107.5  842.44   117.2842.9842   127.1  844.42   136.9  845.27   146.6  845.36
   234.6  844.74   273.7   844.7   283.5  846.51   293.3  851.58     303  858.02
   312.8  863.92   342.1  880.17   351.9  885.38   361.7  890.38   371.5  895.24
#Mann= 3 , 0 , 0
       0      .1       0    97.8    .045       0   117.2      .1       0
Bank Sta=97.8,117.2
XS Rating Curve= 0 ,0
Exp/Cntr=0.3,0.1

Type RM Length L Ch R = 1 ,62648.2 ,370.8,374.2,377.5
XS GIS Cut Line= 3
     1879926.808      514418.258      1879854.91      514528.082
     1879705.526      514757.122
#Sta/Elev= 28
       0  904.73     9.4  899.26    28.1  888.54    46.9  878.32    65.6  868.31
      75  863.17    84.4  857.89    93.8  852.88   103.1  849.87   112.5  848.94
   170.3  846.76   228.9  845.35   248.5  845.06   277.8  844.48   287.5  844.16
   297.3  843.17     303842.0856   307.1   841.3   316.8  840.37   326.6  841.35
   336.4     845   346.1  849.95   355.9   854.2   365.6  858.61   375.4  863.51
   385.2  868.91     395  874.99   404.7  881.46
#Mann= 3 , 0 , 0
       0      .1       0     303    .045       0   326.6      .1       0
Bank Sta=303,326.6
XS Rating Curve= 0 ,0
Exp/Cntr=0.3,0.1

Type RM Length L Ch R = 1 ,62274   ,135.8,171.1,209.3
XS GIS Cut Line= 3
     1879564.883      514299.284     1879467.555      514457.867
     1879366.249      514571.091
#Sta/Elev= 21
       0  879.17     9.8  873.88    19.6  869.17    29.4  864.77      49  856.18
    58.8  851.67    68.6  848.13    78.3  846.78    88.1  846.55   117.5  846.36
   195.6  846.38   205.1  845.58   214.6  843.24     224  839.49   233.6  838.17
   242.5   838.1   252.5   838.8     262  843.35   271.5  849.62     281  855.42
     338  887.88
#Mann= 3 , 0 , 0
       0      .1       0     224    .045       0   252.5      .1       0
Bank Sta=224,252.5
XS Rating Curve= 0 ,0
Exp/Cntr=0.3,0.1

Type RM Length L Ch R = 1 ,62102.9 ,54.1,53.6,47.3
XS GIS Cut Line= 4
     1879478.112      514292.535     1879335.459      514404.234
     1879227.201      514397.282     1879121.922      514464.819
#Sta/Elev= 30
       0  860.51     9.5  855.75    19.1  851.21    28.6  847.55    38.1  846.16
    76.3  843.52    85.8  843.17    95.4  843.06   114.4  843.11     143  842.86
   152.6  842.97   171.6  843.46   181.2   842.9   190.2   841.8   208.3  838.68
   217.3   838.1   262.5  838.17   271.6  838.87   280.6  840.01   289.7  840.83
   308.9  843.96   318.5  846.07   328.2  847.76   337.8   849.3   347.4  851.05
     357  853.47   366.6   855.7   376.3   857.8   395.5  861.62   414.7  865.12
#Mann= 3 , 0 , 0
       0      .1       0   208.3    .045       0   271.6      .1       0
#XS Ineff= 2 , 0
           121.1  847.02
Permanent Ineff=
       F       F
Bank Sta=208.3,271.6
XS Rating Curve= 0 ,0
Skew Angle= 45
Exp/Cntr=0.3,0.1

Type RM Length L Ch R = 1 ,62049.3 ,223.7,189.5,157.6
XS GIS Cut Line= 5
     1879449.677      514270.152     1879313.609      514376.424
      1879205.35      514369.472     1879115.357      514427.203
      1879100.12      514457.828
#Sta/Elev= 30
       0  862.54    19.2  852.88    28.8  849.04    38.4  847.22    67.1  845.21
    76.7  844.72   115.1  843.67   163.1  842.77   181.7  842.25   190.7  841.61
   208.8  839.46   217.8  838.54   226.9  838.04     245     838     254     838
     263  838.24   272.1   838.1   281.1  838.66   290.8  840.07   300.6  841.11
   310.3  841.45     320  841.29   329.7  840.91   339.4  840.88   349.2  841.08
   358.9  841.62   378.3  844.09     388  845.72   413.7  855.26   422.3  858.27
#Mann= 3 , 0 , 0
       0      .1       0   217.8    .045       0   281.1      .1       0
#XS Ineff= 2 , 0
          115.58   847.6
Permanent Ineff=
       F       F
Bank Sta=217.8,281.1
XS Rating Curve= 0 ,0
Skew Angle= 45
Exp/Cntr=0.3,0.1

Type RM Length L Ch R = 1 ,61859.8 ,260.8,227.6,194.3
XS GIS Cut Line= 4
     1879436.766        514014.9     1879170.588      514176.792
     1879058.357      514298.955     1879094.112      514510.506
#Sta/Elev= 30
       0  935.04    19.5  925.96    38.9  915.61    48.7  909.94    68.2  897.83
    97.4  878.98   116.8  867.44   126.6  862.52   136.3  859.35   175.2  854.86
   194.7   853.4   223.9  852.59   282.3  852.32   321.3  850.71   331.1  849.77
   340.8  848.18   350.6  846.07   370.1  840.58   379.8  838.41   389.6     838
   409.1  838.23   428.6  841.75   438.4  842.19     536  839.77   584.7  840.12
   594.5  840.34   604.2   841.1     614  843.65   623.7  847.98     692   882.9
#Mann= 3 , 0 , 0
       0      .1       0   379.8    .045       0   409.1      .1       0
Bank Sta=379.8,409.1
XS Rating Curve= 0 ,0
Exp/Cntr=0.3,0.1

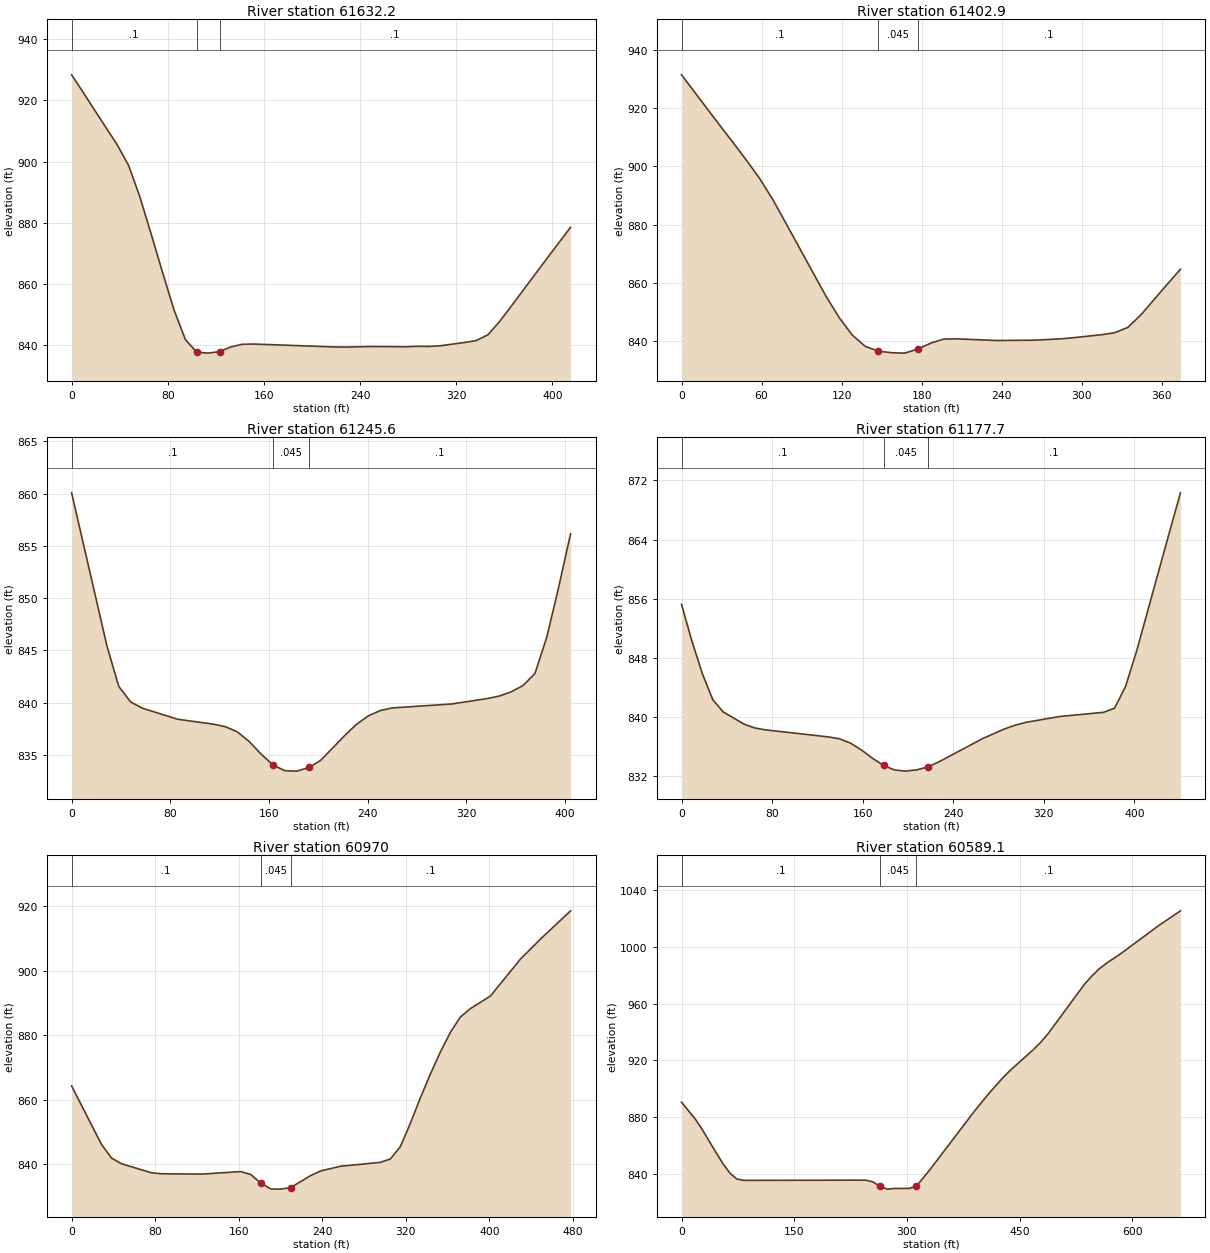
Type RM Length L Ch R = 1 ,61632.2 ,230.8,229.3,227.7
XS GIS Cut Line= 3
     1878849.151      514166.372     1878978.492      514317.413
      1879073.11      514511.858
#Sta/Elev= 30
       0  928.39     9.5  922.73    18.9  916.99    37.9  905.55    47.4   898.8
    56.8   888.5    66.3  876.18    75.8  863.63    85.2  851.54    94.7   841.8
   104.2  837.71   113.6  837.42   123.1  837.93   132.6  839.46     142  840.31
   151.5  840.39   218.5  839.44   228.3   839.4     248  839.58   277.5   839.5
   287.3  839.64   297.2  839.61     307  839.84   326.6  840.88   336.5  841.51
   346.3   843.4   356.1  847.76     366  852.89   395.4  868.34   415.1  878.55
#Mann= 3 , 0 , 0
       0      .1       0   104.2    .045       0   123.1      .1       0
Bank Sta=104.2,123.1
XS Rating Curve= 0 ,0
Exp/Cntr=0.3,0.1

Type RM Length L Ch R = 1 ,61402.9 ,183.4,157.3,132.1
XS GIS Cut Line= 2
     1878660.548      514309.766     1878922.398      514576.622
#Sta/Elev= 28
       0  931.47    29.5  913.62    39.4  907.74    49.2  901.77      59  895.53
    68.9   888.2    78.7  880.08   108.2  855.42   118.1  848.05   127.9  842.05
   137.7  838.13   147.6  836.49   157.4  835.95   167.3  835.81   177.1  837.22
   186.9  839.27   196.8  840.66   206.6  840.71   236.1  840.15   265.6  840.27
   285.3  840.76   295.2  841.18   314.8  842.14   324.7  842.83   334.5  844.67
   344.4  849.04     364  859.48   373.9  864.66
#Mann= 3 , 0 , 0
       0      .1       0   147.6    .045       0   177.1      .1       0
Bank Sta=147.6,177.1
XS Rating Curve= 0 ,0
Exp/Cntr=0.3,0.1

Type RM Length L Ch R = 1 ,61245.6 ,70.8,67.9,65.4
XS GIS Cut Line= 4
     1878502.188      514495.001     1878570.198      514547.612
     1878781.928      514529.647     1878865.337      514595.091
#Sta/Elev= 30
       0  860.07    28.7   845.4    38.2  841.57    47.8  840.08    57.3  839.48
      86  838.42     115  837.95   124.6  837.71   134.3  837.22   143.9   836.3
   153.6  835.09   163.2  834.05   172.9   833.5   182.6  833.46   192.7833.8167
   201.9  834.49   221.2  836.84   230.9  837.93   240.5  838.74   250.2  839.25
   259.8   839.5   308.1  839.88     337   840.4   346.7  840.64   356.3  841.04
   365.9  841.64   375.6  842.79   385.2  846.26   394.9  851.07   404.5  856.16
#Mann= 3 , 0 , 0
       0      .1       0   163.2    .045       0   192.7      .1       0
Bank Sta=163.2,192.7
XS Rating Curve= 0 ,0
Exp/Cntr=0.3,0.1

Type RM Length L Ch R = 1 ,61177.7 ,168.2,207.7,245.8
XS GIS Cut Line= 4
     1878448.419      514517.587     1878539.527      514595.863
      1878752.54      514575.332     1878834.666      514643.342
#Sta/Elev= 30
       0  855.24     9.2  850.26    18.5  845.82    27.7  842.32      37  840.66
    55.4  839.02    64.7  838.51    73.9  838.26   129.8   837.3   139.6  837.04
   149.3  836.46     159  835.53   168.8   834.4   178.5  833.44   188.2  832.83
   197.9  832.67   207.8  832.84   217.4  833.23   227.1   833.9     266  837.07
   285.5  838.39   295.2  838.91   304.9  839.29   334.1  840.06   372.9  840.63
   382.6  841.19   392.3  844.13     402  848.88     431  864.97   440.8  870.33
#Mann= 3 , 0 , 0
       0      .1       0   178.5    .045       0   217.4      .1       0
Bank Sta=178.5,217.4
XS Rating Curve= 0 ,0
Exp/Cntr=0.3,0.1

Type RM Length L Ch R = 1 ,60970   ,371,380.9,390.8
XS GIS Cut Line= 3
     1878387.407      514512.256       1878472.1      514775.315
     1878635.068       514893.37
#Sta/Elev= 30
       0  864.23    28.6  846.08    38.1  841.87    47.6  840.08    76.2  837.28
    85.8  836.95   123.9  836.84     162  837.63   171.5  836.73   181.1  834.03
   190.6  832.24   200.1  832.18   209.6  832.65   228.7  836.37   238.2  837.81
   257.3  839.28   295.5  840.49   305.1  841.55   314.7   845.4   324.3  852.67
   333.8  860.51   343.4  867.93     353  874.79   362.6  880.91   372.2  885.69
   381.8  888.28   400.9  892.18   429.7  903.67   448.8  909.86   477.6  918.64
#Mann= 3 , 0 , 0
       0      .1       0   181.1    .045       0   209.6      .1       0
Bank Sta=181.1,209.6
XS Rating Curve= 0 ,0
Exp/Cntr=0.3,0.1

Type RM Length L Ch R = 1 ,60589.1 ,300.9,324.7,348.4
XS GIS Cut Line= 4
     1878135.908        514459.8     1878090.157      514590.797
     1878050.758      514897.418     1878020.457      515111.709
#Sta/Elev= 30
       0  890.68    18.5  878.68    27.8  871.29    46.2  855.05    55.5  847.23
    64.8  840.54      74  836.58    83.2   835.7     245  835.88   254.7  834.65
   264.4  831.51     274  829.55   283.7  830.01     303  830.05   312.6  831.48
     332   844.1   389.9   884.3   409.3  896.88   428.6  908.33   438.2  913.32
   467.6  927.22   477.4  932.33   487.2  938.23   536.4   973.5   546.3  979.37
   556.1  984.41     566  988.43   585.6  995.42   634.8 1014.68   664.3 1025.21
#Mann= 3 , 0 , 0
       0      .1       0   264.4    .045       0   312.6      .1       0
Bank Sta=264.4,312.6
XS Rating Curve= 0 ,0
Exp/Cntr=0.3,0.1

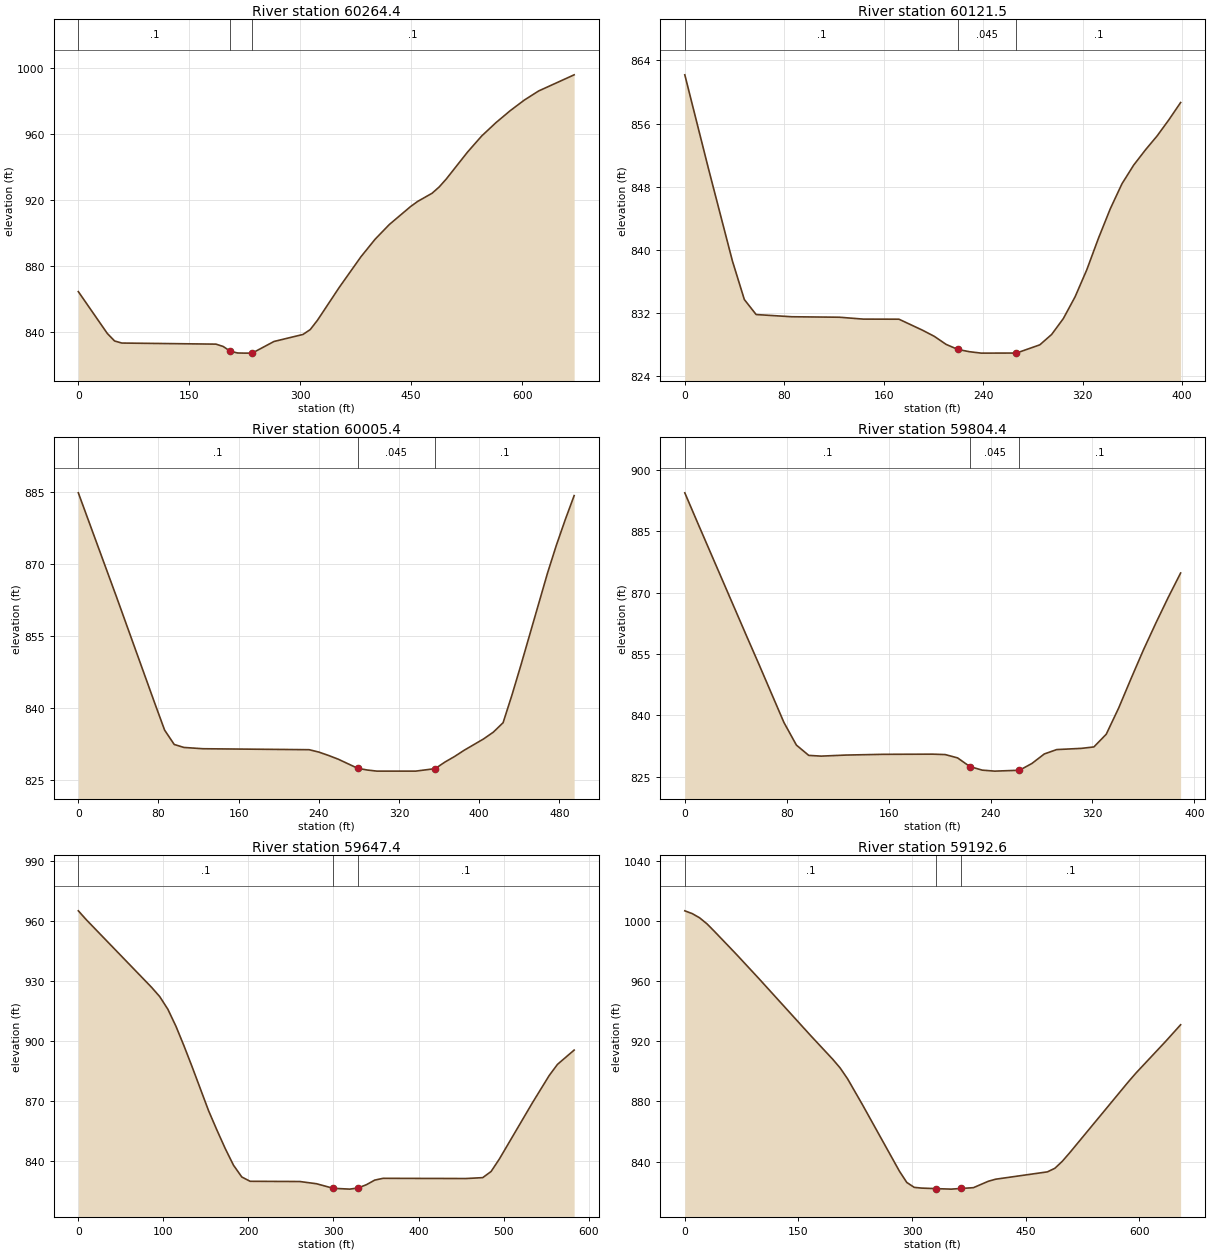
Type RM Length L Ch R = 1 ,60264.4 ,98.2,142.9,182.2
XS GIS Cut Line= 3
     1878062.792      514438.934     1877710.362      514586.503
     1877463.834      514735.809
#Sta/Elev= 30
       0  864.68    39.2  839.31      49  834.77    58.8  833.51   186.1  832.85
   195.9  831.42   205.7  828.46   215.5  827.48   225.3   827.4   235.1  827.42
   264.5  834.46   303.7  838.72   313.5  841.67   323.3  847.33   352.7  867.22
   382.1  885.84   401.3  896.49   420.5  905.38   449.3   916.3   458.9   919.4
   478.2   924.3   487.8   928.1   497.4  932.94   526.2  949.29   545.4  959.07
   564.6  967.12   583.8  974.34     603  980.81   622.3  986.31   670.3   996.1
#Mann= 3 , 0 , 0
       0      .1       0   205.7    .045       0   235.1      .1       0
Bank Sta=205.7,235.1
XS Rating Curve= 0 ,0
Exp/Cntr=0.3,0.1

Type RM Length L Ch R = 1 ,60121.5 ,122.9,116.1,114.6
XS GIS Cut Line= 3
     1878007.237      514367.753     1877837.098      514431.989
     1877663.487      514301.781
#Sta/Elev= 29
       0  862.17    19.1  850.24    38.3  838.58    47.9  833.69    57.4  831.79
    86.1  831.51   124.4  831.45   143.6  831.21   172.3   831.2   191.3   829.8
   200.7  829.03   210.2  828.01   219.6  827.37     229  827.08   238.5   826.9
   266.8  826.91   285.6  827.95   295.1  829.26   304.5  831.27     314  834.04
   323.4  837.46   332.8  841.46   342.3  845.19   351.7  848.36   361.1  850.72
   370.6  852.66     380  854.43   389.4  856.46   398.9  858.66
#Mann= 3 , 0 , 0
       0      .1       0   219.6    .045       0   266.8      .1       0
Bank Sta=219.6,266.8
XS Rating Curve= 0 ,0
Skew Angle= 55
Exp/Cntr=0.3,0.1

Type RM Length L Ch R = 1 ,60005.4 ,239.5,200.9,162.4
XS GIS Cut Line= 4
     1878015.917      514300.045     1877845.779      514364.281
     1877649.795      514222.309      1877581.89      514242.753
#Sta/Elev= 28
       0  884.82    38.3  863.04    76.6  840.85    86.1  835.44    95.7  832.45
   105.3  831.83   124.4  831.56   230.3  831.36   239.9  830.87   249.6  830.17
   259.3  829.39   278.7   827.5   288.3  827.13   297.9   826.9   336.7   826.9
   356.1  827.42   365.8  828.78   375.5  829.95   385.1  831.25   404.5  833.61
   414.2  835.02   423.9  836.98   432.7  842.71   441.6  848.91   468.2   868.1
     477  873.88   485.9  879.22   494.8  884.24
#Mann= 3 , 0 , 0
       0      .1       0   278.7    .045       0   356.1      .1       0
Bank Sta=278.7,356.1
XS Rating Curve= 0 ,0
Skew Angle= 55
Exp/Cntr=0.3,0.1

Type RM Length L Ch R = 1 ,59804.4 ,151.5,157.1,162.6
XS GIS Cut Line= 2
     1877899.598      514001.434     1877545.431      514162.892
#Sta/Elev= 29
       0  894.44     9.7  887.37    48.6  859.33    58.4  852.34    77.8  838.26
    87.6  832.72    97.3   830.2     107  830.02   126.5  830.28   155.7  830.46
   194.6   830.5   204.4   830.4   214.1  829.59   223.8  827.46   233.5  826.59
   243.3  826.35   262.7  826.56   272.5  828.23   282.2  830.55   291.9  831.62
   311.4  831.92   321.1  832.27   330.8  835.37   340.6  841.81   350.3     849
     360     856   369.8   862.6   379.5  868.87   389.2  874.82
#Mann= 3 , 0 , 0
       0      .1       0   223.8    .045       0   262.7      .1       0
Bank Sta=223.8,262.7
XS Rating Curve= 0 ,0
Exp/Cntr=0.3,0.1

Type RM Length L Ch R = 1 ,59647.4 ,470.2,454.8,439.4
XS GIS Cut Line= 4
     1877950.548      513841.785     1877818.169      513918.825
     1877558.838      513966.568     1877419.949      514057.714
#Sta/Elev= 30
       0  965.03     9.6  960.48    86.2  926.73    95.7  922.12   105.3  915.78
   114.9  907.17   124.4   897.3     134  886.78   153.2  864.99   162.9   855.4
   172.7  846.14   182.5  837.74   192.2  831.89     202  829.73   260.6  829.61
   280.1   828.5   299.7  826.22   319.2  825.81     329   826.4   338.7  828.02
   348.5  830.32   358.3  831.21   455.9  831.11   475.5  831.56   485.3  834.62
     495  840.83   534.1  869.12   553.7  882.66   563.4  888.22     583  895.37
#Mann= 3 , 0 , 0
       0      .1       0   299.7    .045       0     329      .1       0
Bank Sta=299.7,329
XS Rating Curve= 0 ,0
Exp/Cntr=0.3,0.1

Type RM Length L Ch R = 1 ,59192.6 ,295.6,299,302.4
XS GIS Cut Line= 2
     1877583.772      513386.984      1877151.48      513878.304
#Sta/Elev= 30
       0 1006.74     9.8 1004.89    19.5 1002.11    29.3  998.07    39.1  993.08
    68.4  977.66    97.7  961.74     166  923.85   195.4  907.96   205.1  902.21
   214.9  894.99   234.4   877.9   283.3   833.6     293  826.13   302.8  822.88
   312.6  822.38   332.1  822.02   351.6   821.7   364.8822.1436   380.9  822.66
   400.5  826.91   410.2  828.29   478.6  833.18   488.4  835.55   498.1  840.14
   507.9  845.81     586   893.4   595.8  899.06   634.9  920.08   654.4  930.98
#Mann= 3 , 0 , 0
       0      .1       0   332.1    .045       0   364.8      .1       0
Bank Sta=332.1,364.8
XS Rating Curve= 0 ,0
Exp/Cntr=0.3,0.1

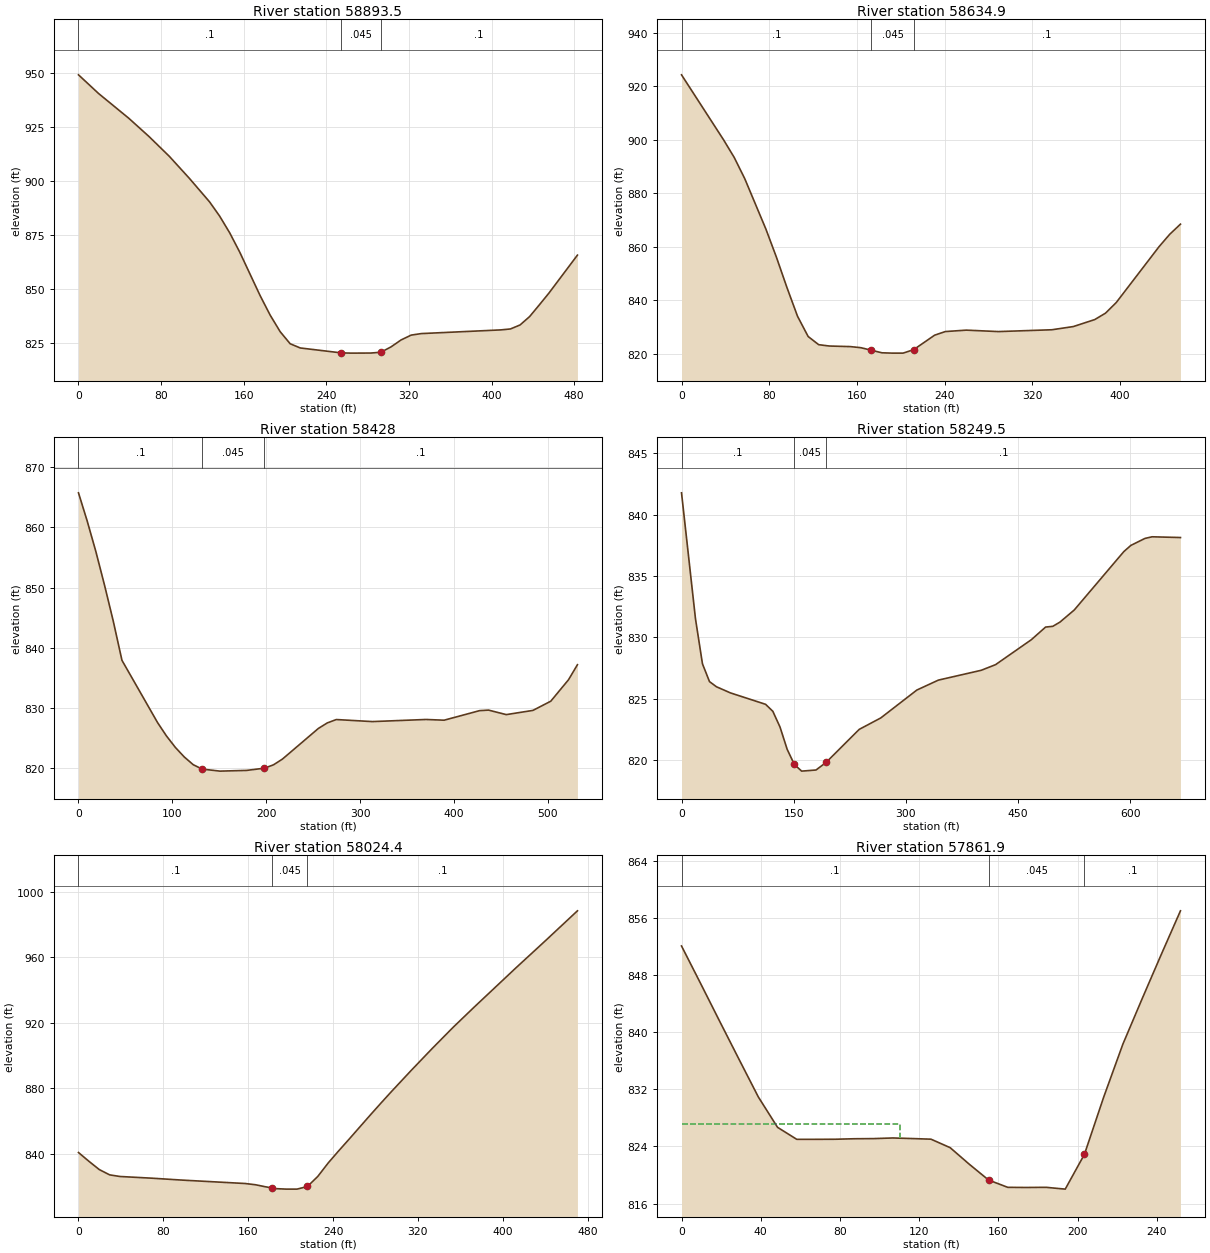
Type RM Length L Ch R = 1 ,58893.5 ,268.4,258.6,248.8
XS GIS Cut Line= 3
     1877340.716      513284.554     1877042.105       513536.29
      1876995.23      513616.151
#Sta/Elev= 30
       0  949.19    19.5  940.52    48.8  929.04    68.4  920.57    87.9  911.48
   107.4  901.24   126.9  890.38   136.7  883.76   146.5  875.96   156.2  867.03
   175.8  847.04   185.5  838.01   195.3  830.24     205  824.64   214.8  822.69
   253.9  820.44   263.6   820.3   283.2  820.34   292.9  820.72   302.7   823.2
   312.4   826.4   322.2  828.65     332  829.35   409.1  831.06   418.3  831.49
   427.6  833.33   436.9  837.23   446.1  842.53   455.4  847.98   483.2  865.69
#Mann= 3 , 0 , 0
       0      .1       0   253.9    .045       0   292.9      .1       0
Bank Sta=253.9,292.9
XS Rating Curve= 0 ,0
Exp/Cntr=0.3,0.1

Type RM Length L Ch R = 1 ,58634.9 ,254.8,206.9,158.1
XS GIS Cut Line= 3
     1877004.055      513129.678     1876890.123      513373.819
     1876860.826      513557.196
#Sta/Elev= 30
       0  924.31    38.5   899.9    48.1  893.38    57.7  885.45      77  866.57
    86.6  856.05    96.2   844.7   105.8  834.01   115.5  826.42   125.1  823.36
   134.7  822.86     154  822.64   163.6  822.23   173.2  821.28   182.8  820.32
   192.4   820.2   202.1   820.2   211.7  821.49   230.9  826.92   240.6  828.27
   259.8   828.8     289  828.26   337.8  828.94   357.4  830.14   376.9  832.75
   386.7  835.14   396.5  839.11   435.6  860.04   445.3  864.65   455.1  868.45
#Mann= 3 , 0 , 0
       0      .1       0   173.2    .045       0   211.7      .1       0
Bank Sta=173.2,211.7
XS Rating Curve= 0 ,0
Exp/Cntr=0.3,0.1

Type RM Length L Ch R = 1 ,58428   ,160.1,178.6,197.1
XS GIS Cut Line= 5
     1876732.858      513024.132     1876704.744      513060.877
     1876770.384      513197.804     1876822.467      513381.832
     1876810.315      513523.325
#Sta/Elev= 30
       0  865.76     9.2  861.11    18.5     856    27.8  850.36      37  844.45
    46.3   837.9    84.2  827.55    93.7  825.32   103.2  823.41   112.7  821.82
   122.2  820.54   131.7  819.81   150.7  819.47   179.1  819.59   198.1  819.96
   207.7  820.52   217.2  821.47   255.5  826.57     265  827.49   274.6  828.05
   312.9  827.71   370.2  828.06   389.4  827.94   427.2  829.53   436.7  829.62
   455.6  828.87     484  829.57     503   831.1   521.9  834.67   531.4  837.17
#Mann= 3 , 0 , 0
       0      .1       0   131.7    .045       0   198.1      .1       0
Bank Sta=131.7,198.1
XS Rating Curve= 0 ,0
Skew Angle= 45
Exp/Cntr=0.3,0.1

Type RM Length L Ch R = 1 ,58249.5 ,170.8,225,279.7
XS GIS Cut Line= 5
     1876669.768      512961.515     1876578.418      513008.688
     1876679.969      513216.156     1876732.053      513400.184
       1876719.9      513541.677
#Sta/Elev= 30
       0  841.77    18.7   831.5      28  827.85    37.4   826.4    46.7  825.98
    65.4  825.48   112.4  824.55   122.1  823.98   131.7   822.7   141.3  820.88
   150.9  819.65   160.6  819.11   179.8   819.2   193.3  819.82   237.6  822.51
   266.4  823.44   314.6  825.71   343.4  826.52   400.7  827.32   419.9  827.78
   467.7  829.81   486.8  830.84   496.4   830.9   505.9  831.24   525.1  832.23
   591.3  836.98   600.8  837.49   619.7  838.06   629.2  838.19   667.1  838.13
#Mann= 3 , 0 , 0
       0      .1       0   150.9    .045       0   193.3      .1       0
Bank Sta=150.9,193.3
XS Rating Curve= 0 ,0
Skew Angle= 45
Exp/Cntr=0.3,0.1

Type RM Length L Ch R = 1 ,58024.4 ,163.9,162.6,161.3
XS GIS Cut Line= 3
     1876661.165      512934.557     1876396.506      512946.994
     1876194.683      512986.057
#Sta/Elev= 29
       0  840.76     9.8  835.42    19.6  830.35    29.4   827.1    39.2  826.11
    68.7  825.09    98.1  823.89     157  821.83   166.8  821.07   176.6  819.79
   182.7819.0948   186.4  818.67   196.3  818.39   206.1   818.4   215.9     820
   225.7  826.18   235.5  834.39   245.3  841.73   255.1  848.85   274.7  863.33
   284.5  870.44   294.3  877.43   313.9  891.03   333.5  904.28     353  917.08
   372.6  929.28   411.8  953.16   441.2  970.71   470.5  988.44
#Mann= 3 , 0 , 0
       0      .1       0   182.7    .045       0   215.9      .1       0
Bank Sta=182.7,215.9
XS Rating Curve= 0 ,0
Exp/Cntr=0.3,0.1

Type RM Length L Ch R = 1 ,57861.9 ,151.8,170.3,189.5
XS GIS Cut Line= 2
     1876640.557       512764.01     1876389.906      512790.052
#Sta/Elev= 29
       0  852.06     9.7  846.78    19.4  841.45    29.1  836.17    38.8  830.93
    48.5  826.68    58.2     825    67.8     825    77.5  825.01    87.2  825.08
    96.9   825.1   106.6  825.19   116.3  825.11     126  825.02   135.7  823.83
   145.4   821.5   155.1   819.3   162.6  818.51   164.8  818.28   174.5  818.26
   177.6  818.27   184.2  818.28   193.8  818.03   203.5   822.9   213.2  830.89
   222.9  838.31   232.6  844.65   242.3  850.87     252  856.98
#Mann= 3 , 0 , 0
       0      .1       0   155.1    .045       0   203.5      .1       0
#XS Ineff= 2 , 0
          110.57  827.12
Permanent Ineff=
       F       F
Bank Sta=155.1,203.5
XS Rating Curve= 0 ,0
Exp/Cntr=0.3,0.1