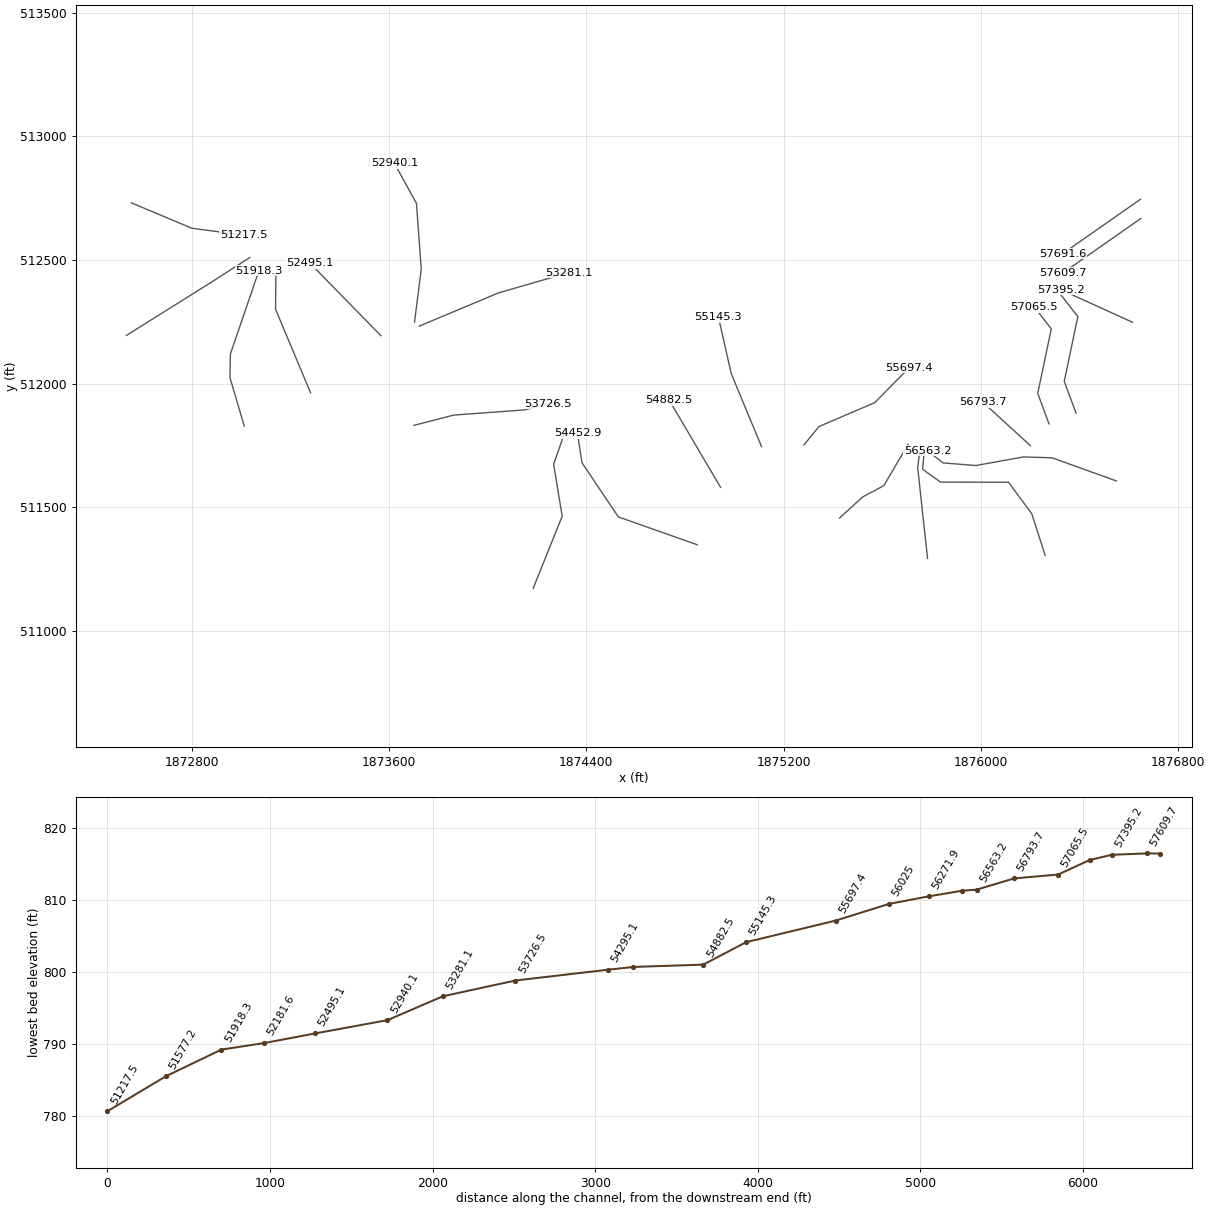
HEC-RAS study FALLINGRCR.prj: FALLINGRCR

--- FALLINGRCR.g01 (geometry) --- (continued)

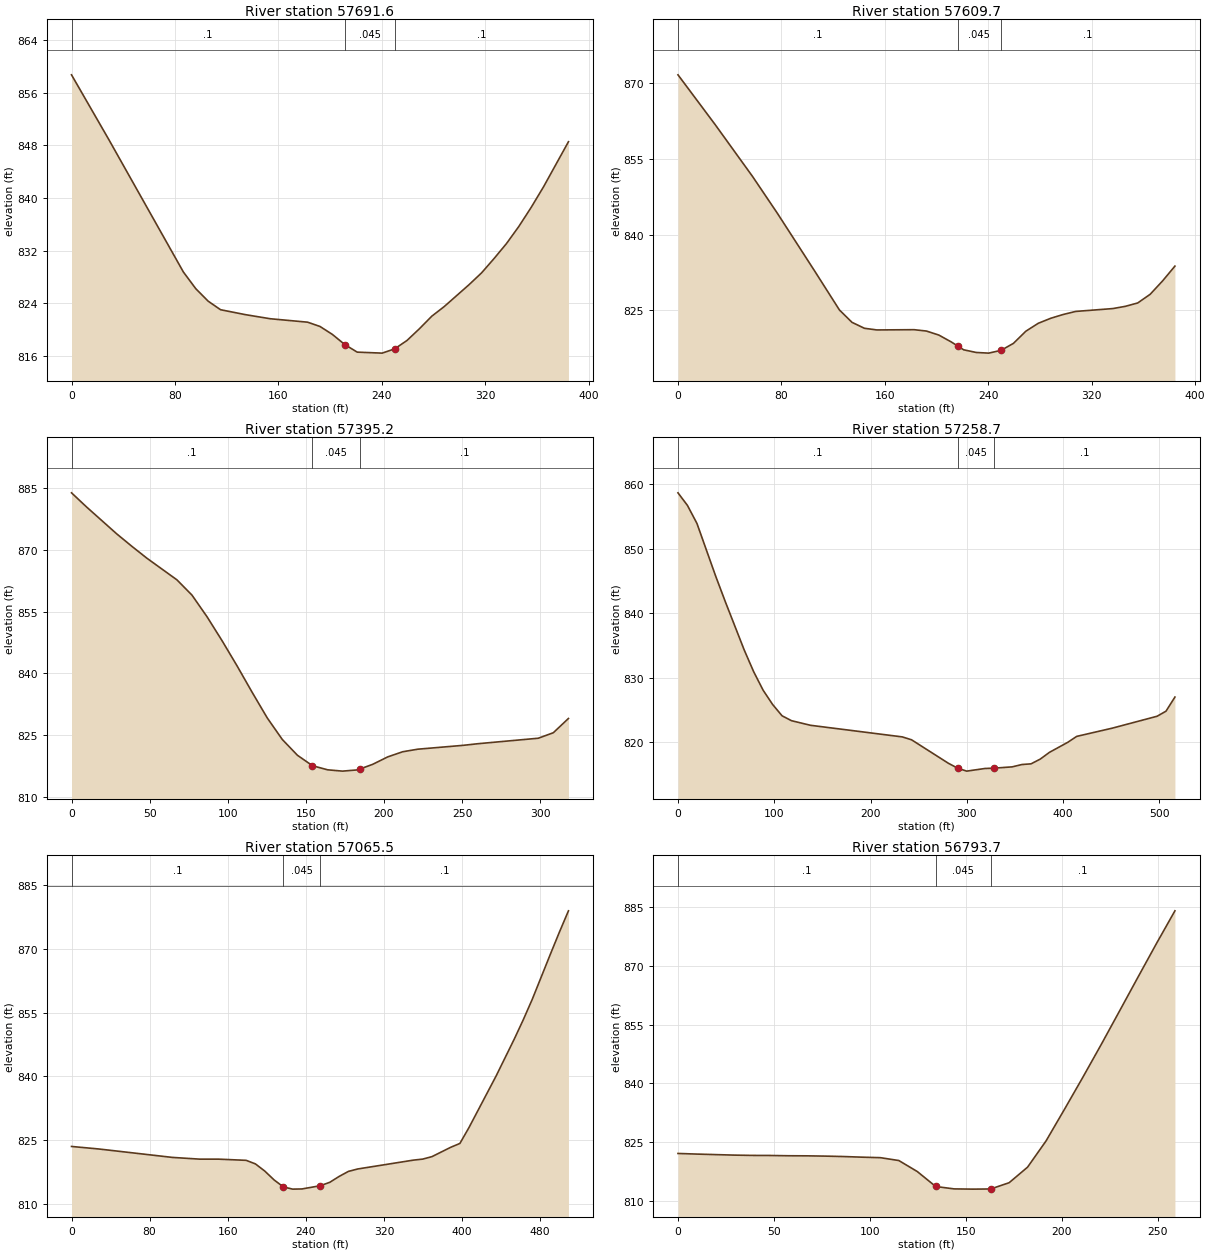
Type RM Length L Ch R = 1 ,57691.6 ,83.8,81.9,79.1
XS GIS Cut Line= 2
     1876647.495      512745.566     1876332.087      512525.769
#Sta/Elev= 27
       0  858.72    28.8  848.91    86.5  828.79    96.1  826.25   105.7  824.35
   115.3  823.05   134.6   822.3   153.8  821.68   182.6  821.16   192.2  820.51
   201.8   819.3   211.4  817.76     221  816.61   240.3  816.46   249.9   817.1
   259.5  818.38   269.1  820.16   278.7  822.07   288.3  823.53   307.6  826.87
   317.2  828.65   326.8  830.81   336.4  833.08     346  835.69   355.6   838.6
   365.2  841.74   384.4  848.56
#Mann= 3 , 0 , 0
       0      .1       0   211.4    .045       0   249.9      .1       0
Bank Sta=211.4,249.9
XS Rating Curve= 0 ,0
Skew Angle= 30
Exp/Cntr=0.3,0.1

Type RM Length L Ch R = 1 ,57609.7 ,238.3,214.5,190.8
XS GIS Cut Line= 2
      1876648.86      512667.845     1876333.452      512448.049
#Sta/Elev= 30
       0  871.69    28.8   861.8    57.7  851.52    76.9  844.22   105.7  832.78
   124.9  825.04   134.6  822.59   144.2  821.41   153.8  821.08   182.6  821.13
   192.2  820.86   201.8  820.06   211.4   818.7  216.42817.8843     221  817.14
   230.7  816.61   240.3  816.48   249.9  817.03   259.5  818.42   269.1  820.83
   278.7   822.4   288.3  823.39   297.9  824.14   307.6  824.75   336.4  825.32
     346  825.76   355.6  826.43   365.2  828.14   374.8  830.79   384.4  833.74
#Mann= 3 , 0 , 0
       0      .1       0  216.42    .045       0   249.9      .1       0
Bank Sta=216.42,249.9
XS Rating Curve= 0 ,0
Skew Angle= 30
Exp/Cntr=0.3,0.1

Type RM Length L Ch R = 1 ,57395.2 ,199.6,136.4,82.5
XS GIS Cut Line= 2
     1876614.515      512248.602     1876324.802      512379.895
#Sta/Elev= 28
       0  883.78     9.6  880.36    28.9  873.84    38.6  870.82    48.2  867.94
    67.5  862.67    77.1  858.98    86.8   853.7    96.4   847.9     106   841.8
   115.7  835.36   125.3  829.19   134.9  823.98   144.6  820.14   154.2  817.61
   163.9  816.61   173.5  816.29   183.1  816.59   184.8816.8267   192.8  817.94
   202.4  819.74     212  820.99   221.7  821.61   250.6  822.54   260.2  822.94
   298.8  824.27   308.4   825.6   318.1  829.06
#Mann= 3 , 0 , 0
       0      .1       0   154.2    .045       0   184.8      .1       0
Bank Sta=154.2,184.8
XS Rating Curve= 0 ,0
Exp/Cntr=0.3,0.1

Type RM Length L Ch R = 1 ,57258.7 ,167.3,193.2,209.6
XS GIS Cut Line= 4
     1876386.203      511880.781      1876338.24      512009.742
     1876393.325      512271.258     1876324.738      512358.862
#Sta/Elev= 30
       0  858.66     9.8  856.72    19.7  853.92    39.3   845.7    49.1  841.82
    68.8  834.32    78.6  830.96    88.4   828.1    98.3  825.88   108.1  824.13
   117.9  823.37   137.6  822.66     233  820.86   242.6  820.41   280.8  816.78
   290.3  816.03   299.8  815.56   318.9  815.97   328.5  816.02   347.1  816.22
   357.1  816.58   366.7  816.69   376.2  817.42   385.8  818.47   404.8  820.02
   414.1  820.94   451.2  822.22   497.6  824.06   506.8  824.84   516.1  827.03
#Mann= 3 , 0 , 0
       0      .1       0   290.3    .045       0   328.5      .1       0
Bank Sta=290.3,328.5
XS Rating Curve= 0 ,0
Skew Angle= 50
Exp/Cntr=0.3,0.1

Type RM Length L Ch R = 1 ,57065.5 ,241.4,271.8,302
XS GIS Cut Line= 4
     1876276.305       511837.92     1876230.714      511961.118
     1876285.624      512221.804     1876217.038      512309.407
#Sta/Elev= 30
       0  823.56    28.2  822.96   103.2  820.99   131.4  820.58   150.4  820.58
   178.9   820.3   188.4  819.46     198  817.77   207.5   815.7     217  814.06
   226.5  813.54     236  813.58     255  814.35   264.6  815.15   274.1  816.52
   283.6   817.7   293.1  818.27   350.2  820.35   359.7  820.59   369.2  821.17
   388.2  823.34   397.8  824.27     407  827.95   434.9  840.11   453.4  848.73
   462.7   853.3   471.9   858.1   490.5  868.72   499.8  873.93     509  878.89
#Mann= 3 , 0 , 0
       0      .1       0     217    .045       0     255      .1       0
Bank Sta=217,255
XS Rating Curve= 0 ,0
Skew Angle= 50
Exp/Cntr=0.3,0.1

Type RM Length L Ch R = 1 ,56793.7 ,215,230.4,247.2
XS GIS Cut Line= 2
     1876200.846      511749.765     1876009.575      511924.323
#Sta/Elev= 30
       0  822.11     9.6  821.95    19.2  821.82    28.8  821.69    38.4  821.61
      48  821.59    57.5  821.52    67.1   821.5    76.7  821.43    86.3  821.32
    95.9  821.16   105.5  821.03   115.1   820.3   124.7   817.5   134.3  813.68
   139.2  813.36   143.9  813.06   153.4     813   154.2     813     163  813.04
   172.6  814.64   182.2  818.61   191.8  825.28   201.4  833.35     211  841.55
   220.6  849.94   230.2  858.54   239.8  867.17   249.4  875.73     259  884.06
#Mann= 3 , 0 , 0
       0      .1       0   134.3    .045       0     163      .1       0
Bank Sta=134.3,163
XS Rating Curve= 0 ,0
Exp/Cntr=0.3,0.1

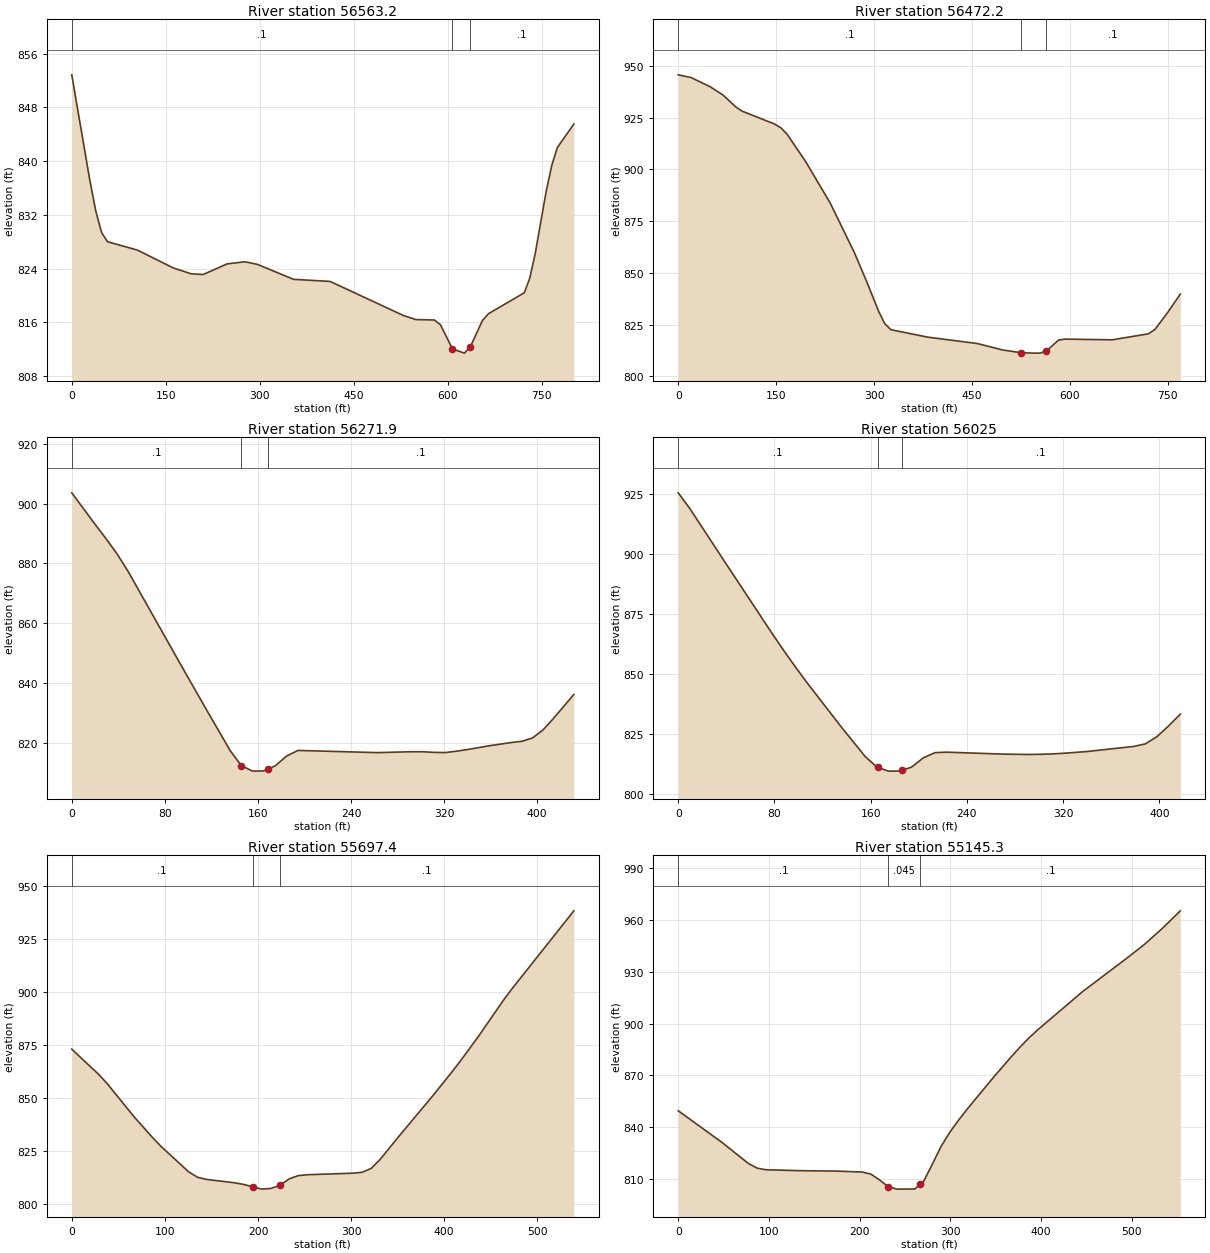
Type RM Length L Ch R = 1 ,56563.2 ,90.4,91,90.3
XS GIS Cut Line= 6
     1876549.411      511607.326     1876288.995      511700.642
     1876172.817      511704.314      1875980.06      511669.611
     1875846.726      511680.028     1875784.437      511728.854
#Sta/Elev= 30
       0  852.85    28.6  837.29    38.2  832.64    47.7  829.35    57.2  828.01
   104.9  826.77   162.2  824.11   190.8  823.24   209.9  823.14     248  824.72
   276.6  825.03     296  824.66   354.1  822.42   412.4  822.11     530  817.02
   549.6  816.43   578.9  816.37   588.7  815.66   607.8  812.06   626.9  811.44
   636.5  812.41   655.6  816.28   665.2   817.3   722.5  820.42   731.3  822.61
     740   826.3   757.6  835.59   766.4  839.38   775.2  842.02   801.6  845.53
#Mann= 3 , 0 , 0
       0      .1       0   607.8    .045       0   636.5      .1       0
Bank Sta=607.8,636.5
XS Rating Curve= 0 ,0
Exp/Cntr=0.3,0.1

Type RM Length L Ch R = 1 ,56472.2 ,232.9,200.3,167.7
XS GIS Cut Line= 6
     1876260.783      511306.762     1876206.461      511474.897
     1876112.118       511602.05     1875836.726      511602.319
     1875763.859      511654.503     1875769.912      511722.524
#Sta/Elev= 30
       0   945.6    19.6   944.3    49.1  939.82    68.7  935.83    88.4  930.05
    98.2  928.02   147.2  921.91   157.1  920.08   166.9  916.87   195.3  903.65
   232.6  883.84   269.8  859.81   288.5  845.94   307.1  831.37   316.4  825.51
   325.7  822.58   382.5  818.98   458.4   815.9   496.6  812.82   525.2  811.47
   544.3  811.28   553.9  811.28   563.4  812.14   582.5  817.56   592.1  818.04
     665  817.71   720.3   820.6   730.1  822.69   749.6  830.81   769.1  839.77
#Mann= 3 , 0 , 0
       0      .1       0   525.2    .045       0   563.4      .1       0
Bank Sta=525.2,563.4
XS Rating Curve= 0 ,0
Exp/Cntr=0.3,0.1

Type RM Length L Ch R = 1 ,56271.9 ,273.9,246.9,219.6
XS GIS Cut Line= 3
     1875783.801      511294.572     1875743.871       511661.76
     1875751.683      511723.392
#Sta/Elev= 29
       0   903.6    19.4   893.4    29.2  888.41    38.9  883.19    48.6   877.2
    97.2  843.69   116.6   830.5   136.1  817.41   145.8  812.31   155.5  810.52
   165.2   810.6   168.3811.1475     175  812.32   184.7  815.58   194.4  817.44
   262.4  816.71   291.6     817   301.3     817     311   816.8   320.8  816.72
   330.5  817.18   340.2  817.75   359.6  819.05   378.2  820.11   387.1  820.52
     396  821.62   404.8  824.23   413.7     828   431.5  836.18
#Mann= 3 , 0 , 0
       0      .1       0   145.8    .045       0   168.3      .1       0
Bank Sta=145.8,168.3
XS Rating Curve= 0 ,0
Exp/Cntr=0.3,0.1

Type RM Length L Ch R = 1 ,56025   ,329.4,327.5,325.6
XS GIS Cut Line= 4
     1875427.378      511457.574     1875520.703      511542.616
     1875606.297      511587.897     1875705.144       511755.22
#Sta/Elev= 29
       0  925.66     9.7  919.05    38.8  896.76    77.7  867.21    87.4  860.03
    97.1  853.19   106.8  846.55   135.9  827.68   155.3  815.63     165  811.19
   165.7811.0653   174.7  809.46   184.4  809.51   185.7809.7321     194  811.15
   203.7  814.98   213.4  817.18   223.1  817.38   271.7  816.54   291.1  816.42
   300.8  816.48   310.6  816.64   320.3  816.91   339.7  817.64   378.6  819.77
   388.3  820.82     398  823.86   407.7  828.36   417.4  833.28
#Mann= 3 , 0 , 0
       0      .1       0   165.7    .045       0   185.7      .1       0
Bank Sta=165.7,185.7
XS Rating Curve= 0 ,0
Exp/Cntr=0.3,0.1

Type RM Length L Ch R = 1 ,55697.4 ,516.6,552.2,587.7
XS GIS Cut Line= 4
     1875282.864      511752.896     1875343.791      511827.133
     1875569.316      511923.428     1875708.754      512063.969
#Sta/Elev= 30
       0  873.08    28.8  861.24    38.4  856.66    67.2  841.08    86.4  831.62
      96  827.21   125.5   815.3   135.3  812.69   145.1  811.69   174.5  810.15
   184.3  809.39   194.1  808.28   203.9  807.14   213.7  807.46   223.6   808.9
   233.4  811.96   243.2   813.5     253  813.92     302  814.65   311.8  815.06
   321.6  816.91   331.4  821.24   350.7  831.69   388.4  851.48   407.2  861.76
   416.7  867.12   435.5  878.33   463.8  896.28   473.2  901.75   539.2  938.26
#Mann= 3 , 0 , 0
       0      .1       0   194.1    .045       0   223.6      .1       0
Bank Sta=194.1,223.6
XS Rating Curve= 0 ,0
Exp/Cntr=0.3,0.1

Type RM Length L Ch R = 1 ,55145.3 ,259.7,262.8,265.9
XS GIS Cut Line= 3
     1875110.609      511746.215     1874987.996      512040.269
     1874935.913      512269.218
#Sta/Elev= 30
       0  849.51    48.3  831.15    77.2  819.04    86.9   816.3    96.5  815.35
   135.2   814.8   173.8  814.58   202.7  814.04   212.4   812.8     222  809.45
   231.7  805.38   241.4  804.13   260.7   804.2   266.7806.8706   270.3  808.47
     280  818.48   289.6  828.76   299.3  837.03   308.9  843.99   318.6  850.52
   347.9  869.14   367.5  881.02   377.3   886.7   387.1  891.95   396.9  896.65
   445.8  918.53   494.7  937.93   514.3  946.02   533.8  955.18   553.4  965.26
#Mann= 3 , 0 , 0
       0      .1       0   231.7    .045       0   266.7      .1       0
Bank Sta=231.7,266.7
XS Rating Curve= 0 ,0
Exp/Cntr=0.3,0.1

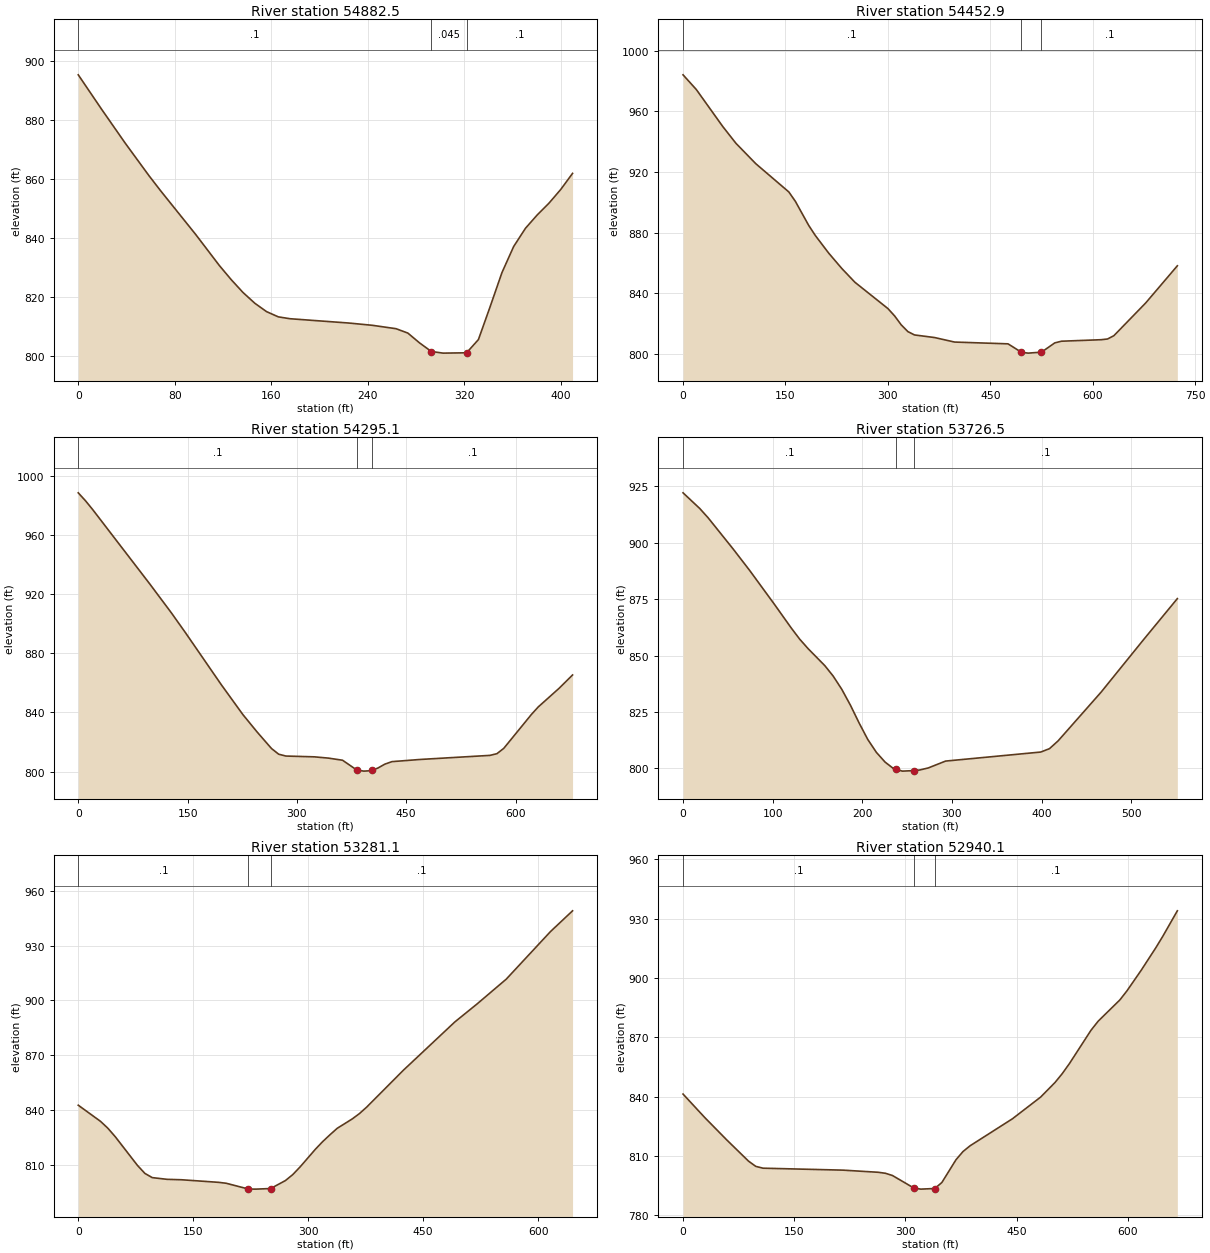
Type RM Length L Ch R = 1 ,54882.5 ,428.3,429.6,430.9
XS GIS Cut Line= 2
     1874944.593      511581.284      1874736.26      511933.932
#Sta/Elev= 30
       0  895.19    19.5  883.45      39  872.02    58.5  861.12    68.3  855.93
    97.5  841.07     117  830.62   126.8  825.85   136.5  821.54   146.3  817.89
     156  815.06   165.8  813.28   175.5  812.65   224.3  811.19   243.8  810.42
   263.3  809.28   273.1   807.8   282.8  804.48   292.6  801.56   302.3  801.01
   321.8  801.12   331.6   805.6   341.3  816.72   351.1  828.26   360.8  837.09
   370.6  843.27   380.3  847.76   390.1  851.77   399.8  856.39   409.6  861.84
#Mann= 3 , 0 , 0
       0      .1       0   292.6    .045       0   321.8      .1       0
Bank Sta=292.6,321.8
XS Rating Curve= 0 ,0
Exp/Cntr=0.3,0.1

Type RM Length L Ch R = 1 ,54452.9 ,167.5,157.8,148.1
XS GIS Cut Line= 4
     1874849.888       511349.46     1874530.097      511461.927
     1874382.527      511681.111     1874364.081      511800.468
#Sta/Elev= 30
       0  984.04    19.4  974.38    58.1  950.03    77.5  938.92   106.5  925.51
     155  906.86   164.6  900.64     184  884.88   193.7  878.22   213.1  866.71
   232.4  856.52   251.8  847.36   300.2     830   309.9   825.2   319.6   819.3
   329.3  814.88     339  812.67   368.4  810.96   397.7  807.98     476  806.81
   495.6  801.27   505.4  800.69     525801.3194   544.5  807.44   554.3  808.54
   612.5  809.53   621.8  810.01   631.1   812.2   677.6  833.72     724  858.22
#Mann= 3 , 0 , 0
       0      .1       0   495.6    .045       0     525      .1       0
Bank Sta=495.6,525
XS Rating Curve= 0 ,0
Exp/Cntr=0.3,0.1

Type RM Length L Ch R = 1 ,54295.1 ,606.1,568.6,530.9
XS GIS Cut Line= 4
       1874184.8      511173.474      1874302.41      511464.898
     1874267.687      511674.968     1874318.035      511817.329
#Sta/Elev= 30
       0  988.33     9.8  983.04    19.6  977.14    98.2  926.72   127.7  907.28
   147.3  893.68   196.4  858.59   225.9   838.5   245.5  826.68   265.2  815.55
     275  811.74   284.8  810.49   323.9  809.95   343.3  809.09   362.6  807.66
     382  801.12   391.7   800.3   401.2  800.58   403.7801.0315     411  802.35
   420.7  805.03   430.4  806.71   469.1  808.18   564.9  810.94   574.4  812.08
   583.8  815.67   621.6  838.49     631  843.61   659.3  856.07   678.2  865.26
#Mann= 3 , 0 , 0
       0      .1       0     382    .045       0   403.7      .1       0
Bank Sta=382,403.7
XS Rating Curve= 0 ,0
Exp/Cntr=0.3,0.1

Type RM Length L Ch R = 1 ,53726.5 ,438,445.4,452.7
XS GIS Cut Line= 4
     1873700.778      511831.829     1873862.993      511873.397
     1874151.774      511894.478     1874242.866      511919.455
#Sta/Elev= 30
       0  922.18    18.6  915.25    27.9  911.15    55.8  897.33    74.4  887.74
   102.3  872.56   120.9  862.16   130.2  857.29   139.6  853.07   158.2  845.56
   167.5  840.94   177.1  835.08   186.8     828   196.4  820.18   206.1  812.85
   215.7  807.12   225.4  802.82     235  799.86   237.2799.6213   244.7   798.8
   257.2799.0195     264  799.29   273.6  800.21   292.9  803.25   399.1  807.26
   408.8  808.75   418.4  812.18   466.4   833.8   513.7  857.03   551.5  875.28
#Mann= 3 , 0 , 0
       0      .1       0   237.2    .045       0   257.2      .1       0
Bank Sta=237.2,257.2
XS Rating Curve= 0 ,0
Exp/Cntr=0.3,0.1

Type RM Length L Ch R = 1 ,53281.1 ,311.4,341.1,369.4
XS GIS Cut Line= 3
     1873723.611      512233.144     1874044.263      512367.101
     1874330.107      512449.373
#Sta/Elev= 30
       0  842.57      29  833.75    38.6  829.98    48.3  825.31    77.2  809.63
    86.9  805.24    96.5  802.92   115.8  801.98   135.1  801.73   183.4  800.32
   193.1  799.82     222  796.66   231.7  796.61     251  796.93   270.3  801.29
   279.9  804.56   289.6  808.83   308.9   818.2   318.6   822.5   328.2  826.28
   337.9  829.91   357.1  834.94   366.7   837.9   376.3   841.5   424.3  861.74
   491.4  888.17   520.2  897.95   558.6  911.65   616.2  937.66     645  949.02
#Mann= 3 , 0 , 0
       0      .1       0     222    .045       0     251      .1       0
Bank Sta=222,251
XS Rating Curve= 0 ,0
Exp/Cntr=0.3,0.1

Type RM Length L Ch R = 1 ,52940.1 ,431.7,444.9,459.8
XS GIS Cut Line= 4
      1873703.57      512248.966     1873730.994      512463.085
     1873711.332       512728.83     1873622.352       512890.27
#Sta/Elev= 30
       0  841.33    29.4  829.42    58.9  818.18    88.3  807.44    98.1  804.79
   107.9  803.87   215.9  802.88   263.4   801.8     273   801.3   282.5  800.16
     311  793.92   320.6  793.29   339.6   793.6   349.1  796.64   368.1  808.11
   377.6  812.28   387.2   815.2   444.3  828.84   482.3   839.8   501.7  847.17
   511.4  851.62   521.2  856.76   550.2  873.54     560  878.19   589.1  888.86
   598.8  893.51   618.2  904.03   637.6  915.22   647.3  921.18   666.7  933.92
#Mann= 3 , 0 , 0
       0      .1       0     311    .045       0   339.6      .1       0
Bank Sta=311,339.6
XS Rating Curve= 0 ,0
Exp/Cntr=0.3,0.1

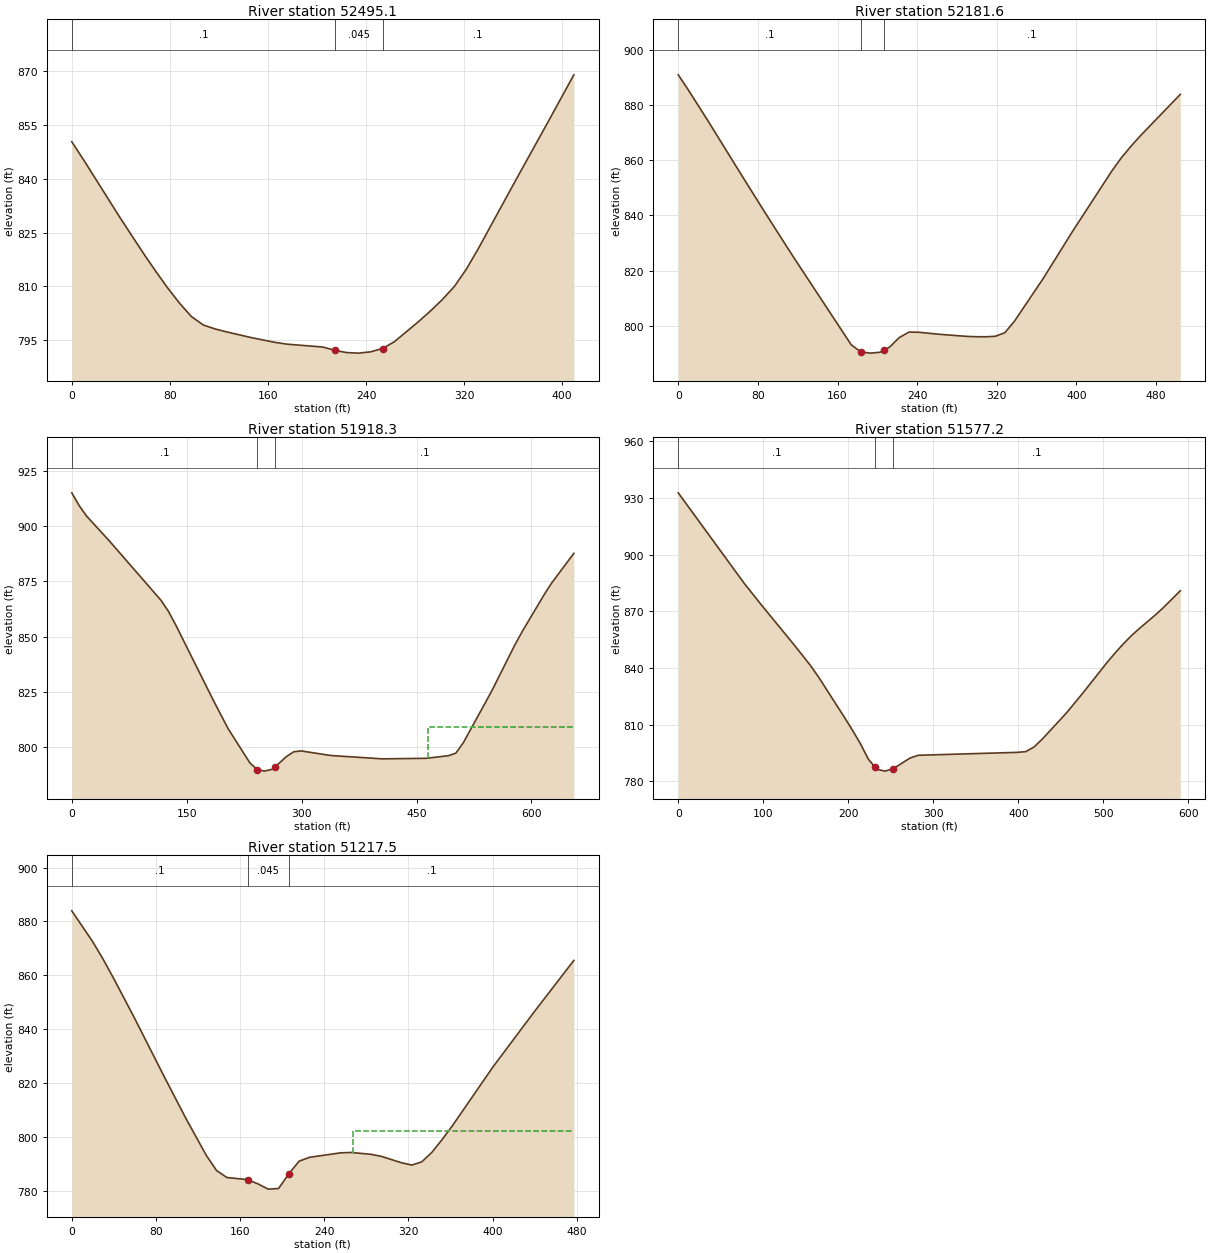
Type RM Length L Ch R = 1 ,52495.1 ,320.7,313.5,305.7
XS GIS Cut Line= 2
     1873567.504      512194.117     1873280.604       512486.29
#Sta/Elev= 30
       0  850.31     9.8  845.19      39  829.36    58.5  819.21    68.2  814.38
      78  809.69    87.8  805.39    97.5  801.65   107.2  799.29     117  798.16
   126.7  797.32   146.2  795.78   165.7  794.44   175.5  793.94   204.7  793.14
   214.5  792.23   224.2  791.59     234  791.44   243.7   791.8   253.5  792.72
   263.2  794.63   282.7  800.18   292.5  803.16   302.2  806.34     312  809.98
   321.7  814.76   331.5  820.48   360.7  838.72     390  856.78   409.5  868.94
#Mann= 3 , 0 , 0
       0      .1       0   214.5    .045       0   253.5      .1       0
Bank Sta=214.5,253.5
XS Rating Curve= 0 ,0
Exp/Cntr=0.3,0.1

Type RM Length L Ch R = 1 ,52181.6 ,272.8,263.4,253.9
XS GIS Cut Line= 3
     1873282.231      511963.127     1873140.043      512301.089
     1873141.534      512438.681
#Sta/Elev= 30
       0  890.84     9.6  885.67      29  874.68    67.5  852.29    86.8  841.19
   106.1  830.29   115.8  824.85   173.7  793.15   183.3  790.55     193   790.1
   202.6  790.41   206.3791.1194   212.3  792.27   221.9   795.7   231.6   797.7
   241.2  797.67   260.5  796.97   289.5  796.17   299.1  796.04   308.8  796.02
   318.4  796.19   328.1   797.5   337.7  801.65   366.6  817.13   396.1  834.19
   435.4  855.96   445.3  860.92   455.1  865.13   464.9  869.04   504.3  883.77
#Mann= 3 , 0 , 0
       0      .1       0   183.3    .045       0   206.3      .1       0
Bank Sta=183.3,206.3
XS Rating Curve= 0 ,0
Exp/Cntr=0.3,0.1

Type RM Length L Ch R = 1 ,51918.3 ,363.7,341.1,318.5
XS GIS Cut Line= 4
     1873013.217      511829.034     1872955.295      512024.754
     1872956.961      512119.808     1873072.609      512456.672
#Sta/Elev= 30
       0  915.06     9.7  909.26    19.4  904.52    48.6  893.49   116.6   866.4
   126.4  861.33   136.1  855.02   184.7  821.26   204.1  808.37   232.6  792.86
   242.1  789.92   251.6  789.19   261.2  789.99     265790.9946   280.2  795.78
   289.7  797.93   299.2  798.34   337.7  796.27   405.1  794.74   462.8  794.99
   491.7  796.17   501.3  797.32     511  802.02   539.8  820.14   549.5  826.38
   578.3  846.26     588  852.37   616.8  869.15   626.5  874.34   655.3  887.69
#Mann= 3 , 0 , 0
       0      .1       0   242.1    .045       0     265      .1       0
#XS Ineff= 2 , 0
                          464.52          809.17
Permanent Ineff=
       F       F
Bank Sta=242.1,265
XS Rating Curve= 0 ,0
Exp/Cntr=0.3,0.1

Type RM Length L Ch R = 1 ,51577.2 ,381.2,359.7,338.1
XS GIS Cut Line= 3
     1872535.757      512195.483      1872882.33      512411.929
     1873035.434      512510.017
#Sta/Elev= 30
       0  932.77    77.8  884.74    97.3  873.71   136.2  852.36   155.7  841.26
   165.4  835.03   194.6  814.54   204.3  807.58     214  800.18   223.8  791.67
   231.5787.5421   233.5  786.47   243.2  785.48     253   786.8   272.4  792.36
   282.1  793.86   398.9  795.42   408.6   795.8   418.2   798.2   427.8  802.29
   456.5  816.26   475.6   826.7   504.3     843   513.9   848.1   523.4  852.83
     533  857.22   542.6   861.1   561.7  868.38   571.3  872.37   590.4  880.94
#Mann= 3 , 0 , 0
       0      .1       0   231.5    .045       0     253      .1       0
Bank Sta=231.5,253
XS Rating Curve= 0 ,0
Exp/Cntr=0.3,0.1

Type RM Length L Ch R = 1 ,51217.5 ,279.8,279.4,279
XS GIS Cut Line= 3
     1872555.984       512730.75     1872800.775       512628.32
     1873010.845      512600.542
#Sta/Elev= 30
       0  883.93    19.7   872.6    29.5  866.18    39.3  859.22      59  844.61
    88.4  821.98   108.1  807.17   127.8  793.21   137.6  787.55   147.4  784.94
   167.1  784.14   176.9  782.59   186.7  780.62   196.6  780.85   206.4  786.35
   216.2  791.01     226  792.43   255.5  794.09   265.4  794.23   284.6  793.53
   294.2   792.8   313.5   790.4   323.2  789.55   332.8  790.75   342.4   794.3
     352  798.98   361.7  804.06   400.2  825.86   438.7  845.96   477.3  865.52
#Mann= 3 , 0 , 0
       0      .1       0   167.1    .045       0   206.4      .1       0
#XS Ineff= 2 , 0
                          267.71           802.2
Permanent Ineff=
       F       F
Bank Sta=167.1,206.4
XS Rating Curve= 0 ,0
Exp/Cntr=0.3,0.1