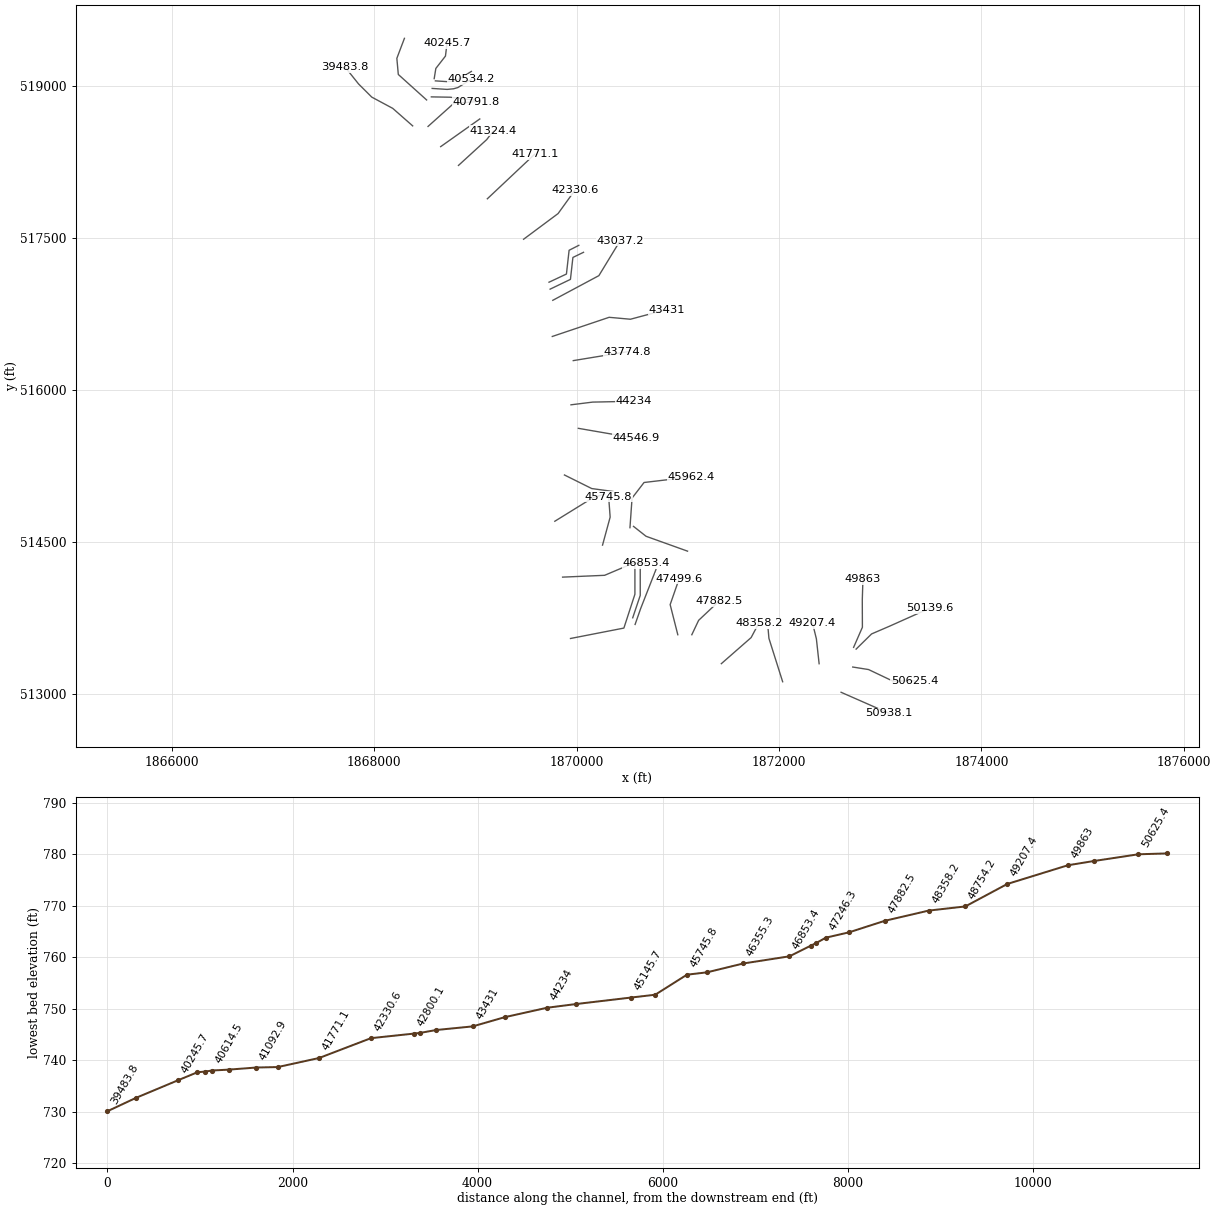
HEC-RAS study FALLINGRCR.prj: FALLINGRCR

--- FALLINGRCR.g01 (geometry) --- (continued)

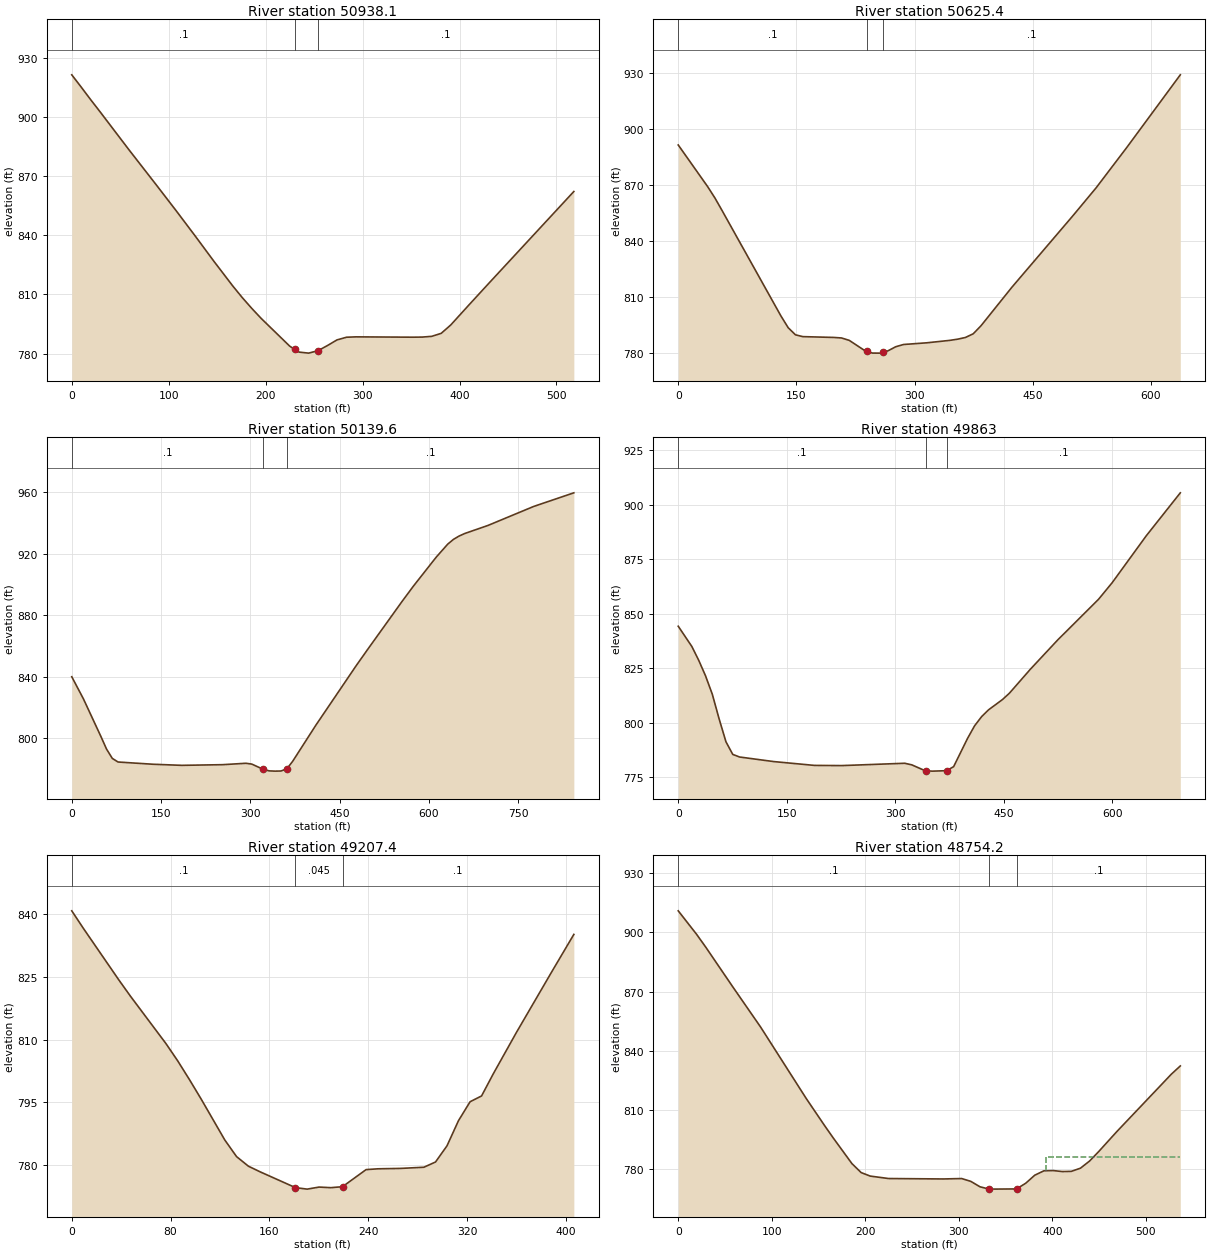
Type RM Length L Ch R = 1 ,50938.1 ,313.3,312.7,311.9
XS GIS Cut Line= 2
      1872613.42      513013.519     1873087.595      512805.186
#Sta/Elev= 30
       0  921.48     9.8  915.21    19.5  908.87    29.3  902.65    58.6  883.69
      88  865.09   107.5  852.61     127  839.88   146.6  826.84   166.1  814.28
   175.9  808.37   185.7   802.9   195.4  797.81   224.8  783.75   230.1 782.092
   234.5  780.72   244.3   780.2   254.1  781.45   263.8  784.07   273.6  786.91
   283.4  788.27   293.2  788.46   351.8  788.29   361.6  788.35   371.3  788.72
   381.1  790.25   390.9  794.48   410.4  805.04     430  815.54   517.9  862.25
#Mann= 3 , 0 , 0
       0      .1       0   230.1    .045       0   254.1      .1       0
Bank Sta=230.1,254.1
XS Rating Curve= 0 ,0
Exp/Cntr=0.3,0.1

Type RM Length L Ch R = 1 ,50625.4 ,466.3,485.8,504.9
XS GIS Cut Line= 4
     1872728.437      513263.085     1872884.687      513238.129
     1873124.488      513124.196     1873338.246      513127.452
#Sta/Elev= 30
       0   891.6    37.2  869.37    46.5  863.26    55.8  856.36   130.3  800.03
   139.6  793.66   148.9  789.84   158.2  788.87   197.6  788.44   207.4  788.15
   217.2  786.86   236.9  781.37   239.5781.0182   246.7  780.05   256.6  780.03
   259.5780.3992   266.4  781.28   276.2  783.46   286.1  784.66   315.6  785.56
   345.1  786.88   354.9  787.52   364.7  788.42   374.6  790.41   384.4  794.68
   423.7  815.37   501.5  853.85   530.6  868.64   569.5  890.24   637.5   929.2
#Mann= 3 , 0 , 0
       0      .1       0   239.5    .045       0   259.5      .1       0
Bank Sta=239.5,259.5
XS Rating Curve= 0 ,0
Exp/Cntr=0.3,0.1

Type RM Length L Ch R = 1 ,50139.6 ,249.9,276.6,302.8
XS GIS Cut Line= 4
     1872761.849      513440.044     1872914.649      513590.013
     1873094.783      513667.595     1873490.382       513844.59
#Sta/Elev= 30
       0  840.09    19.5  825.77    48.7  801.47    58.4  793.06    68.1  786.98
    77.8  784.64   136.2  783.19   184.9  782.47   253.3   782.9   292.6  783.82
   302.4   783.3     322  779.83   331.8  778.87   341.6  778.71   351.4  778.79
   361.2  780.13     371     785   410.2  808.62   477.6  847.13   496.9  857.72
   554.7  888.92     574  899.01   612.5  917.93   631.7  926.32   641.4  929.45
     651  931.63   660.6  933.29   699.2  938.47   776.2  950.85   843.6   959.7
#Mann= 3 , 0 , 0
       0      .1       0     322    .045       0   361.2      .1       0
Bank Sta=322,361.2
XS Rating Curve= 0 ,0
Exp/Cntr=0.3,0.1

Type RM Length L Ch R = 1 ,49863   ,653.3,655.6,658.2
XS GIS Cut Line= 4
     1872737.118      513457.313     1872823.923       513655.88
     1872822.838      513926.063     1872829.349      514133.311
#Sta/Elev= 30
       0  844.29    18.8  835.02    28.3   828.7    37.7  821.61    47.1  813.14
    56.5  801.88      66  791.34    75.4  785.56    84.8  784.37   131.9  782.28
   188.4  780.52   226.4  780.44   313.2   781.5   322.9  780.78   342.2  777.97
   351.8   777.9   371.1   778.1   380.8  779.96     400  792.88   409.7  798.63
   419.4  802.84     429  805.97   448.3  810.69     458  813.64   486.9  824.59
   524.6  837.97   581.2  856.65     600  864.24   647.1  885.71   694.2  905.41
#Mann= 3 , 0 , 0
       0      .1       0   342.2    .045       0   371.1      .1       0
Bank Sta=342.2,371.1
XS Rating Curve= 0 ,0
Exp/Cntr=0.3,0.1

Type RM Length L Ch R = 1 ,49207.4 ,448.7,453.2,457.6
XS GIS Cut Line= 3
     1872396.406      513295.637     1872369.279      513541.948
     1872331.302      513696.028
#Sta/Elev= 30
       0  840.85     9.5  836.61    38.1  824.32    47.6  820.39    76.2  809.11
    85.8  804.94    95.3  800.46   104.8  795.79   123.9  786.02   133.4  782.05
     143  779.75   152.5   778.4   181.1  774.62   190.6  774.26   200.2  774.75
   209.7  774.61   219.2  774.84   238.3  778.93   247.8  779.12   266.5  779.22
   285.1   779.5   294.5  780.75   303.8  784.62   313.1  790.64   322.5  795.17
   331.8  796.56   341.2  801.81   359.8  811.64   387.8  825.85   406.5  835.21
#Mann= 3 , 0 , 0
       0      .1       0   181.1    .045       0   219.2      .1       0
Bank Sta=181.1,219.2
XS Rating Curve= 0 ,0
Exp/Cntr=0.3,0.1

Type RM Length L Ch R = 1 ,48754.2 ,422.4,396,369.4
XS GIS Cut Line= 3
     1872036.163      513117.686     1871900.529      513546.288
     1871892.934      513633.094
#Sta/Elev= 30
       0  910.88    19.6     899    29.3  892.56    58.6  872.17      88  852.05
   136.8  815.83   156.4  802.12   166.1  795.56   185.7  782.82   195.5  778.29
   205.2  776.51   224.8  775.27   283.4  775.05     303  775.26   312.7  773.84
   322.5   771.1   332.3   769.9   361.6     770   371.4  772.86   381.1  776.95
   390.9  779.18   400.7   779.3   410.5  778.81   420.2   778.9     430  780.52
   439.8  784.17   449.6     789   468.9  799.08     527  828.07   536.7  832.31
#Mann= 3 , 0 , 0
       0      .1       0   332.3    .045       0   361.6      .1       0
#XS Ineff= 2 , 0
                          392.63           786.4
Permanent Ineff=
       F       F
Bank Sta=332.3,361.6
XS Rating Curve= 0 ,0
Exp/Cntr=0.3,0.1

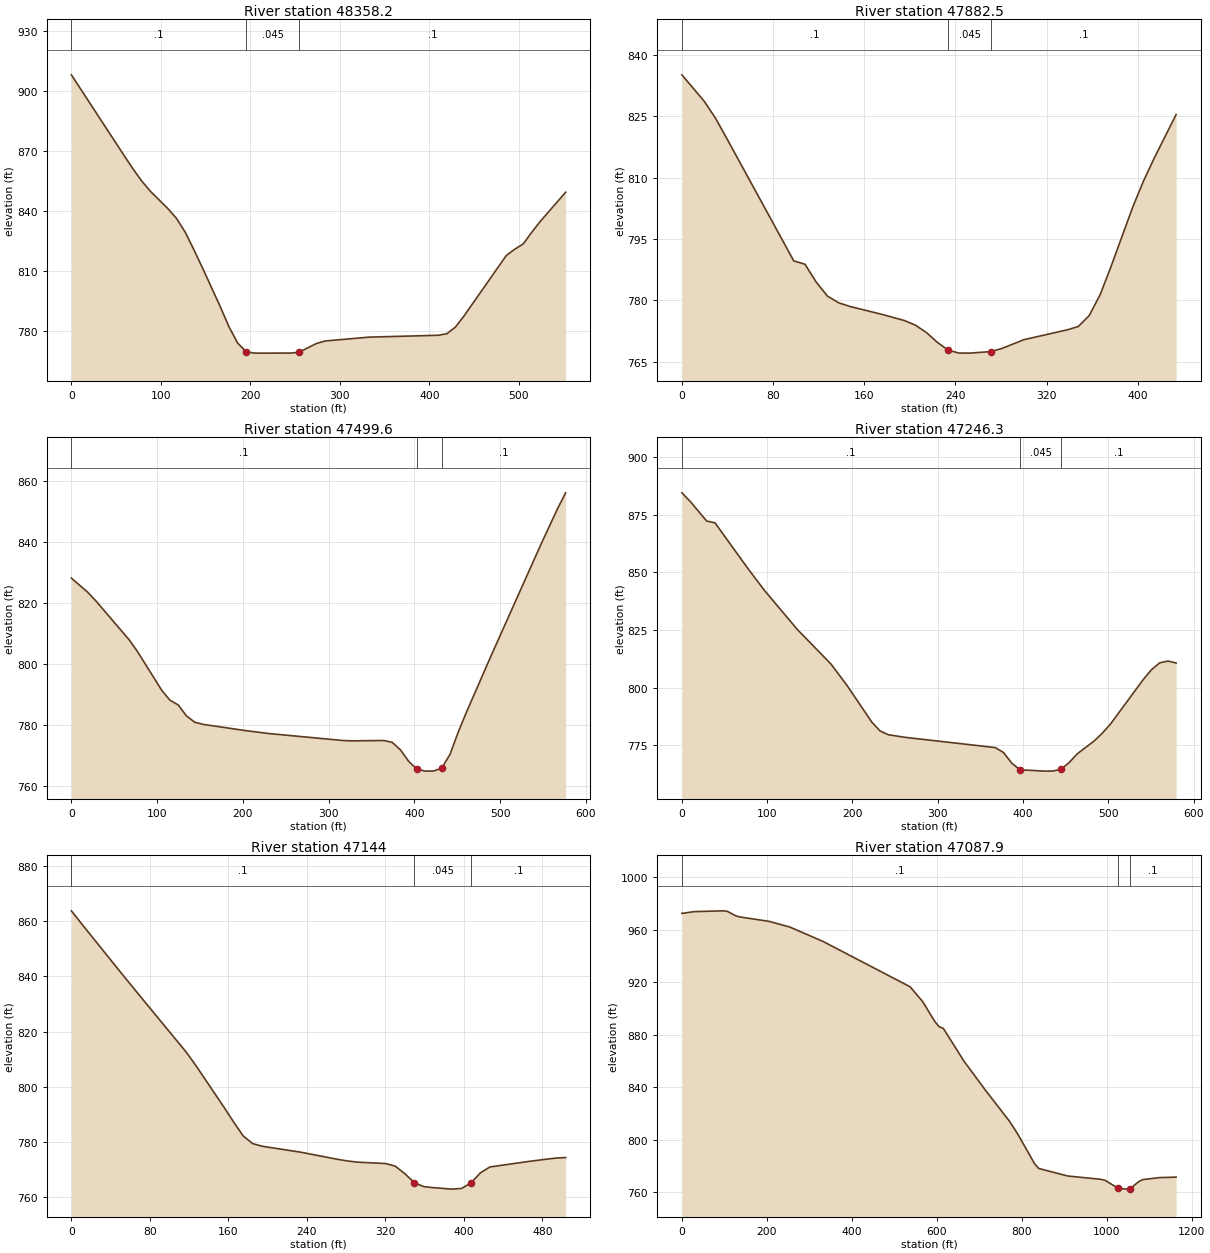
Type RM Length L Ch R = 1 ,48358.2 ,474.8,475.7,476.4
XS GIS Cut Line= 3
     1871430.448      513296.273     1871724.748      513553.884
     1871800.534      513696.043
#Sta/Elev= 30
       0  908.24    58.7  868.04    68.4  861.52    78.2  855.38      88  850.14
   107.6  841.46   117.3  836.55   127.1  829.64   136.9  820.77   146.7   811.5
   166.2  792.47     176  782.34   185.8  774.08   195.6  769.71   205.3  769.09
   244.4  769.11   254.2  769.49   273.8  773.91   283.6  775.16   332.4  777.08
   410.1  778.02   419.6  778.82     429  782.08   438.5  787.55   485.9  817.88
   495.4  821.06   504.8  823.68   514.3  829.47   523.8  834.92   552.2  849.53
#Mann= 3 , 0 , 0
       0      .1       0   195.6    .045       0   254.2      .1       0
Bank Sta=195.6,254.2
XS Rating Curve= 0 ,0
Exp/Cntr=0.3,0.1

Type RM Length L Ch R = 1 ,47882.5 ,372,382.9,393.8
XS GIS Cut Line= 3
     1871138.811      513582.096     1871206.027      513724.166
     1871407.388      513913.721
#Sta/Elev= 30
       0  835.15    19.6   828.7    29.5  824.55    39.3  819.66    98.2  789.65
     108  788.84   117.9  784.47   127.7  781.06   137.5  779.41   147.4  778.52
   176.2  776.53   195.3  775.07   204.8  773.96   214.4  772.18   223.9  769.81
   233.5  767.85     243  767.12   252.5   767.1   271.6  767.48   281.1  768.27
   300.2  770.39   338.4  772.81   347.9  773.62   357.4  776.27     367  781.35
   376.5  788.21   395.6  802.78   405.1  809.19   414.6  814.84   433.7  825.44
#Mann= 3 , 0 , 0
       0      .1       0   233.5    .045       0   271.6      .1       0
Bank Sta=233.5,271.6
XS Rating Curve= 0 ,0
Exp/Cntr=0.3,0.1

Type RM Length L Ch R = 1 ,47499.6 ,254.1,253.3,252.4
XS GIS Cut Line= 3
     1871000.356      513582.096     1870924.773      513879.445
     1871013.377      514134.179
#Sta/Elev= 30
       0  828.08    19.2  823.41    28.8  820.54    67.1  807.98    76.7   804.2
   105.5   791.3     115  788.09   124.6  786.56   134.2  782.96   143.8  780.91
   153.4   780.2   201.3  778.22   230.1  777.19   316.4  774.91   326.1  774.79
   364.6   774.9   374.2   774.3   383.9  771.82   393.5  768.06   403.1  765.49
   412.8  764.88   422.4  764.91     432  765.87   441.7  770.39   451.3  777.71
   460.9  784.22   489.8   802.8   547.6  839.04   566.9  850.69   576.5  855.99
#Mann= 3 , 0 , 0
       0      .1       0   403.1    .045       0     432      .1       0
Bank Sta=403.1,432
XS Rating Curve= 0 ,0
Exp/Cntr=0.3,0.1

Type RM Length L Ch R = 1 ,47246.3 ,93.6,102.3,111.1
XS GIS Cut Line= 3
     1870578.481      513683.658     1870633.009       513839.46
      1870784.21      514225.325
#Sta/Elev= 30
       0  884.45     9.7  880.77    29.1  872.23    38.8  871.47    77.7  851.52
    97.1  842.04   135.9  825.02   174.7   810.3     194  800.79   222.9  784.98
   232.5  781.22   242.2   779.6   261.4  778.49   367.5  774.03   377.1  771.91
   386.7  767.34   396.4  764.41   425.3  763.83   434.9  763.85   444.6  764.62
   454.2  767.58   463.8  771.41   483.1  776.79   492.8  780.21   502.4  784.16
     541  803.52   550.6  807.78   560.2  810.75   569.9  811.54   579.5   810.7
#Mann= 3 , 0 , 0
       0      .1       0   396.4    .045       0   444.6      .1       0
Bank Sta=396.4,444.6
XS Rating Curve= 0 ,0
Exp/Cntr=0.3,0.1

Type RM Length L Ch R = 1 ,47144   ,56.1,56.1,56.1
XS GIS Cut Line= 3
     1870554.946      513749.395      1870629.33      513970.749
      1870629.33       514240.95
#Sta/Elev= 30
       0  863.82     9.7  859.45    48.6  842.21    68.1   833.7   116.8  812.64
   126.5  807.87   155.7  792.44   165.4  787.15   175.1   782.1   184.9   779.3
   194.6  778.36   233.5  776.22   272.1  773.57   281.8  773.01   291.4  772.59
   320.4  772.08     330  771.15   339.7  768.45   349.3  765.19     359  763.72
   368.6  763.34   387.9   762.8   397.6  763.04   407.2  765.04   416.9  768.71
   426.5  770.84   465.1   772.8   484.4  773.68   494.1  774.07   503.7  774.28
#Mann= 3 , 0 , 0
       0      .1       0   349.3    .045       0   407.2      .1       0
Bank Sta=349.3,407.2
XS Rating Curve= 0 ,0
Exp/Cntr=0.3,0.1

Type RM Length L Ch R = 1 ,47087.9 ,261.2,234.5,207.5
XS GIS Cut Line= 4
     1869940.362      513544.968     1870467.706      513647.833
     1870576.553      513981.835     1870576.553      514256.575
#Sta/Elev= 30
       0   972.5    29.3  973.86    97.7  974.47   107.5  974.03     127  970.63
   136.8  969.78   205.1  966.45     254  962.12   332.1  951.16   537.3  916.56
   566.6  905.35   595.8  889.87   605.6  886.15   615.4  884.85   664.1  859.85
   712.9  838.42   771.5  813.91     791  804.07     830  781.78   839.8  778.09
   908.2  772.31   986.7  769.76   996.5  768.97    1026763.0941  1045.6  762.31
  1055.4   762.7    1075  767.96  1084.8  769.58  1124.1  771.09  1163.3  771.45
#Mann= 3 , 0 , 0
       0      .1       0    1026    .045       0  1055.4      .1       0
Bank Sta=1026,1055.4
XS Rating Curve= 0 ,0
Exp/Cntr=0.3,0.1

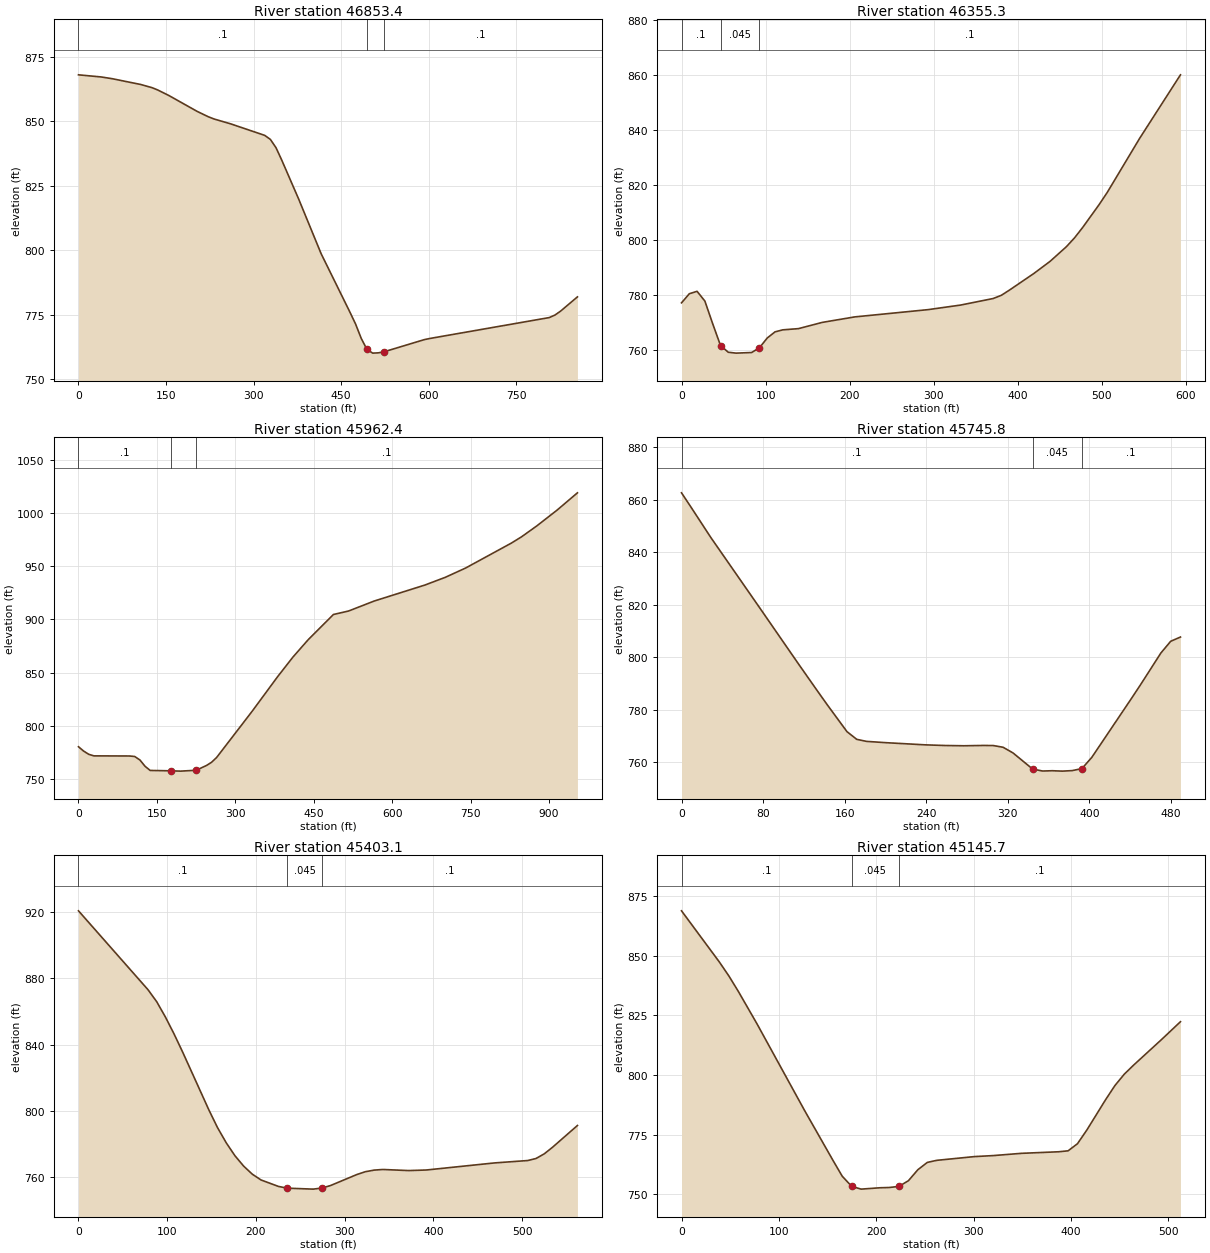
Type RM Length L Ch R = 1 ,46853.4 ,522.4,498,473.5
XS GIS Cut Line= 4
     1869862.335      514151.106     1870277.774      514169.124
     1870566.762      514291.731     1870691.762      514286.523
#Sta/Elev= 30
       0  867.99    38.7  867.17      58  866.48   106.4  864.26   125.7  863.04
   135.4  862.16   154.7     860   203.1  853.86   222.4  851.75   232.1   850.9
   261.1  848.98   319.1  844.54   328.8  842.98   338.5  839.74   348.1  835.05
   377.2  819.91   415.8  798.69   464.9  776.17   474.7  771.52   484.5  765.89
   494.3  761.63   504.1  760.21   513.9  760.32   523.7  760.74   592.4  765.43
   602.2  765.89   806.7  773.98   816.4  774.96     826  776.47   854.9  781.99
#Mann= 3 , 0 , 0
       0      .1       0   494.3    .045       0   523.7      .1       0
Bank Sta=494.3,523.7
XS Rating Curve= 0 ,0
Exp/Cntr=0.3,0.1

Type RM Length L Ch R = 1 ,46355.3 ,343.5,393,441.9
XS GIS Cut Line= 3
     1870562.856      514652.408     1870686.554      514554.752
      1871096.71      514407.617
#Sta/Elev= 30
       0  777.09     9.3   780.4    18.5  781.28    27.8  777.73    37.1  769.48
    46.4  761.59    55.6  759.14    64.9  758.82    83.4  759.04    92.7  760.78
     102  764.33   111.2  766.54   120.5  767.28   139.1  767.72   167.3  769.98
     206  771.98   293.2  774.62   331.9  776.28   370.6  778.66   380.3  779.82
     390  781.72     419  787.75   438.4  792.18   457.8  797.51   467.5  800.73
   477.2  804.52   496.5  812.72   506.2  817.15   544.9  836.88   593.4  859.94
#Mann= 3 , 0 , 0
       0      .1       0    46.4    .045       0    92.7      .1       0
Bank Sta=46.4,92.7
XS Rating Curve= 0 ,0
Exp/Cntr=0.3,0.1

Type RM Length L Ch R = 1 ,45962.4 ,213.4,216.6,220
XS GIS Cut Line= 4
       1870527.7      514639.387     1870548.533      514932.356
     1870667.022      515086.002     1871130.564       515140.69
#Sta/Elev= 30
       0  780.08     9.8  776.01    19.6  772.96    29.4  771.48    97.9  771.36
   107.7  770.86   117.5   767.6   127.3  761.68   137.1  757.74   176.2  757.38
   195.8   757.1   225.2  757.92   244.8  762.41   254.6  765.44   264.3  769.98
   332.5   813.7     381  846.14   410.1  864.48   439.2  880.83   487.7  904.71
   516.9  908.02   565.5  917.36   662.8  932.48   701.7  939.73   740.6   948.5
   828.1  971.99   847.5  977.89   876.7  988.16   915.6 1003.09   954.5 1019.37
#Mann= 3 , 0 , 0
       0      .1       0   176.2    .045       0   225.2      .1       0
Bank Sta=176.2,225.2
XS Rating Curve= 0 ,0
Exp/Cntr=0.3,0.1

Type RM Length L Ch R = 1 ,45745.8 ,367.3,342.6,317.8
XS GIS Cut Line= 3
     1870256.866      514467.512     1870332.048      514743.786
     1870317.173      514946.136
#Sta/Elev= 30
       0  862.68     9.5  857.11    28.6  845.74    76.4  819.01   114.5  797.59
   133.6     787   143.2  781.76   162.2  771.69   171.8  768.75   181.3  767.98
   200.4  767.48   238.6  766.66   257.7  766.41   276.8   766.3     296  766.42
   305.6  766.39   315.3  765.73     325  763.58   344.3  757.42     354  756.68
   363.6  756.79   373.3  756.64   382.9  756.83   392.6   757.6   402.3   761.9
   440.9  784.19   450.6  789.89   469.9  801.59   479.6  806.11   489.2  807.73
#Mann= 3 , 0 , 0
       0      .1       0   344.3    .045       0   392.6      .1       0
Bank Sta=344.3,392.6
XS Rating Curve= 0 ,0
Exp/Cntr=0.3,0.1

Type RM Length L Ch R = 1 ,45403.1 ,280.4,257.4,234.2
XS GIS Cut Line= 3
     1869785.512       514703.19     1870160.512       514934.96
     1870276.397      514971.419
#Sta/Elev= 30
       0  920.65    78.4  873.03    88.2  865.78      98  856.56   107.8  846.26
   117.6   835.2     147  800.48   156.7  789.85   166.5   780.7   176.3  772.91
   186.1  766.66   195.9  761.76   205.7  758.28   225.3  754.39   235.1  753.33
   264.5  752.75   274.3   753.4   284.1  754.92   313.5  761.51   323.3  763.26
   333.1  764.22   342.9   764.6   372.3  763.94   391.9  764.28   468.9  768.56
   506.3     770   515.6  771.22     525  774.07   534.3  778.04   562.3  791.14
#Mann= 3 , 0 , 0
       0      .1       0   235.1    .045       0   274.3      .1       0
Bank Sta=235.1,274.3
XS Rating Curve= 0 ,0
Exp/Cntr=0.3,0.1

Type RM Length L Ch R = 1 ,45145.7 ,591.9,598.8,605.4
XS GIS Cut Line= 3
     1869880.564      515160.221     1870150.095      515026.106
     1870359.731       514997.46
#Sta/Elev= 30
       0  868.79    38.8   847.4    48.6  841.54    58.3  835.09    77.7  821.34
   126.2  785.32   155.4   764.4   165.1  757.63   174.8  753.38   184.5  752.21
   203.9  752.78   213.4  752.89   223.4  753.36   233.1  755.73   242.8  760.33
   252.5   763.4   262.2  764.27     301  765.84   320.3  766.26   349.1   767.2
   387.6  767.86   397.2  768.26   406.8  771.24   416.5  777.02   435.7  789.68
   445.3  795.62   454.9  800.37   464.6  804.21   493.4  814.96   512.6  822.34
#Mann= 3 , 0 , 0
       0      .1       0   174.8    .045       0   223.4      .1       0
Bank Sta=174.8,223.4
XS Rating Curve= 0 ,0
Exp/Cntr=0.3,0.1

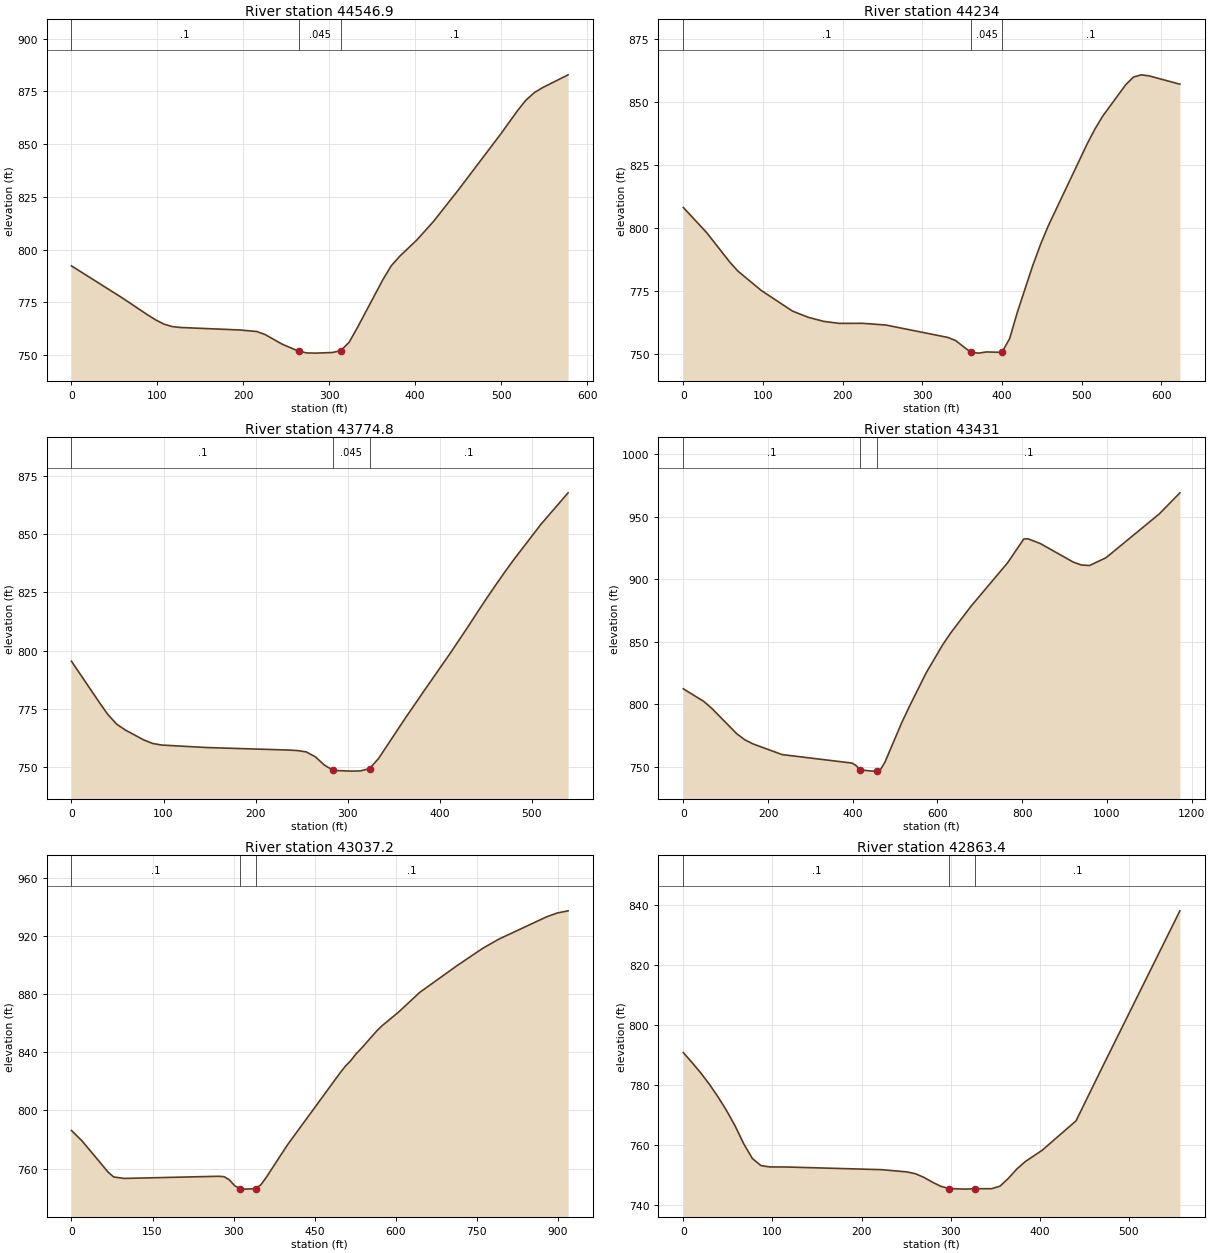
Type RM Length L Ch R = 1 ,44546.9 ,308.5,312.9,317.2
XS GIS Cut Line= 2
     1870018.083      515621.035     1870587.536      515522.686
#Sta/Elev= 30
       0  792.28    58.8  777.19    88.2  769.18      98  766.68   107.7  764.67
   117.5   763.5   127.3  763.08   195.9  761.91   215.5  761.19   225.3  759.76
   244.9  755.23   264.5  751.82   274.2  751.02     284  750.94   303.6  751.23
   313.4  752.13   323.2  756.14     333  763.25   362.4  785.78   372.2  792.39
     382  796.86   401.6  804.43   421.2   813.3   450.6  828.48   499.5  854.77
   519.1  865.85   528.9  870.84   538.7  874.39   548.5  876.81   577.9  882.81
#Mann= 3 , 0 , 0
       0      .1       0   264.5    .045       0   313.4      .1       0
Bank Sta=264.5,313.4
XS Rating Curve= 0 ,0
Exp/Cntr=0.3,0.1

Type RM Length L Ch R = 1 ,44234   ,456,459.3,462.4
XS GIS Cut Line= 3
     1869945.232        515853.4     1870158.928      515880.112
     1870566.895      515888.611
#Sta/Elev= 30
       0  808.09    29.4  798.08    58.7  786.25    68.5  782.82    97.9  775.11
     137  766.93   156.6  764.48   176.2  762.83   195.8  762.04   225.1  762.06
   254.2  761.39     332  756.46   341.7  755.25   361.1   750.5   370.8  750.22
   380.5  750.69     400  750.53   409.7  756.01   419.4  766.53   438.8  785.13
   448.5  793.44   458.2  800.82   506.8  833.22   516.5  839.11   526.3  844.29
   555.4  856.85   565.1  859.88   574.8  860.78   584.6  860.37   623.4  857.06
#Mann= 3 , 0 , 0
       0      .1       0   361.1    .045       0     400      .1       0
Bank Sta=361.1,400
XS Rating Curve= 0 ,0
Exp/Cntr=0.3,0.1

Type RM Length L Ch R = 1 ,43774.8 ,340.1,343.7,347.4
XS GIS Cut Line= 2
     1869967.872      516289.958     1870500.164      516377.458
#Sta/Elev= 30
       0  795.47    29.4  778.32    39.2   772.8      49  768.53    58.8  765.93
    78.5  761.75    88.3  760.22    98.1  759.55   147.1  758.49   235.4  757.42
   245.2   757.2     255  756.62   264.8  754.54   274.6     751   284.4  748.68
     304  748.38   313.8  748.48   323.7  749.45   333.5  753.78   362.9  771.26
   382.5  782.53   411.9   799.2   431.6  810.81   441.4  816.78   451.2  822.61
     461  828.27   470.8  833.79   480.6  839.11     510   854.2   539.4  867.65
#Mann= 3 , 0 , 0
       0      .1       0   284.4    .045       0   323.7      .1       0
Bank Sta=284.4,323.7
XS Rating Curve= 0 ,0
Exp/Cntr=0.3,0.1

Type RM Length L Ch R = 1 ,43431   ,390.1,393.9,397.6
XS GIS Cut Line= 4
     1869760.521      516528.574     1870321.919      516717.766
     1870532.327      516698.709      1870888.23      516794.195
#Sta/Elev= 30
       0   812.4    48.6   802.3      68  796.53   126.2  776.48   145.7  771.55
   165.1  768.29   233.1  759.83   398.2  753.04   407.9  751.02   417.6  747.54
   446.7   746.6   456.4  746.66   466.2  748.26   475.9  753.72   514.7  784.64
   534.2  798.69     573  825.02   611.6  847.25   630.8  856.91   678.8  878.29
   765.3  913.09   803.7  932.22   813.4  932.37   842.5  928.61     920  913.81
   939.4  911.42   958.8     911   997.6  917.17  1123.7   952.3  1172.2  969.11
#Mann= 3 , 0 , 0
       0      .1       0   417.6    .045       0   456.4      .1       0
Bank Sta=417.6,456.4
XS Rating Curve= 0 ,0
Exp/Cntr=0.3,0.1

Type RM Length L Ch R = 1 ,43037.2 ,148.3,173.8,199.3
XS GIS Cut Line= 3
      1869765.43       516885.68     1870220.717      517129.367
     1870430.044      517473.128
#Sta/Elev= 30
       0  786.17    19.5  779.05    68.2  757.41      78  754.26    97.4  753.25
   272.8  754.74   282.6  754.42   292.3  752.21     302  748.24   311.8  746.13
   321.5   745.9     341  746.22   350.8  749.03   360.5  754.04   399.5  776.23
   496.9  825.72   506.7  830.37   516.4  834.03   526.2  838.69     536  842.45
   565.5  854.87   575.3  858.35   604.8  867.39     644  880.96   712.7  899.26
   761.8  911.55   791.3  917.75   879.6  933.05   899.2  935.65   918.9  937.11
#Mann= 3 , 0 , 0
       0      .1       0   311.8    .045       0     341      .1       0
Bank Sta=311.8,341
XS Rating Curve= 0 ,0
Exp/Cntr=0.3,0.1

Type RM Length L Ch R = 1 ,42863.4 ,61.7,63.3,64.8
XS GIS Cut Line= 4
     1869739.053         516996.     1869939.747      517092.528
     1869964.078      517309.191     1870068.914      517359.889
#Sta/Elev= 30
       0  790.76     9.7   787.5    19.4  784.06      29  780.34    38.7  776.14
    48.4  771.54    58.1  766.39    67.8  760.43    77.5  755.53    87.1  753.18
    96.8  752.73   116.2   752.7   222.7  751.81   251.1  751.06   260.6  750.45
   270.1  749.23   279.6  747.64   289.1  746.26   298.5  745.52   316.6  745.34
     327  745.48   345.9  745.48   355.4  746.33   364.9  748.97   374.4  752.09
   383.8  754.52   402.8  758.31   440.7  768.07   469.8  785.69   557.2  837.92
#Mann= 3 , 0 , 0
       0      .1       0   298.5    .045       0     327      .1       0
Bank Sta=298.5,327
XS Rating Curve= 0 ,0
Exp/Cntr=0.3,0.1

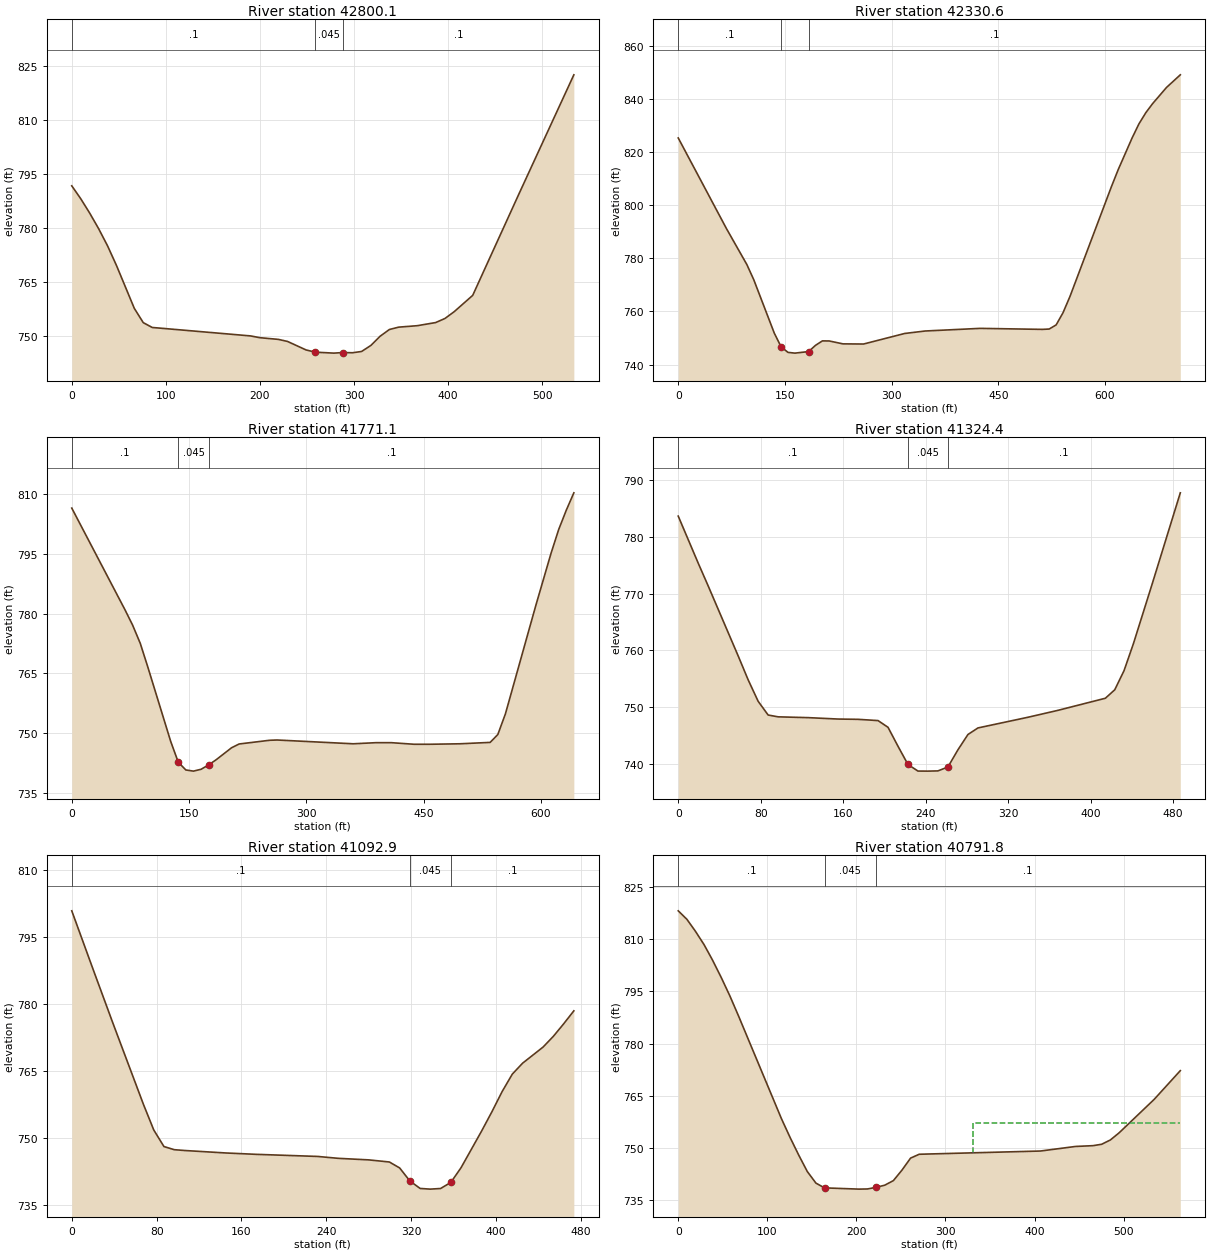
Type RM Length L Ch R = 1 ,42800.1 ,493.2,469.5,445.7
XS GIS Cut Line= 4
     1869728.123      517064.499     1869900.164      517145.305
     1869926.515      517379.954     1870022.386      517428.639
#Sta/Elev= 30
       0  791.69     9.5  788.12      19  784.14    28.5  779.81      38  775.04
    47.5  769.58    66.5  757.64      76  753.68    85.5  752.34   190.1  749.99
   199.9   749.5   219.6  749.03   229.4  748.45   249.1  746.09   258.9  745.48
   278.6  745.21   288.5  745.38   298.3  745.31   308.1  745.67     318  747.36
   327.8  749.91   337.6  751.77   347.5  752.43   367.2  752.83   386.8   753.7
   396.7  754.84   406.5  756.72   426.2  761.26   475.1   789.3   533.7  822.53
#Mann= 3 , 0 , 0
       0      .1       0   258.9    .045       0   288.5      .1       0
Bank Sta=258.9,288.5
XS Rating Curve= 0 ,0
Exp/Cntr=0.3,0.1

Type RM Length L Ch R = 1 ,42330.6 ,556.9,559.6,562.1
XS GIS Cut Line= 3
     1869477.097      517489.074     1869817.693      517742.633
     1869982.305      517970.845
#Sta/Elev= 30
       0   825.4    67.6  791.34    96.5  777.69   106.2  771.98   135.1  751.82
   144.8  746.61   154.4  744.59   164.1  744.31   183.4   744.9     193  747.24
   202.7  748.92   212.3  748.89   231.6   747.8   260.6  747.74   318.5  751.72
   347.4  752.65   424.6  753.64   511.9  753.26   521.6  753.39   531.4  754.94
     541   759.5   550.8  765.63     609  806.95   618.7  813.48   638.1  825.33
   647.8  830.69   657.5  834.92   667.2  838.38   686.6  844.43     706  849.19
#Mann= 3 , 0 , 0
       0      .1       0   144.8    .045       0   183.4      .1       0
Bank Sta=144.8,183.4
XS Rating Curve= 0 ,0
Exp/Cntr=0.3,0.1

Type RM Length L Ch R = 1 ,41771.1 ,446.7,446.6,446.4
XS GIS Cut Line= 2
     1869119.024      517888.813     1869586.472      518328.918
#Sta/Elev= 30
       0  806.47    68.1  780.93    77.8   777.1    87.6  772.52    97.3  766.55
   126.5  747.92   136.2  742.69   145.9  740.75   155.6  740.46   165.4  740.93
   175.1  742.03   184.8  743.34   204.3  746.32     214  747.27   252.9   748.2
   262.6  748.27   359.9  747.32   389.1   747.6   408.6   747.6   437.8   747.2
   457.2   747.2   496.1  747.32     535  747.67   544.8  749.65   554.5  754.83
   593.4  782.05   612.8   795.1   622.6  801.08   632.3  805.92     642   810.3
#Mann= 3 , 0 , 0
       0      .1       0   136.2    .045       0   175.1      .1       0
Bank Sta=136.2,175.1
XS Rating Curve= 0 ,0
Exp/Cntr=0.3,0.1

Type RM Length L Ch R = 1 ,41324.4 ,234.5,231.5,228.7
XS GIS Cut Line= 3
     1868833.651       518218.24     1869112.514      518473.232
     1869178.703      518560.037
#Sta/Elev= 30
       0   783.7    19.4  775.39    29.1  771.36    58.1  759.05    67.8  754.82
    77.5  751.03    87.2   748.6    96.9  748.28     126  748.14     155  747.89
   174.4  747.84   193.8  747.62   203.5  746.43   213.2  743.08   222.8  739.88
   232.5  738.71   242.2   738.7   251.9  738.74   261.6  739.43   271.3  742.46
     281  745.16   290.7  746.32   339.1   748.2   368.2  749.42   414.3  751.56
   423.4  753.05   432.4  756.42   441.6  761.24   459.7  771.72     487  787.81
#Mann= 3 , 0 , 0
       0      .1       0   222.8    .045       0   261.6      .1       0
Bank Sta=222.8,261.6
XS Rating Curve= 0 ,0
Exp/Cntr=0.3,0.1

Type RM Length L Ch R = 1 ,41092.9 ,298.4,301.1,303.6
XS GIS Cut Line= 2
      1868657.87      518403.787     1869044.154      518677.225
#Sta/Elev= 30
       0  800.77    19.3  788.22    38.6   775.8    67.6  757.52    77.3  751.82
    86.9  748.12    96.6  747.42   106.2  747.24   144.9  746.69   173.8  746.38
   231.8  745.91   251.1  745.49   280.1  745.14   299.4  744.67   309.1  743.34
   318.7  740.44   328.4  738.76     338  738.61   347.7  738.75   357.4  740.12
     367  743.41   386.3  751.56     396  755.86   405.7   760.4   415.3   764.3
     425  766.74   444.3  770.34     454  772.74   463.6   775.5   473.3  778.43
#Mann= 3 , 0 , 0
       0      .1       0   318.7    .045       0   357.4      .1       0
Bank Sta=318.7,357.4
XS Rating Curve= 0 ,0
Exp/Cntr=0.3,0.1

Type RM Length L Ch R = 1 ,40791.8 ,194.3,177.3,160.2
XS GIS Cut Line= 3
     1868533.087       518603.44     1868784.823      518829.135
     1869009.432      518848.666
#Sta/Elev= 30
       0  818.18     9.7  815.75    19.3  812.31      29  808.46    38.6  803.97
    48.3  799.01      58  793.71    67.6  788.02   115.9  758.42   125.6  753.03
   135.2  748.01   144.9  743.25   154.6  739.92   164.2  738.56   202.9   738.2
   212.5  738.25   222.2  738.72   231.8  739.33   241.5  740.64   251.2  743.68
   260.8  747.11   270.5  748.22   406.7  749.15   445.9  750.46   465.5  750.69
   475.3  751.09   485.1  752.33   494.9  754.38   534.2  763.98   563.6  772.25
#Mann= 3 , 0 , 0
       0      .1       0   164.2    .045       0   222.2      .1       0
#XS Ineff= 2 , 0
                          331.02          757.17
Permanent Ineff=
       F       F
Bank Sta=164.2,222.2
XS Rating Curve= 0 ,0
Exp/Cntr=0.3,0.1

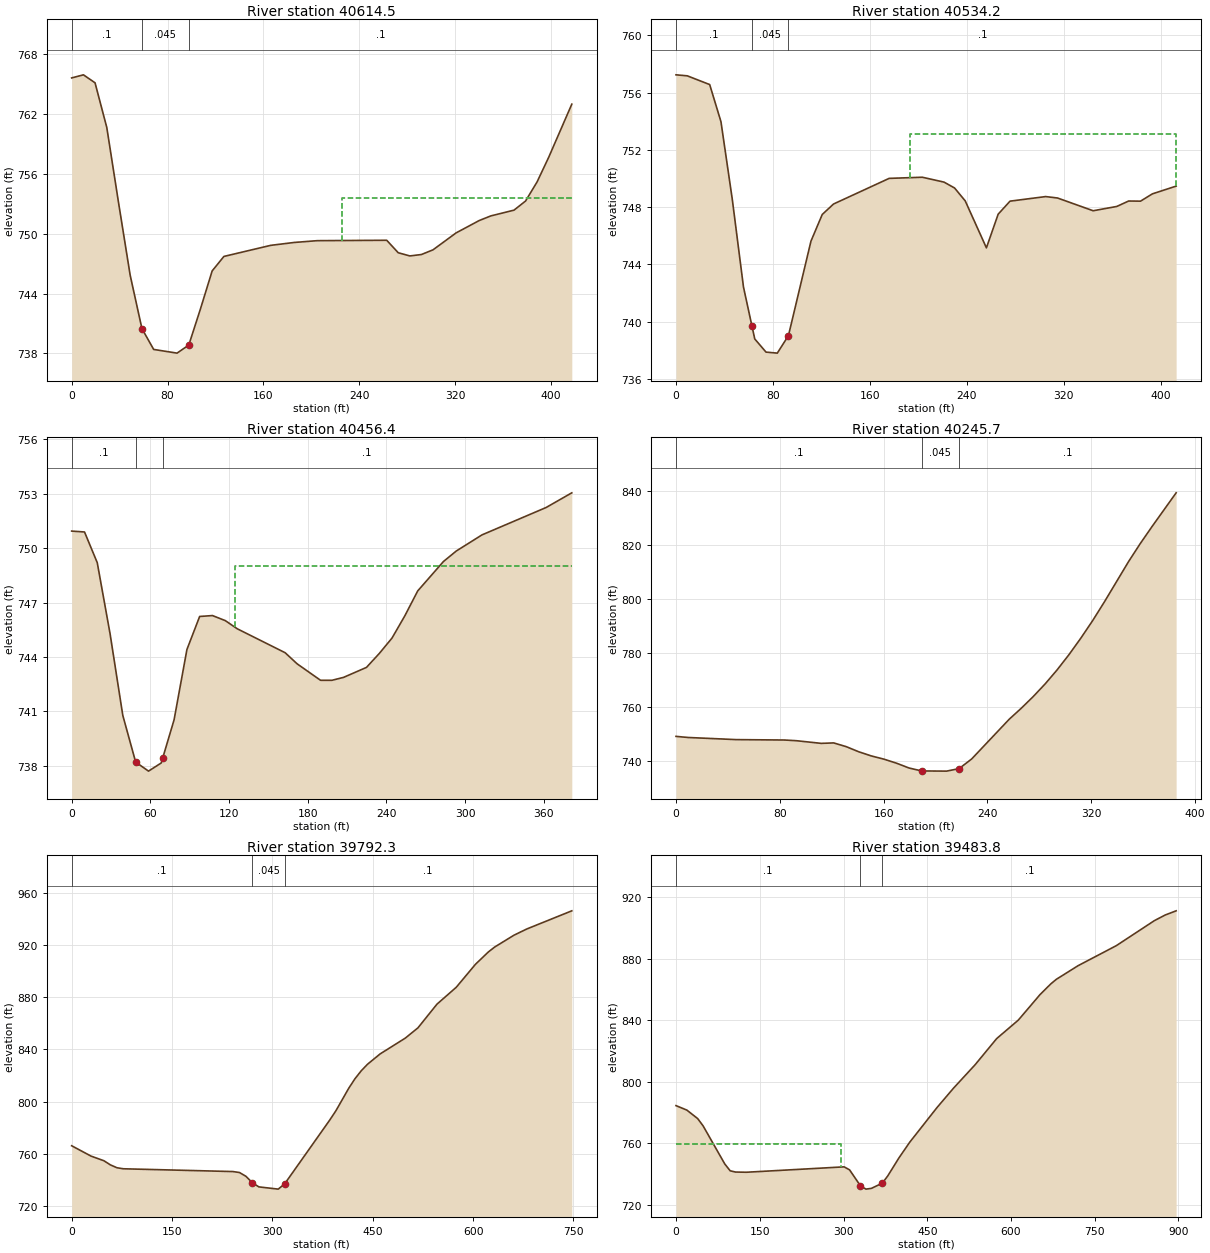
Type RM Length L Ch R = 1 ,40614.5 ,81.4,80.4,79.4
XS GIS Cut Line= 3
     1868565.639      518895.324     1868751.186      518892.069
      1868981.22      518864.942
#Sta/Elev= 29
       0  765.61     9.8  765.92    19.5  765.12    29.3  760.64    39.1  753.11
    48.8  745.84    58.6  740.49    68.4   738.4    87.9  738.03    97.7  738.84
   107.4  742.45   117.2  746.27     127  747.72     166  748.83   185.6  749.12
   204.9   749.3   262.8  749.34   272.4  748.09   282.1  747.77   291.7  747.91
   301.4  748.38   320.7  750.08     340  751.32   349.6  751.78     369  752.36
   378.6  753.27   388.2  755.18   397.9  757.65   417.2  762.98
#Mann= 3 , 0 , 0
       0      .1       0    58.6    .045       0    97.7      .1       0
#XS Ineff= 2 , 0
                          225.21          753.55
Permanent Ineff=
       F       F
Bank Sta=58.6,97.7
XS Rating Curve= 0 ,0
Exp/Cntr=0.3,0.1

Type RM Length L Ch R = 1 ,40534.2 ,77.8,77.8,77.9
XS GIS Cut Line= 5
     1868573.802      518978.812     1868722.034      518969.157
     1868785.643      518975.404      1868827.67      518987.331
     1868960.567       519070.25
#Sta/Elev= 30
       0  757.24     9.3  757.17    27.8  756.56    37.1  753.97    46.4  748.58
    55.7  742.42    62.6739.7342      65   738.8    74.3  737.88    83.6  737.81
    92.8  739.03   111.4  745.63   120.7  747.49     130  748.22   175.9  750.01
   203.3  750.09   221.2  749.75   229.9  749.34   238.7  748.44   256.2  745.16
   265.9  747.51   275.7  748.42   305.1  748.74   314.9  748.64   344.3  747.75
   363.8  748.05   373.6  748.43   383.4  748.42   393.2  748.93   412.8  749.47
#Mann= 3 , 0 , 0
       0      .1       0    62.6    .045       0    92.8      .1       0
#XS Ineff= 2 , 0
                          192.99          753.08
Permanent Ineff=
       F       F
Bank Sta=62.6,92.8
XS Rating Curve= 0 ,0
Exp/Cntr=0.3,0.1

Type RM Length L Ch R = 1 ,40456.4 ,187.3,210.7,232.9
XS GIS Cut Line= 5
     1868605.696      519053.443     1868722.602      519045.829
     1868786.211      519052.076     1868828.238      519064.003
     1868961.135      519146.922
#Sta/Elev= 30
       0  750.94     9.8  750.89    19.5   749.2    29.3  745.27      39  740.77
    48.8   738.2    58.6   737.7    68.3  738.15    69.4738.4172    78.1  740.53
    87.9  744.41    97.6  746.23   107.4  746.28   117.2     746   126.3  745.55
   162.8  744.23   171.9  743.62   189.8  742.71   198.5  742.71   207.3  742.87
   224.8  743.42   234.6  744.19   244.3  745.04   254.1  746.27   263.9  747.64
   283.5  749.26   293.3  749.84   312.9  750.73   361.8  752.24   381.4  753.05
#Mann= 3 , 0 , 0
       0      .1       0    48.8    .045       0    69.4      .1       0
#XS Ineff= 2 , 0
                          124.65          749.02
Permanent Ineff=
       F       F
Bank Sta=48.8,69.4
XS Rating Curve= 0 ,0
Exp/Cntr=0.3,0.1

Type RM Length L Ch R = 1 ,40245.7 ,420.2,453.3,487.4
XS GIS Cut Line= 4
      1868593.85      519075.445     1868610.126      519176.357
     1868705.081      519298.298     1868720.804      519425.923
#Sta/Elev= 30
       0     749     9.3  748.59    46.5   747.8    83.6  747.65    92.9  747.39
   111.9  746.41   121.5  746.58   131.2  745.19   140.8   743.3   150.5  741.76
   160.2  740.57   169.8  739.09   179.5   737.3   189.2   736.2   208.5  736.13
   218.1  737.05   227.8  740.62   256.8  755.36     266  759.39   275.1  763.66
   284.3  768.35   293.5  773.52   302.7  779.19   311.9  785.34   321.1   791.9
   330.2  798.88   348.6  813.63   357.8  820.44     367  826.83   385.4   839.2
#Mann= 3 , 0 , 0
       0      .1       0   189.2    .045       0   218.1      .1       0
Bank Sta=189.2,218.1
XS Rating Curve= 0 ,0
Exp/Cntr=0.3,0.1

Type RM Length L Ch R = 1 ,39792.3 ,303.1,308.6,314
XS GIS Cut Line= 4
     1868518.981      518864.942     1868239.311      519116.747
     1868224.927      519276.183     1868299.797      519473.666
#Sta/Elev= 30
       0  766.04      29  758.07    48.2  754.53    57.9  751.34    67.6  749.16
    77.2  748.35   241.2  746.21   250.9  745.46   260.5  742.55   270.2   737.6
   279.8  734.44   308.8  732.72   318.4  736.77   385.7  785.73   395.2   793.1
     414  810.07   423.4  817.47   432.8   823.6   442.2  828.63   461.1  836.59
   498.7  848.72   517.6   856.6     546  874.78   574.8  887.74   603.6  905.43
   622.8  914.87   632.4  918.72   661.2  927.79   680.4  932.57   747.6   946.5
#Mann= 3 , 0 , 0
       0      .1       0   270.2    .045       0   318.4      .1       0
Bank Sta=270.2,318.4
XS Rating Curve= 0 ,0
Exp/Cntr=0.3,0.1

Type RM Length L Ch R = 1 ,39483.8 ,302.2,311.2,320
XS GIS Cut Line= 5
     1868381.177      518608.865     1868184.451      518781.788
     1867977.414       518892.79     1867846.827      519022.864
     1867712.774      519190.463
#Sta/Elev= 30
       0  784.43    19.4  781.53    38.8  776.01    48.5  771.28    87.3  746.53
      97  742.05   106.7  741.23   126.1   741.1   301.1  744.61   310.9  742.64
   330.4  732.26   340.2  730.12     350  730.62   369.6  734.01   379.4  738.79
     399  750.27   418.5  760.58   467.5  783.19   496.8  795.69   535.6  810.98
   574.4  828.06   613.2  840.09     652  856.66   671.4  863.65   681.2   866.6
   720.2  875.47   788.5  888.46   856.8  904.76   876.3  908.45   895.8  911.15
#Mann= 3 , 0 , 0
       0      .1       0   330.4    .045       0   369.6      .1       0
#XS Ineff= 2 , 0
          294.62  759.17
Permanent Ineff=
       F       F
Bank Sta=330.4,369.6
XS Rating Curve= 0 ,0
Exp/Cntr=0.3,0.1