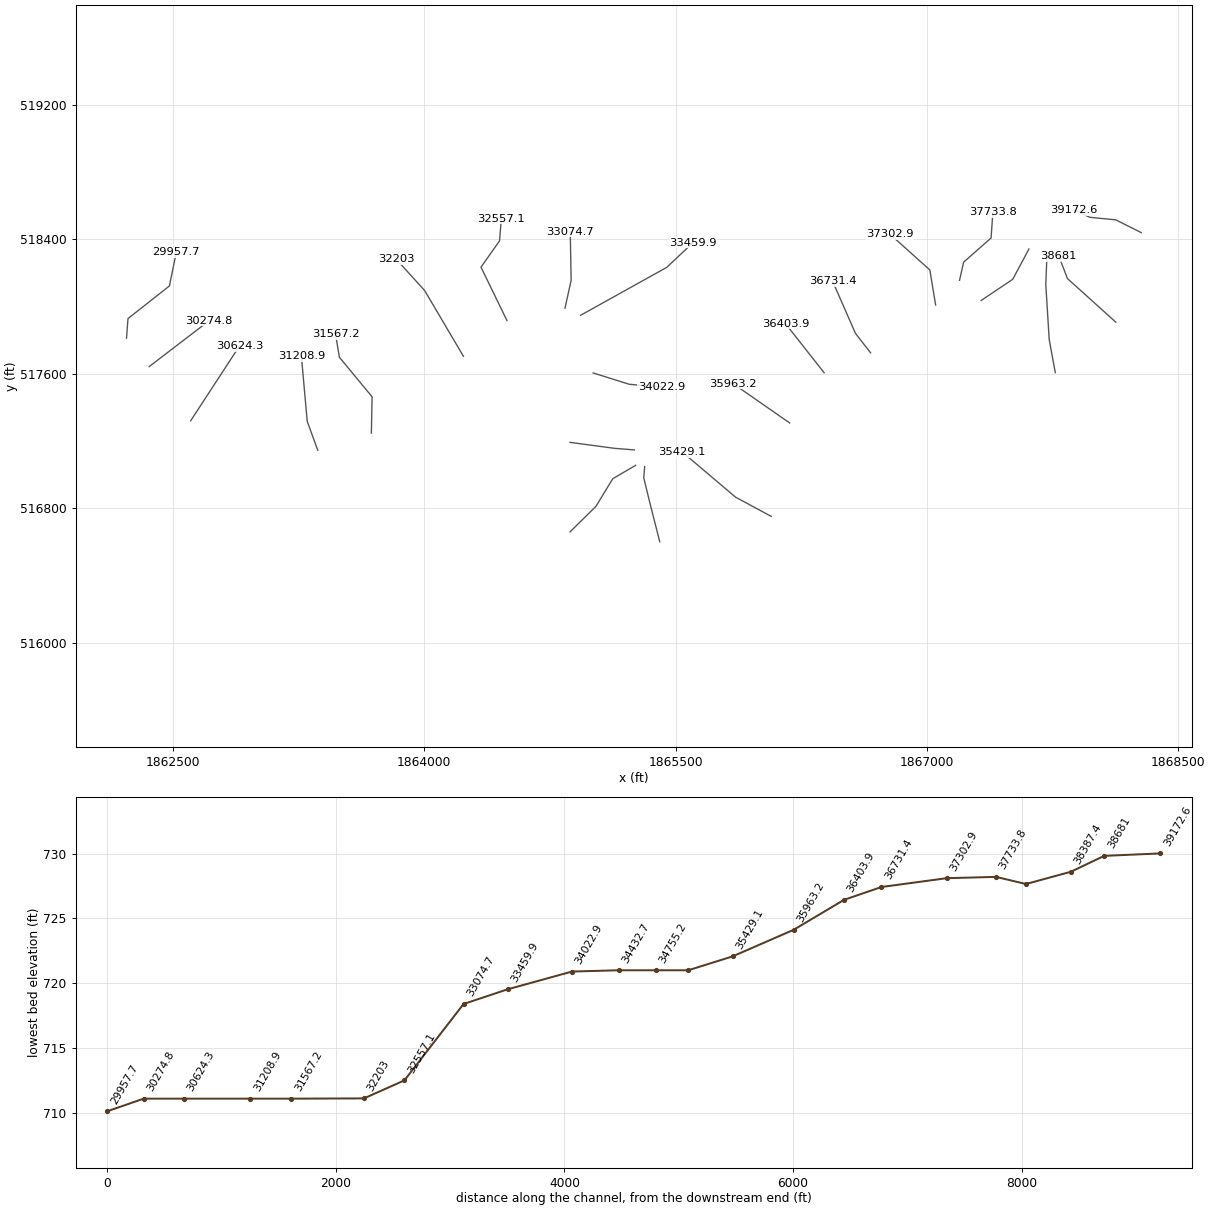
HEC-RAS study FALLINGRCR.prj: FALLINGRCR

--- FALLINGRCR.g01 (geometry) --- (continued)

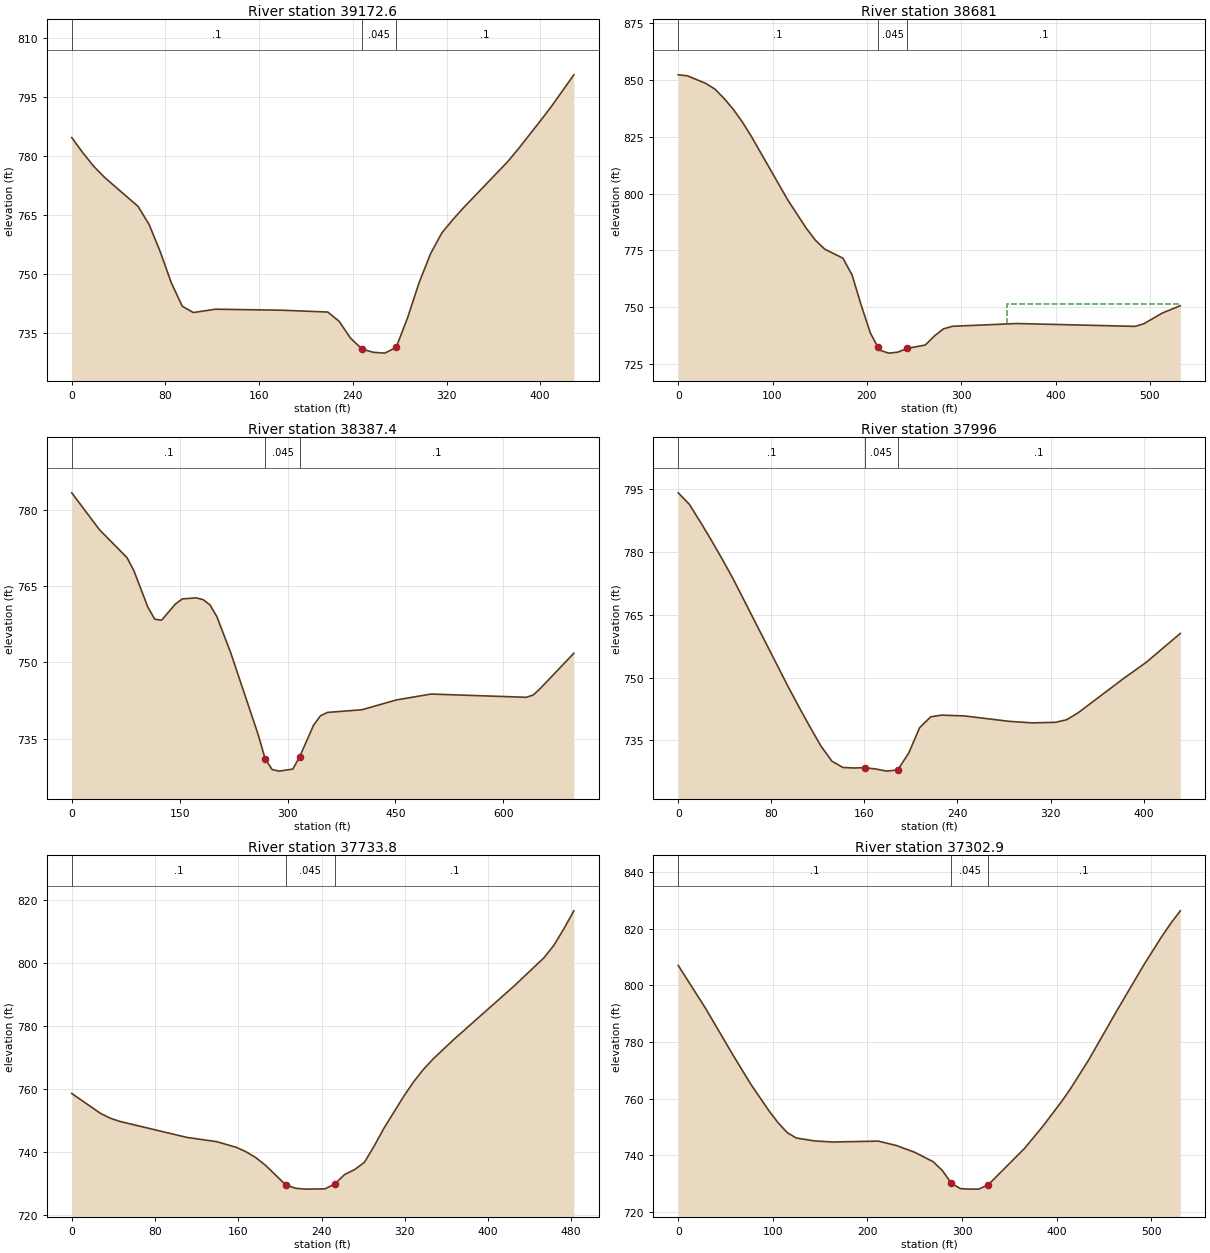
Type RM Length L Ch R = 1 ,39172.6 ,506,491.6,477.2
XS GIS Cut Line= 4
     1868280.265      518439.595     1868128.356      518515.549
     1867973.191       518530.74     1867879.875      518574.143
#Sta/Elev= 30
       0  784.67     9.4  780.83    18.9  777.33    28.3  774.49    56.6  767.22
      66  762.65    75.5  755.77    84.9  747.91    94.4  741.89   103.8   740.3
   122.7  741.15   179.6  740.89   218.6  740.43   228.3  738.09     238  733.81
   247.8  731.04   257.5  730.22   267.3  730.01     277  731.46   286.8  739.03
   296.5  747.81   306.3  755.19     316  760.49   325.8  764.01   335.1  767.07
   372.5  778.65   381.9  782.02   400.6  789.08     410  792.75   428.7  800.58
#Mann= 3 , 0 , 0
       0      .1       0   247.8    .045       0     277      .1       0
Bank Sta=247.8,277
XS Rating Curve= 0 ,0
Exp/Cntr=0.3,0.1

Type RM Length L Ch R = 1 ,38681   ,311.2,293.5,275.9
XS GIS Cut Line= 3
     1868128.356      517906.826     1867839.727      518166.157
     1867787.644      518300.706
#Sta/Elev= 30
       0  852.31     9.7  851.88    29.1  848.56    38.8  846.06    48.5  841.97
    58.2  837.22    67.9  831.61    77.6  825.16   116.4  797.05   135.8  784.77
   145.5  779.49   155.2  775.61   174.6  771.61   184.3  764.24     194   750.9
   203.7  738.68   211.9732.2975   213.4  731.13   223.1  729.82   232.8  730.24
   242.5   731.9   261.9  733.38   271.6  737.38   281.3  740.53     291  741.64
   358.9  742.85   484.2   741.6   493.8  742.76   513.1  747.45   532.3  750.71
#Mann= 3 , 0 , 0
       0      .1       0   211.9    .045       0   242.5      .1       0
#XS Ineff= 2 , 0
                          348.44           751.5
Permanent Ineff=
       F       F
Bank Sta=211.9,242.5
XS Rating Curve= 0 ,0
Exp/Cntr=0.3,0.1

Type RM Length L Ch R = 1 ,38387.4 ,414.9,391.5,368
XS GIS Cut Line= 4
     1867767.028      517606.261      1867730.63      517804.667
     1867710.371      518130.497     1867717.124      518300.164
#Sta/Elev= 30
       0  783.36    38.4  776.12    76.8  770.61    86.4  768.02   105.7  760.89
   115.3  758.49   124.9   758.3   144.1  761.48   153.7  762.48   172.9  762.69
   182.5  762.35   192.1  761.32   201.7  758.99   220.9  751.92   259.3  735.71
   268.9  730.97   278.5  728.91   288.1  728.59   307.3  728.99   316.9  731.43
   336.1  737.62   345.7  739.48   355.3  740.14   403.4  740.67   451.4   742.6
   499.4  743.76   631.9  743.12   641.4  743.56   650.8  744.77     698  751.79
#Mann= 3 , 0 , 0
       0      .1       0   268.9    .045       0   316.9      .1       0
Bank Sta=268.9,316.9
XS Rating Curve= 0 ,0
Exp/Cntr=0.3,0.1

Type RM Length L Ch R = 1 ,37996   ,259.2,262.1,265.1
XS GIS Cut Line= 3
     1867324.609      518035.955     1867512.847      518161.729
     1867609.921       518342.37
#Sta/Elev= 30
       0   794.2     9.4  791.51    18.9  787.29    28.3  782.94    37.7   778.4
    47.2  773.62    94.3  747.93   103.8  742.98   113.2  738.24   122.6  733.68
   132.1  730.02   141.5  728.53   150.9   728.4   160.4  728.48   169.8  728.16
   179.2  727.65   188.7  727.95   198.1  731.98   207.5  738.05     217  740.64
   226.4  741.04   245.9  740.85     285  739.54   304.5  739.19     324  739.32
   333.8  739.94   343.6  741.58   382.6  749.77   402.2  753.67   431.5  760.58
#Mann= 3 , 0 , 0
       0      .1       0   160.4    .045       0   188.7      .1       0
Bank Sta=160.4,188.7
XS Rating Curve= 0 ,0
Exp/Cntr=0.3,0.1

Type RM Length L Ch R = 1 ,37733.8 ,392.5,430.9,469.3
XS GIS Cut Line= 4
     1867195.459       518155.82     1867219.938      518263.867
     1867383.697      518407.368     1867394.671      518560.997
#Sta/Elev= 30
       0  758.52    27.7  752.19    36.9   750.7    46.2  749.66   110.8  744.58
   139.2  743.25   158.1  741.45   167.6  740.02     177  738.16   186.5  735.66
   205.4  729.62   214.9  728.47   224.4   728.2   243.3  728.28   252.8  729.84
   262.2  732.83   271.7  734.37   281.2  736.68   290.7   741.9   300.1  747.57
   319.1  757.65   328.5  762.22   338.2  766.24   347.8  769.64     367  775.59
   424.8   792.5   453.7   801.5   463.3  805.47   472.9   810.7   482.5  816.41
#Mann= 3 , 0 , 0
       0      .1       0   205.4    .045       0   252.8      .1       0
Bank Sta=205.4,252.8
XS Rating Curve= 0 ,0
Exp/Cntr=0.3,0.1

Type RM Length L Ch R = 1 ,37302.9 ,581.2,571.5,561.8
XS GIS Cut Line= 3
     1867052.802      518008.943     1867018.194      518217.441
     1866780.206      518430.385
#Sta/Elev= 30
       0  807.02    28.8  791.93    57.6  775.56    76.8  765.06    96.1  755.65
   105.7  751.47   115.3  748.01   124.9  746.12   144.1  745.11   163.3  744.72
   211.4  745.04   230.7  743.48   250.1  741.08   269.4  737.78   279.1   734.7
   288.8  730.12   298.4  728.26   308.1   728.1   317.8  728.13   327.5  729.58
   366.2  742.52   385.5  750.32   404.9  758.86   414.6   763.5   433.9  773.71
     463  790.69     492  807.13   511.3  817.33     521  822.04   530.7  826.28
#Mann= 3 , 0 , 0
       0      .1       0   288.8    .045       0   327.5      .1       0
Bank Sta=288.8,327.5
XS Rating Curve= 0 ,0
Exp/Cntr=0.3,0.1

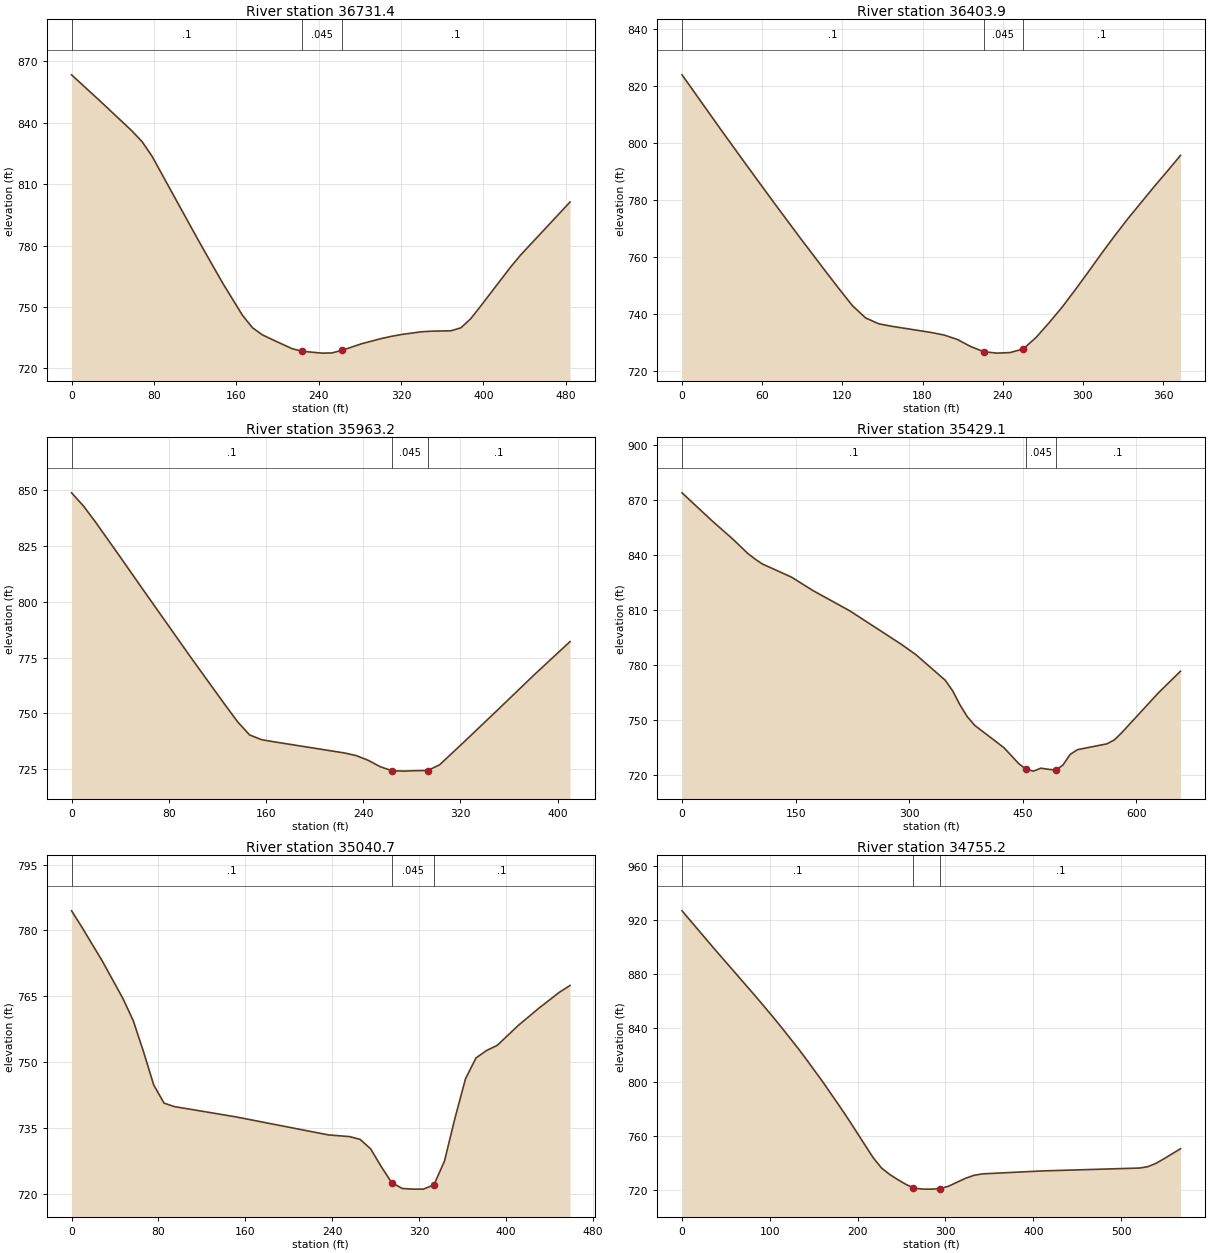
Type RM Length L Ch R = 1 ,36731.4 ,321.7,327.4,333.1
XS GIS Cut Line= 3
     1866664.508      517724.475     1866574.187       517840.12
     1866438.284      518149.067
#Sta/Elev= 30
       0  863.46    29.4  849.85    58.7  836.02    68.5  830.78    78.3  823.55
   117.4   787.8   127.2  778.95   146.7  761.72     166  745.91   175.7  739.85
   185.3  736.37     195  734.04   214.2  729.59   223.9  728.34   243.2  727.42
   252.8  727.51   262.5  728.75   281.7     732     301  734.56   310.7  735.63
   320.3  736.51   339.6  737.84   349.2  738.14   368.5  738.34   378.2   739.8
   387.8  744.29   397.5  750.48   426.4  769.46     436  775.27   484.2  801.29
#Mann= 3 , 0 , 0
       0      .1       0   223.9    .045       0   262.5      .1       0
Bank Sta=223.9,262.5
XS Rating Curve= 0 ,0
Exp/Cntr=0.3,0.1

Type RM Length L Ch R = 1 ,36403.9 ,434.1,440.8,447.4
XS GIS Cut Line= 2
     1866387.158      517605.792     1866156.045       517898.66
#Sta/Elev= 30
       0  823.95    29.4  804.54    49.1  791.78    68.7  779.22    88.4  766.82
     108  754.75   117.8   748.8   127.6  743.04   137.4  738.77   147.3  736.69
   157.1  735.83   186.5  733.67   196.4  732.74   206.2   731.2     216  728.75
   225.8  726.94   235.6  726.43   245.4  726.62   255.3  727.86   265.1  731.97
   274.9  737.15   284.7  742.66   294.5  748.73   304.4  755.07   314.2  761.47
     324  767.65   333.8  773.58   353.4  784.78   363.3  790.21   373.1  795.72
#Mann= 3 , 0 , 0
       0      .1       0   225.8    .045       0   255.3      .1       0
Bank Sta=225.8,255.3
XS Rating Curve= 0 ,0
Exp/Cntr=0.3,0.1

Type RM Length L Ch R = 1 ,35963.2 ,536.3,534.1,531.9
XS GIS Cut Line= 2
     1866181.942      517306.763     1865844.835      517540.387
#Sta/Elev= 25
       0  848.92     9.8     843    19.5  835.96    39.1  820.87    58.6  805.67
    97.6  775.54   117.2  760.71     127  753.35   136.7  746.19   146.5  740.35
   156.2  738.25     166  737.32   224.6  732.26   234.4  731.06   244.1  728.98
   253.9  726.13   263.7  724.29   273.4  724.12   283.2  724.32     293   724.4
   302.7   726.9   322.3  736.86   351.6  752.07   380.8  767.36   410.2  782.21
#Mann= 3 , 0 , 0
       0      .1       0   263.7    .045       0     293      .1       0
Bank Sta=263.7,293
XS Rating Curve= 0 ,0
Exp/Cntr=0.3,0.1

Type RM Length L Ch R = 1 ,35429.1 ,402.4,388.4,373.9
XS GIS Cut Line= 3
     1866070.952      516751.545     1865858.739      516865.485
     1865539.708      517134.668
#Sta/Elev= 30
       0   873.9    38.5  859.06    67.4  848.53    86.7  840.88    96.4  837.78
     106  835.11   144.5  827.92   173.4  820.46   221.6  809.51   289.4  791.32
   308.8  785.62   347.6  771.65   357.4  765.88   367.1  758.19   376.8  751.72
   386.5  747.06   425.3   734.8   444.7  726.16   454.4  723.11   464.1  722.07
   473.8  723.67   493.3  722.55     503  725.36   512.7  731.25   522.4  733.79
   561.2  736.96   570.9  739.09   580.6  742.99   629.2   764.8   658.3  776.58
#Mann= 3 , 0 , 0
       0      .1       0   454.4    .045       0   493.3      .1       0
Bank Sta=454.4,493.3
XS Rating Curve= 0 ,0
Exp/Cntr=0.3,0.1

Type RM Length L Ch R = 1 ,35040.7 ,303.4,285.5,267.6
XS GIS Cut Line= 4
     1865405.829      516600.575     1865347.435      516829.879
     1865310.404      516980.849     1865316.101      517047.789
#Sta/Elev= 30
       0  784.45     9.5  780.73    28.4  772.96    47.3  764.46    56.8  759.41
    66.2  752.38    75.7  744.73    85.2   740.6    94.6  739.82   151.4  737.47
   236.6  733.36     256  732.98   265.8  732.34   275.5  730.19   285.2  726.16
   294.9  722.48   304.6  721.15   314.3     721   324.1     721   333.8  721.97
   343.5  727.37   353.2   737.2   362.9  746.16   372.6  750.92   382.4  752.62
   392.1  753.77   411.3  758.28   430.5  762.25   449.6  765.92   459.2  767.43
#Mann= 3 , 0 , 0
       0      .1       0   294.9    .045       0   333.8      .1       0
Bank Sta=294.9,333.8
XS Rating Curve= 0 ,0
Exp/Cntr=0.3,0.1

Type RM Length L Ch R = 1 ,34755.2 ,348.7,322.5,296.3
XS GIS Cut Line= 4
     1864870.312      516658.969     1865025.555      516811.364
     1865125.252      516975.152      1865261.98       517054.91
#Sta/Elev= 30
       0  926.53    37.8  897.71    85.1   862.4     104  847.84   113.5  840.26
   132.4  824.77   141.9  816.57   160.8  799.74   179.7  781.97   189.2  772.82
   217.5  744.37   227.1  736.63   236.7  731.74   246.3  727.78   255.9  724.16
   263.3722.1404   265.5  721.54   275.1     721   284.6     721   294.2  721.37
   303.8  723.26     323  729.06   332.6  731.23   342.2  732.27   409.3  734.42
     521  736.57   530.3  737.57   539.6  739.99     549   743.5   567.6  750.84
#Mann= 3 , 0 , 0
       0      .1       0   263.3    .045       0   294.2      .1       0
Bank Sta=263.3,294.2
XS Rating Curve= 0 ,0
Exp/Cntr=0.3,0.1

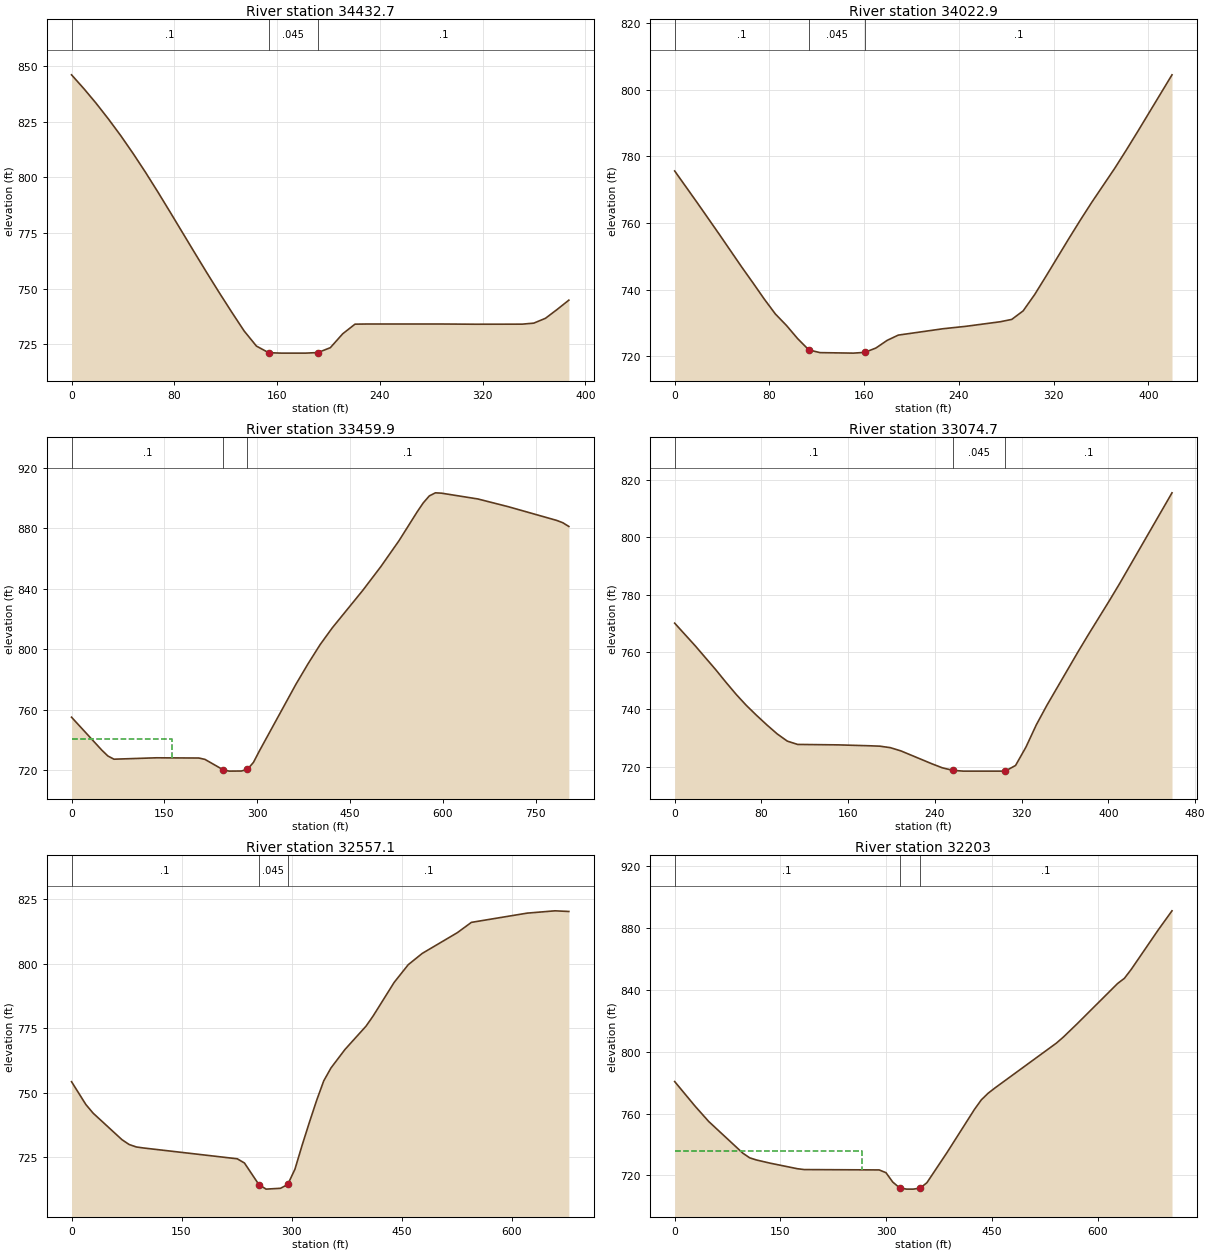
Type RM Length L Ch R = 1 ,34432.7 ,413.6,409.8,405.9
XS GIS Cut Line= 3
     1864870.312      517191.638     1865136.646      517156.031
       1865254.8      517146.718
#Sta/Elev= 30
       0  846.18     9.6  839.97    19.2  833.35    28.8  826.25    38.4  818.76
      48  810.75    57.6  802.33    67.2  793.51    76.8  784.42      96  766.02
   105.6  756.92   115.2  748.03   124.8  739.38   134.4  730.96     144  724.15
   153.5  721.19   163.1     721   182.3     721   191.9  721.26   201.5  723.45
   211.1  729.68   220.7  734.03   230.3   734.1   286.9   734.1   314.3     734
   350.8  734.03   359.9  734.49     369  736.67   378.1  740.65   387.2  744.83
#Mann= 3 , 0 , 0
       0      .1       0   153.5    .045       0   191.9      .1       0
Bank Sta=153.5,191.9
XS Rating Curve= 0 ,0
Exp/Cntr=0.3,0.1

Type RM Length L Ch R = 1 ,34022.9 ,544.6,563,581.3
XS GIS Cut Line= 3
     1865008.464      517604.669     1865224.704      517536.999
     1865417.385      517521.409
#Sta/Elev= 30
       0  775.59    18.9  766.13    37.8   756.5    56.6  746.75    66.1     742
    75.5   737.2      85  732.66    94.4   729.2   103.8  725.26   113.3  721.86
   122.7  721.05     151   720.9   160.5  721.13   169.9  722.43   179.4  724.73
   188.8  726.31   226.6  728.22   245.9  728.95   274.9  730.32   284.6  731.02
   294.2  733.58   303.9  738.46   313.6  744.03   332.9  755.34   342.6  760.89
   352.2   766.2   371.6  776.42   381.2   781.8   390.9   787.4   419.9  804.45
#Mann= 3 , 0 , 0
       0      .1       0   113.3    .045       0   160.5      .1       0
Bank Sta=113.3,160.5
XS Rating Curve= 0 ,0
Exp/Cntr=0.3,0.1

Type RM Length L Ch R = 1 ,33459.9 ,360.6,385.2,409.8
XS GIS Cut Line= 3
     1864933.483      517947.627     1865447.806         518233.
     1865605.141       518380.57
#Sta/Elev= 30
       0  755.14      49  733.37    58.8  729.51    68.6  727.41   137.2  728.33
   205.9  728.18   215.7  727.28   245.1  720.41   254.9  719.53   274.5   719.6
   284.3  720.68   294.1  725.34   303.9  733.04   362.7  776.88   382.3  790.42
   401.9  803.12   421.5  814.16   470.6  838.82     500  854.61   529.4  871.75
   558.8  890.82   568.6  896.72   578.4  901.32   588.2  903.33     598   903.1
   656.8  899.28   705.8  894.19   784.3  885.11   794.1  883.58   803.9  881.11
#Mann= 3 , 0 , 0
       0      .1       0   245.1    .045       0   284.3      .1       0
#XS Ineff= 2 , 0
          162.89  740.42
Permanent Ineff=
       F       F
Bank Sta=245.1,284.3
XS Rating Curve= 0 ,0
Exp/Cntr=0.3,0.1

Type RM Length L Ch R = 1 ,33074.7 ,507.6,517.7,527.2
XS GIS Cut Line= 3
     1864840.167      517989.945     1864877.059       518155.96
     1864871.634      518444.589
#Sta/Elev= 30
       0  770.05    18.9  762.17    37.8  753.84    47.2  749.46    56.7   745.2
    66.1  741.34    75.6  737.84      85  734.55    94.5  731.41   103.9  728.87
   113.4  727.72   151.2  727.56   179.7  727.25   189.3  727.11   198.9  726.59
   208.6  725.47   237.4  720.94     247  719.54   256.7  718.66   266.3   718.4
   304.8   718.4   314.4  720.37     324   726.8   333.6   734.6   343.3  741.38
   372.1   760.1   381.8   766.2     401  777.95   410.6  784.01   458.7  815.55
#Mann= 3 , 0 , 0
       0      .1       0   256.7    .045       0   304.8      .1       0
Bank Sta=256.7,304.8
XS Rating Curve= 0 ,0
Exp/Cntr=0.3,0.1

Type RM Length L Ch R = 1 ,32557.1 ,352.2,354.1,355.8
XS GIS Cut Line= 4
      1864494.03       517916.16     1864338.865      518234.085
     1864449.542      518390.335     1864460.393      518522.714
#Sta/Elev= 30
       0   754.2    19.6  745.32    29.5  741.97    68.8  731.69    78.6  729.82
    88.4  728.87    98.3  728.47     226  724.28   235.8  722.64   255.5  714.25
   265.3  712.51     285  712.84   294.8  714.31   304.6  720.23   314.5  729.62
   324.3  738.41   334.1  746.86   343.9  754.53   353.8  759.55   372.9  766.72
   401.6  775.77   411.2  779.68   439.9  792.73   459.1   799.6   478.2  803.98
   526.1  812.03   545.2  816.02   621.1   819.6   659.1   820.5   678.1  820.25
#Mann= 3 , 0 , 0
       0      .1       0   255.5    .045       0   294.8      .1       0
Bank Sta=255.5,294.8
XS Rating Curve= 0 ,0
Exp/Cntr=0.3,0.1

Type RM Length L Ch R = 1 ,32203   ,632.3,635.8,639.3
XS GIS Cut Line= 3
      1864233.92      517704.066     1864002.493      518095.197
     1863833.223      518280.743
#Sta/Elev= 30
       0  780.76      29   764.8    48.4  754.86    96.7  734.41   106.4  731.39
     116  729.99   135.4  727.93     174  724.34   183.7  723.78   290.1  723.55
   299.8  721.77   309.4  715.69   319.1  711.97   328.8  711.13   338.4  711.12
   348.1  711.76   357.8  715.24   386.8   735.1   425.5  762.86   435.1  768.93
   444.8  773.23   454.5  776.65   541.4  805.59   551.1  809.41   570.4  817.88
   628.4  844.23     638  847.57   647.7  853.34   686.3  879.09   705.6  891.29
#Mann= 3 , 0 , 0
       0      .1       0   319.1    .045       0   348.1      .1       0
#XS Ineff= 2 , 0
          266.29     736
Permanent Ineff=
       F       F
Bank Sta=319.1,348.1
XS Rating Curve= 0 ,0
Exp/Cntr=0.3,0.1

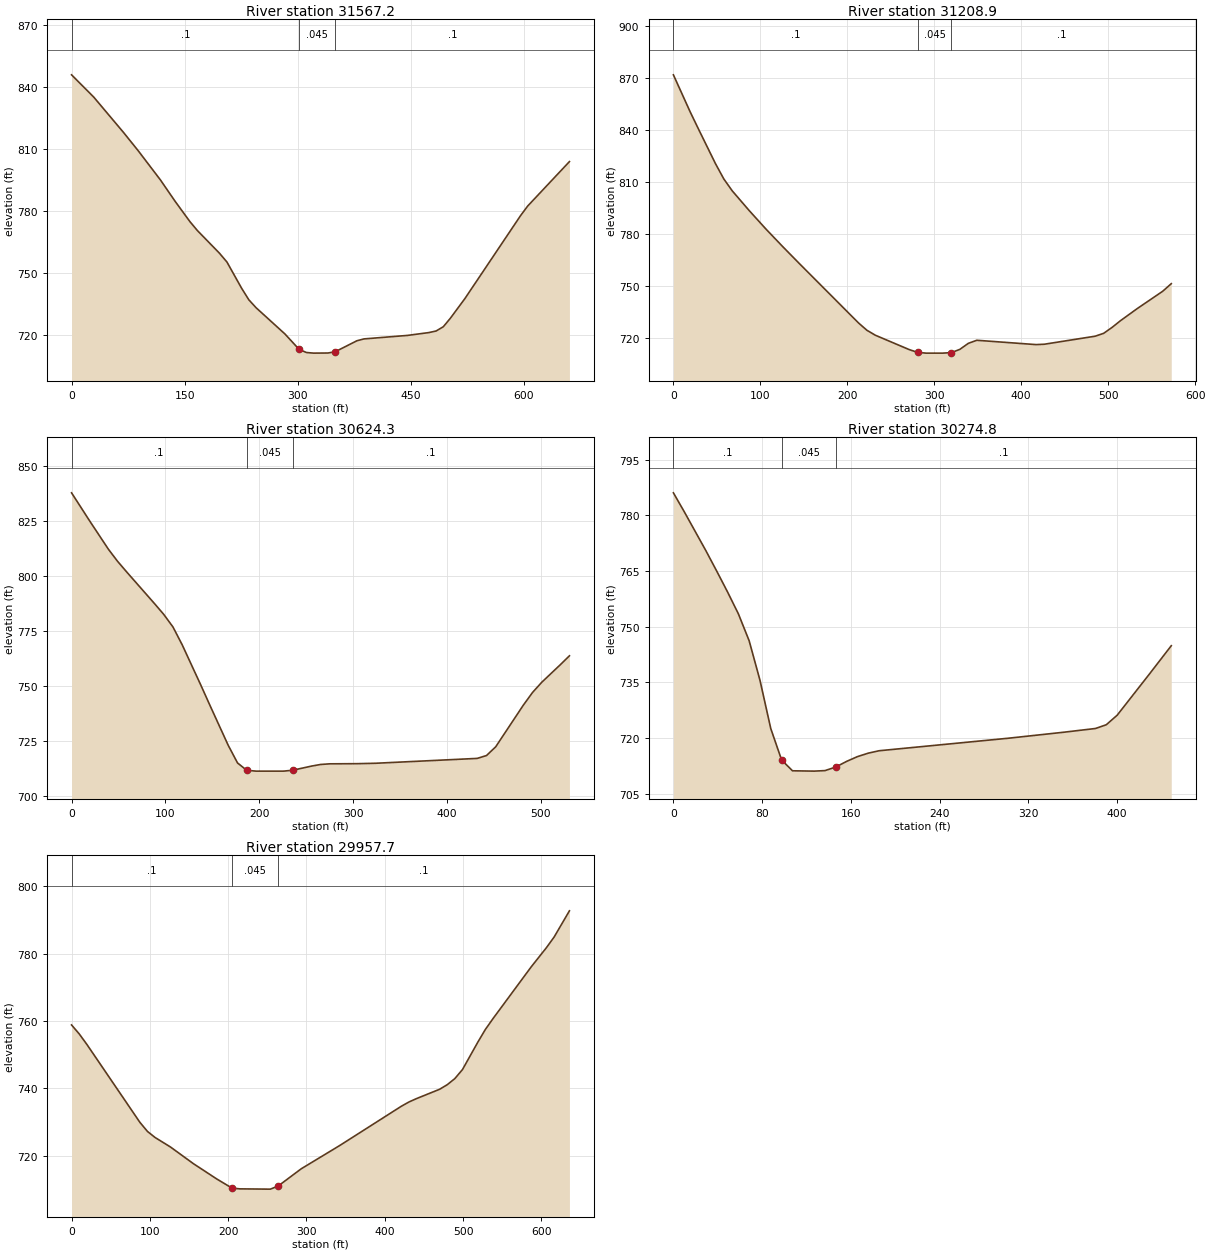
Type RM Length L Ch R = 1 ,31567.2 ,371.9,358.2,344.6
XS GIS Cut Line= 4
     1863684.568      517246.672     1863688.908      517462.601
     1863493.596      517698.061     1863470.809       517834.78
#Sta/Elev= 30
       0  845.72    29.4  834.96    68.7  817.95    88.4  809.01   117.8  794.93
   137.4  784.53   157.1  774.68   166.9  770.41   196.3   759.4   206.2  755.13
   225.5  742.55   235.1  736.94   244.6  733.13   282.9  720.43     302  712.88
   311.6   711.4   321.1   711.1   340.2  711.16   349.8  711.77   378.5  717.07
     388  717.98   445.4  719.66   474.1  721.04   483.6   721.8   493.2  723.87
   502.8  728.09   521.9  737.53   595.8  777.68   605.1  782.24   660.5  803.74
#Mann= 3 , 0 , 0
       0      .1       0     302    .045       0   349.8      .1       0
Bank Sta=302,349.8
XS Rating Curve= 0 ,0
Exp/Cntr=0.3,0.1

Type RM Length L Ch R = 1 ,31208.9 ,599.6,584.6,569.4
XS GIS Cut Line= 3
     1863364.473      517144.676     1863301.539      517317.202
     1863266.816      517704.572
#Sta/Elev= 30
       0  871.65    19.3  850.26      29  840.21    48.3   820.5      58  811.56
    67.7   804.7      87  793.44   106.3  782.75   125.6  772.61     145   762.7
   212.8  728.56   222.5  724.31   232.3  721.41   271.2  713.14   280.9  711.53
   290.6   711.1     310   711.1   319.8  711.41   329.5  713.29   339.2  716.75
   348.9  718.52     417  716.02   426.7  716.24   485.1  720.87   494.8  722.52
   504.5  725.93   514.2  729.82   533.7  736.88   562.8  746.81   572.6  751.16
#Mann= 3 , 0 , 0
       0      .1       0   280.9    .045       0   319.8      .1       0
Bank Sta=280.9,319.8
XS Rating Curve= 0 ,0
Exp/Cntr=0.3,0.1

Type RM Length L Ch R = 1 ,30624.3 ,357.2,349.6,341.9
XS GIS Cut Line= 2
     1862606.009      517320.457     1862896.808       517764.25
#Sta/Elev= 30
       0  837.72    19.6  824.74    39.3  812.04    49.1  806.53      59   801.6
    88.4  787.32    98.3  782.38   108.1  776.67   117.9  768.58   137.6  750.39
   147.4   741.1     167  722.81   176.9  714.81   186.7  711.48   196.5   711.1
     226   711.1   235.8  711.51   255.5  713.37   265.3  714.12   275.1  714.42
   304.6  714.49   324.2  714.68   432.3  716.89   442.2  718.19     452  722.15
   481.4  741.07   491.3   746.9   501.1  751.53   520.8  759.48   530.6  763.57
#Mann= 3 , 0 , 0
       0      .1       0   186.7    .045       0   235.8      .1       0
Bank Sta=186.7,235.8
XS Rating Curve= 0 ,0
Exp/Cntr=0.3,0.1

Type RM Length L Ch R = 1 ,30274.8 ,316.1,317.1,317.4
XS GIS Cut Line= 2
     1862358.613      517642.723     1862715.601      517915.075
#Sta/Elev= 25
       0  786.08     9.8  780.98    29.3  770.49      39  765.03    48.8  759.39
    58.6  753.48    68.3  746.24    78.1  735.55    87.8  722.58    97.6  714.09
   107.4  711.19   126.9   711.1   136.7  711.24   146.4   712.2   156.2  713.72
   165.9     715   175.7  715.94   185.5  716.59   302.6  719.98   351.4  721.56
   380.7  722.59   390.4   723.6   400.2  726.16   429.5  737.34     449  744.89
#Mann= 3 , 0 , 0
       0      .1       0    97.6    .045       0   146.4      .1       0
Bank Sta=97.6,146.4
XS Rating Curve= 0 ,0
Exp/Cntr=0.3,0.1

Type RM Length L Ch R = 1 ,29957.7 ,493.9,522,550.8
XS GIS Cut Line= 4
      1862222.98      517811.993      1862231.66      517928.096
     1862479.056      518122.323     1862520.289      518323.061
#Sta/Elev= 30
       0  758.82     9.7  756.18    19.4   753.1    87.3  729.93      97  727.23
   106.7  725.44   126.3  722.63   155.7  717.67   185.2  713.18   204.9  710.44
   214.7  710.21   250.2  710.13     254  710.13   263.9  711.05   293.4  716.17
   342.5  723.06   421.1  734.69     431  735.98   440.7  736.99     470  739.73
   479.8  741.09   489.5   742.9   499.3  745.59   518.8  753.67   528.5  757.47
   538.3   760.7   587.1  776.05   606.6  781.76   616.4  784.91   635.9  792.66
#Mann= 3 , 0 , 0
       0      .1       0   204.9    .045       0   263.9      .1       0
Bank Sta=204.9,263.9
XS Rating Curve= 0 ,0
Exp/Cntr=0.3,0.1