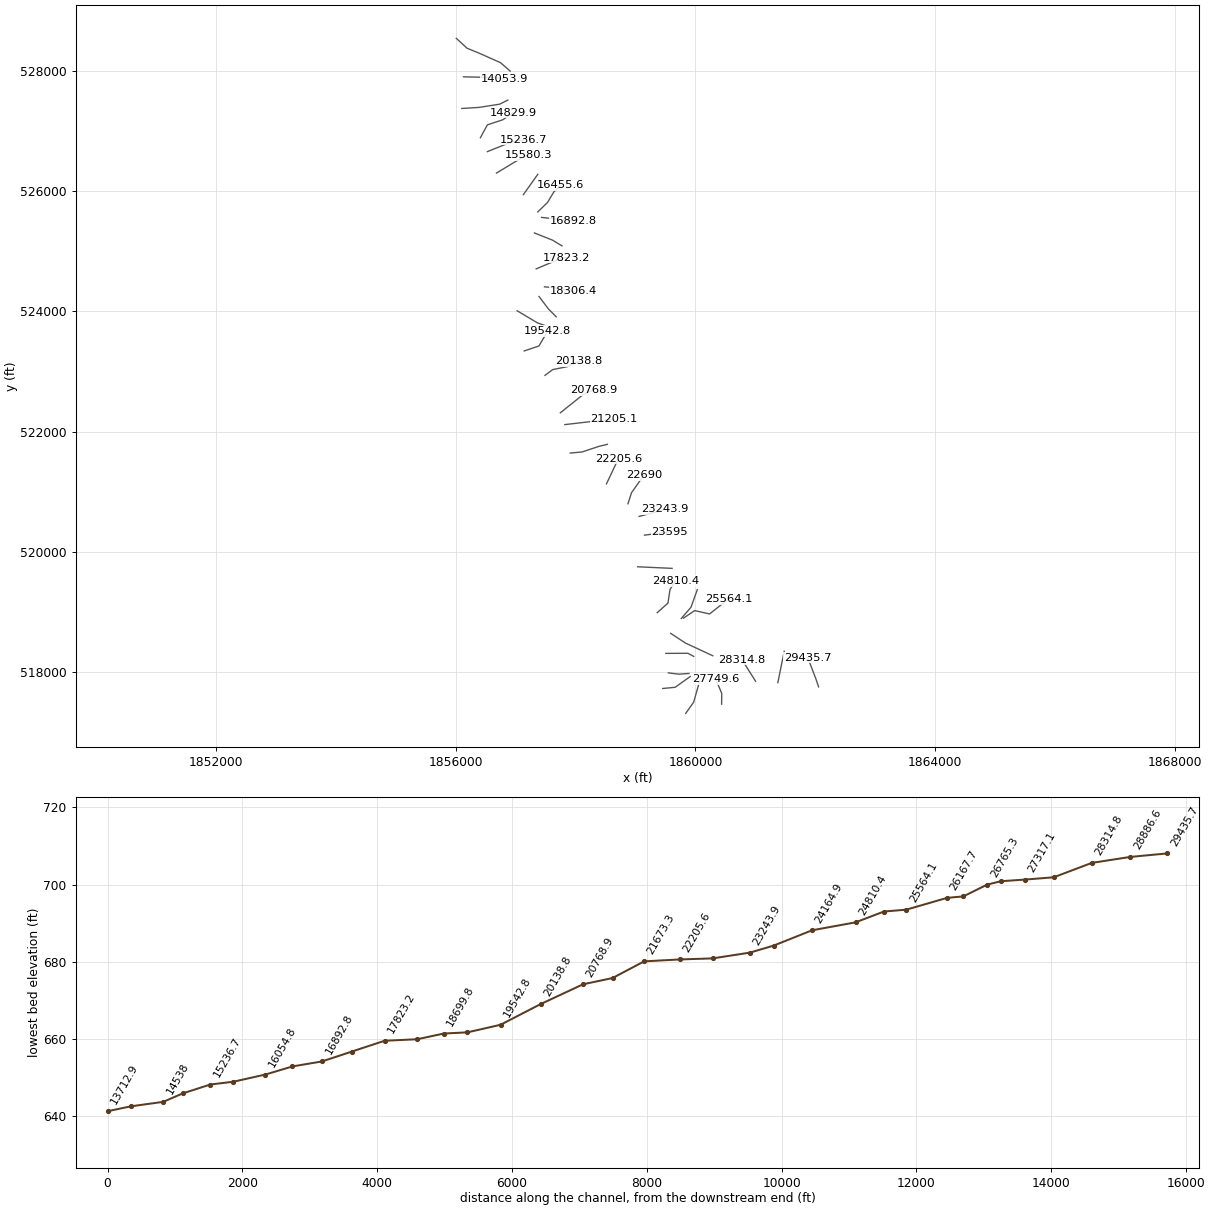
HEC-RAS study FALLINGRCR.prj: FALLINGRCR

--- FALLINGRCR.g01 (geometry) --- (continued)

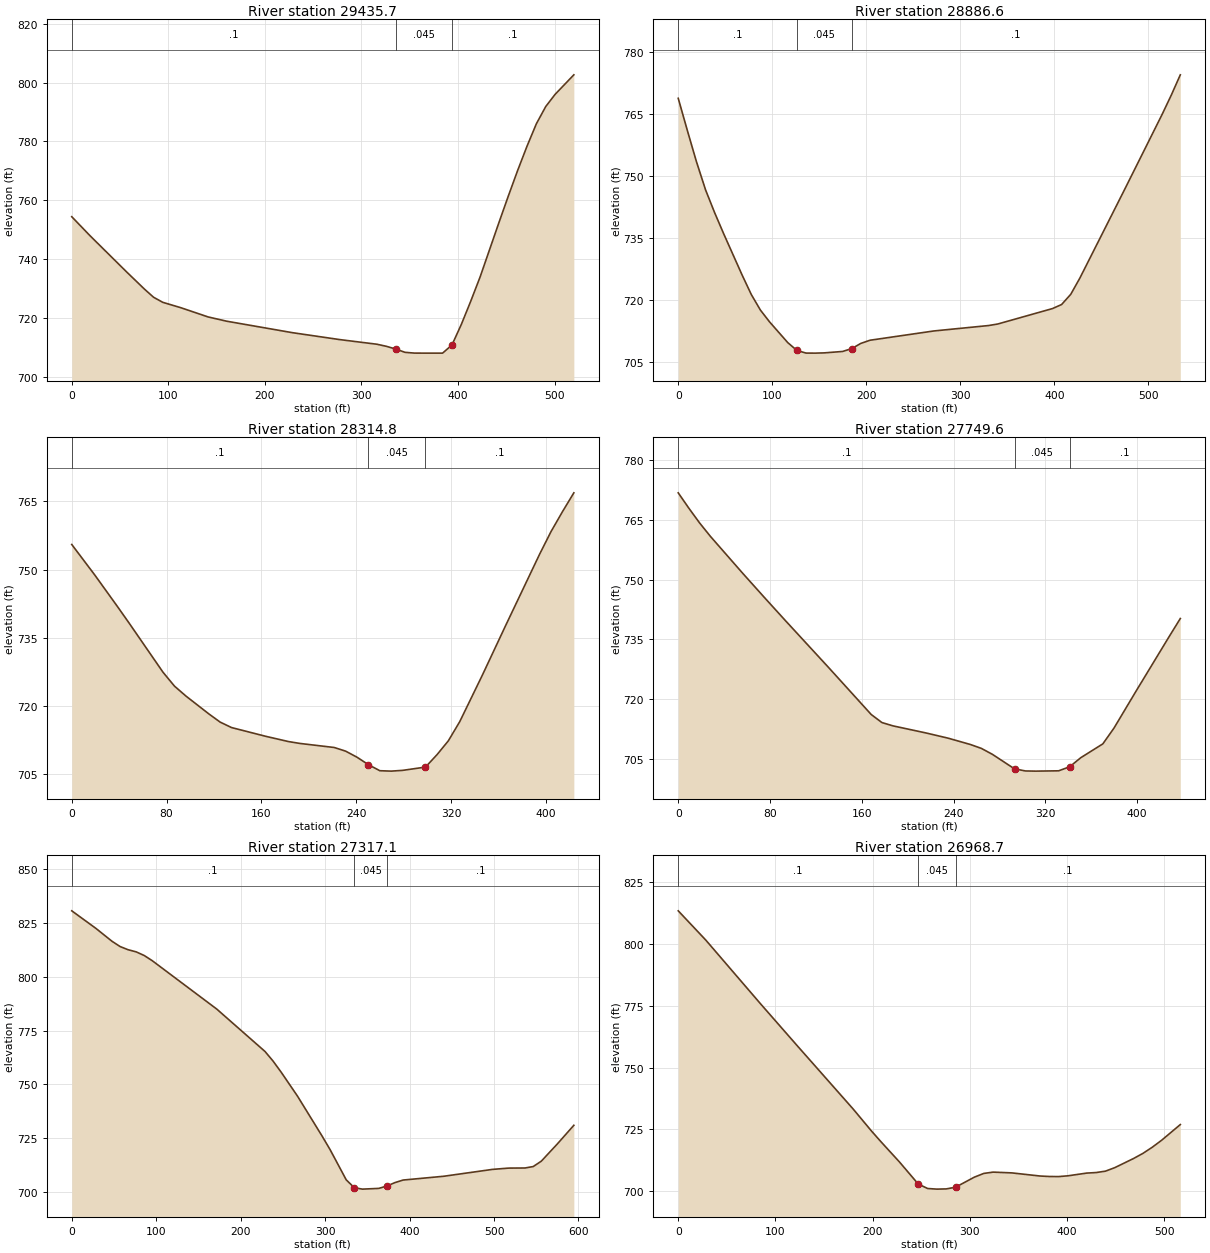
Type RM Length L Ch R = 1 ,29435.7 ,562,549.1,536.2
XS GIS Cut Line= 3
     1862053.709       517755.57      1862008.51      517889.369
     1861872.502      518242.766
#Sta/Elev= 30
       0  754.43    18.8  748.01    56.5  735.78    75.3  729.83    84.7  727.08
    94.2  725.36     113  723.52   141.2  720.39   160.6  718.93   228.6  715.04
   277.2  712.71     316  711.12   325.7  710.42   335.4   709.5   345.1  708.37
   354.8  708.11   364.5   708.1     384   708.1   393.7  710.88   403.4  717.86
   413.1   725.7   422.8  733.94   442.2  752.31   451.9  761.31   461.6  770.04
   471.4  778.37   481.1     786   490.8  791.85   500.5  795.99   519.9  802.62
#Mann= 3 , 0 , 0
       0      .1       0   335.4    .045       0   393.7      .1       0
Bank Sta=335.4,393.7
XS Rating Curve= 0 ,0
Exp/Cntr=0.3,0.1

Type RM Length L Ch R = 1 ,28886.6 ,554.1,571.8,589.1
XS GIS Cut Line= 2
      1861373.37      517825.014     1861480.792      518348.018
#Sta/Elev= 30
       0  768.71     9.7  760.94    19.4  753.39    29.1  746.58    38.8  741.05
    48.5  735.92      68  726.01    77.7  721.34    87.4  717.58    97.1  714.74
   116.5  709.72   126.2  707.84   135.9   707.2   145.6  707.19   155.3  707.25
   174.7  707.59   184.4  708.27   194.2  709.54   203.9   710.3   271.8  712.54
   330.1  713.85   339.8  714.22     398  717.95   407.7  718.93   417.4  721.39
   427.1  725.31   475.7  747.16   514.5   764.8   524.2  769.43   533.9  774.38
#Mann= 3 , 0 , 0
       0      .1       0   126.2    .045       0   184.4      .1       0
Bank Sta=126.2,184.4
XS Rating Curve= 0 ,0
Exp/Cntr=0.3,0.1

Type RM Length L Ch R = 1 ,28314.8 ,568.9,565.2,561.4
XS GIS Cut Line= 2
     1861002.763      517849.004     1860776.077       518206.98
#Sta/Elev= 30
       0  755.51    19.3  748.84    38.5  741.88    48.2  738.29      77   727.4
    86.7  724.34    96.3  722.17   115.6  718.25   125.2  716.43   134.8  715.23
   163.7   713.3     183  712.14   192.6  711.73   221.5  710.84   231.1  710.04
   240.8  708.69   250.4  707.05     260  705.73   269.6  705.64   279.3  705.81
   298.5  706.53   308.2  709.25   317.8  712.31   327.4  716.52   346.7  726.87
   365.9  737.54   394.8  753.37   404.4  758.33   414.1  762.73   423.7  766.88
#Mann= 3 , 0 , 0
       0      .1       0   250.4    .045       0   298.5      .1       0
Bank Sta=250.4,298.5
XS Rating Curve= 0 ,0
Exp/Cntr=0.3,0.1

Type RM Length L Ch R = 1 ,27749.6 ,447.8,432.5,417.3
XS GIS Cut Line= 3
     1860435.766       517468.48     1860438.186      517645.974
     1860337.618      517885.791
#Sta/Elev= 27
       0  771.79     9.3  767.91    18.7   764.2      28  760.87    56.1  751.62
    74.7  745.64    93.4  739.71   130.8  728.01   168.2  716.13   177.5  714.11
   187.1  713.28     216  711.49   235.3  710.18   254.6   708.6   264.2  707.62
   273.8  706.13   293.1  702.48   302.7  701.95   311.6  701.91   331.6  701.99
   341.2  703.01   350.9  705.29   370.1  708.76   379.8  712.72     399  721.98
   427.9   735.7   437.6  740.23
#Mann= 3 , 0 , 0
       0      .1       0   293.1    .045       0   341.2      .1       0
Bank Sta=293.1,341.2
XS Rating Curve= 0 ,0
Exp/Cntr=0.3,0.1

Type RM Length L Ch R = 1 ,27317.1 ,363.7,348.4,333
XS GIS Cut Line= 3
       1859836.7      517315.079     1859969.745      517501.196
     1860069.347      517853.075
#Sta/Elev= 30
       0  830.61    28.6  822.45    47.7  816.45    57.2  814.02    66.7  812.54
    76.3  811.54    85.8  809.85    95.3  807.44   171.6  784.99   228.8  765.27
   238.4  760.78     248  755.62   267.3  744.51   296.2  726.09   305.8  719.72
     325  705.62   334.6  701.95   344.3  701.31   363.5  701.65   373.1  702.75
   382.8  704.36   392.4  705.53   440.5  707.29   498.2  710.48   517.5  711.08
   536.7  711.13   546.4   711.8     556  714.31   575.2  722.41   594.5  730.97
#Mann= 3 , 0 , 0
       0      .1       0   334.6    .045       0   373.1      .1       0
Bank Sta=334.6,373.1
XS Rating Curve= 0 ,0
Exp/Cntr=0.3,0.1

Type RM Length L Ch R = 1 ,26968.7 ,220.1,203.4,186.6
XS GIS Cut Line= 3
     1859453.383      517728.562     1859660.761      517749.111
     1859912.311      517927.231
#Sta/Elev= 30
       0  813.32    28.4  801.48    85.2  775.53   123.1  758.54     180  733.25
   198.9  724.35   208.4  720.13   227.7  711.84   246.9  702.98   256.6  701.15
   266.2   700.9   275.8  700.99   285.4  701.68   304.7  705.74   314.4  707.24
     324  707.77   343.2  707.46   372.1   706.2   381.8     706   391.4  705.97
     401  706.28   420.3  707.38   429.9  707.59   439.6  708.16   449.2  709.58
   468.5  713.27   478.1  715.33   487.7  717.81   497.4  720.65   516.6  726.98
#Mann= 3 , 0 , 0
       0      .1       0   246.9    .045       0   285.4      .1       0
Bank Sta=246.9,285.4
XS Rating Curve= 0 ,0
Exp/Cntr=0.3,0.1

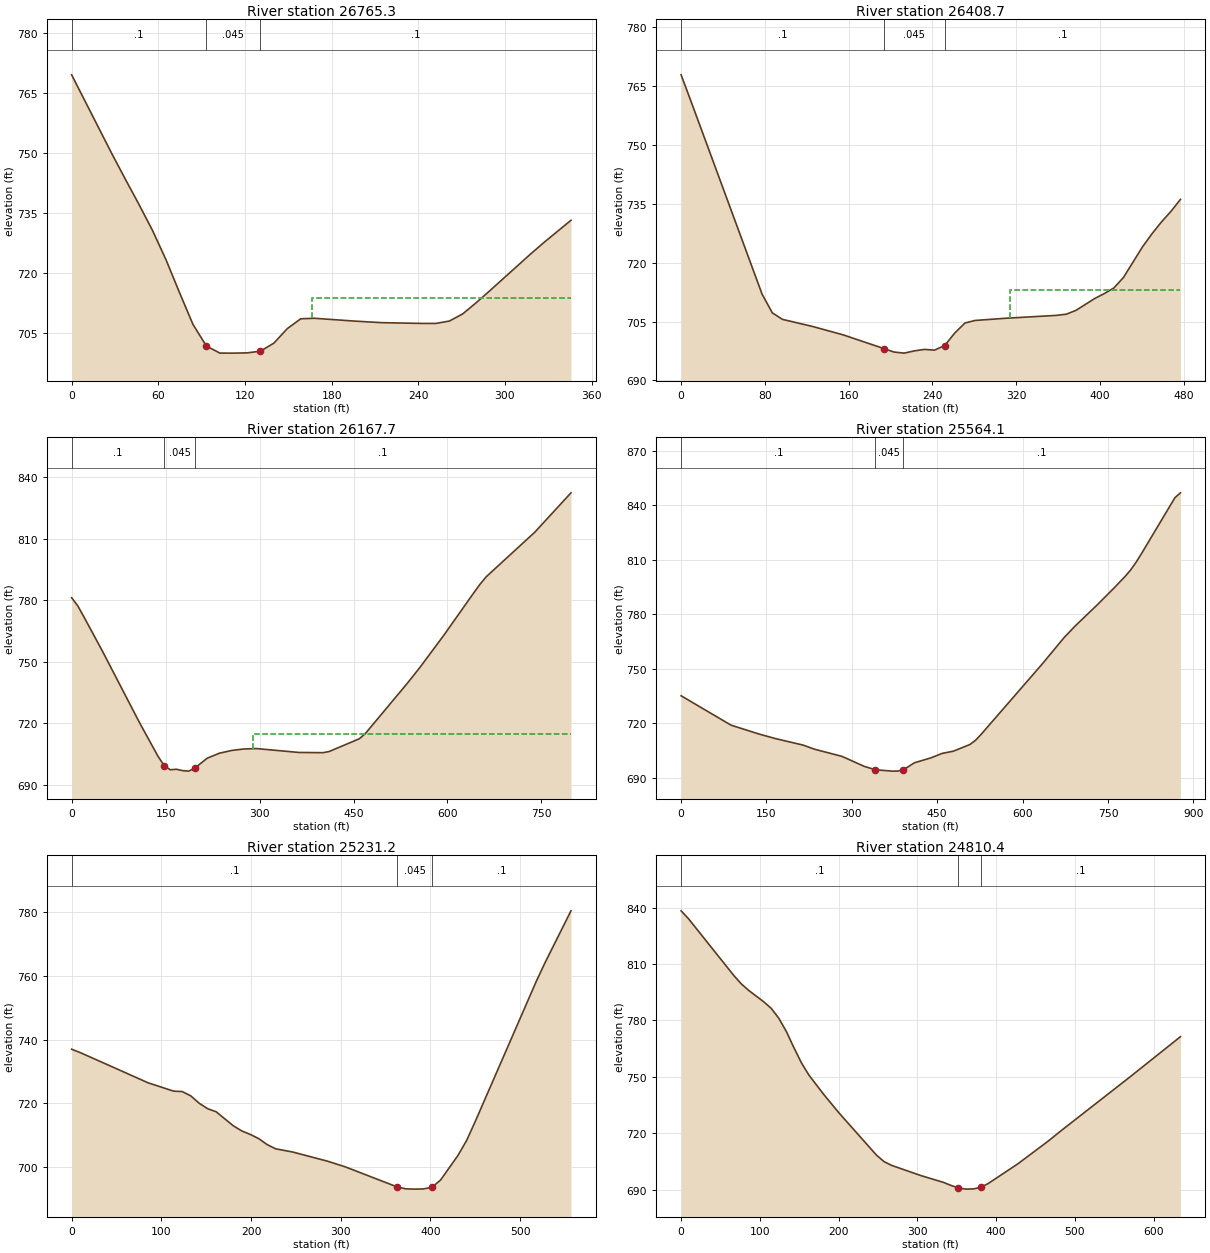
Type RM Length L Ch R = 1 ,26765.3 ,353.6,356.7,359.7
XS GIS Cut Line= 3
     1859547.346      517988.301     1859723.285       517966.49
     1859891.227      517978.849
#Sta/Elev= 28
       0  769.56      28  749.75    37.3  743.41    46.6   737.2      56  730.68
    65.3  723.39    74.6  715.23      84  707.21    93.3  701.81   102.6  700.04
     112  700.03   121.3  700.09   130.6   700.5     140  702.52   149.3  706.15
   158.6  708.61     168  708.74     196  708.03   214.7  707.64   242.8  707.45
   252.1  707.45   261.5  708.04   270.8  709.84   280.2  712.66   289.6  715.65
   317.6  724.75     327  727.68   345.7  733.22
#Mann= 3 , 0 , 0
       0      .1       0    93.3    .045       0   130.6      .1       0
#XS Ineff= 2 , 0
                          166.08          713.77
Permanent Ineff=
       F       F
Bank Sta=93.3,130.6
XS Rating Curve= 0 ,0
Exp/Cntr=0.3,0.1

Type RM Length L Ch R = 1 ,26408.7 ,254.3,240.9,227.6
XS GIS Cut Line= 3
     1859505.906      518312.552     1859873.778      518314.006
     1859969.745      518262.388
#Sta/Elev= 30
       0  767.83     9.7  760.91    77.4  711.94    87.1  707.22    96.8  705.56
   125.8  703.73   154.9   701.6   193.6  698.12   203.3  697.24     213  696.96
   222.7  697.53   232.3  697.91     242  697.72   251.7   698.9   261.4  702.11
   271.1  704.64   280.8  705.28   309.8  705.84   358.2  706.57   367.9  706.88
     377  707.85   395.1  710.89   404.2  712.14   413.3  713.57   422.4  716.23
   440.5  723.99   449.6  727.35   458.7  730.37   467.8  733.08   476.8  736.11
#Mann= 3 , 0 , 0
       0      .1       0   193.6    .045       0   251.7      .1       0
#XS Ineff= 2 , 0
                          314.09          713.07
Permanent Ineff=
       F       F
Bank Sta=193.6,251.7
XS Rating Curve= 0 ,0
Exp/Cntr=0.3,0.1

Type RM Length L Ch R = 1 ,26167.7 ,595.2,603.6,612.1
XS GIS Cut Line= 3
     1859585.553      518645.939     1859832.404       518484.22
     1860288.045      518273.274
#Sta/Elev= 30
       0  781.22     9.8  777.28    19.7  771.84    49.2  755.14   108.2  720.35
   137.7  703.93   147.6  699.32   157.4  697.25   167.2   697.5   177.1  696.83
   186.9  696.58   196.7  698.07   216.4  702.88   236.1  705.35   255.8  706.68
   275.4   707.4   295.1  707.59   362.7   705.7   401.3  705.59     411  706.14
   459.3  712.38   468.9  714.92   536.5  739.67   555.8  747.11   594.4  762.99
   642.7  783.92   652.4  787.97     662  791.49   739.3  813.18   797.2  832.44
#Mann= 3 , 0 , 0
       0      .1       0   147.6    .045       0   196.7      .1       0
#XS Ineff= 2 , 0
                          290.08          714.67
Permanent Ineff=
       F       F
Bank Sta=147.6,196.7
XS Rating Curve= 0 ,0
Exp/Cntr=0.3,0.1

Type RM Length L Ch R = 1 ,25564.1 ,300,332.9,365.8
XS GIS Cut Line= 4
     1859800.666      518899.155     1859987.063       519023.64
     1860235.083         518968.     1860548.239      519215.176
#Sta/Elev= 30
       0  735.07    87.7  718.87   136.4  714.02   165.7  711.47   214.4  707.87
   233.9  705.65   282.8  701.65   321.9  696.13   341.5  694.28   370.8  693.53
   380.6  693.55   390.3   694.2   409.9  698.13   439.2  700.87   458.8  703.32
   478.3  704.52   507.5  708.21   517.2   710.5     527  713.75     634  752.41
   672.9  767.13   692.4  773.54   731.3  785.22   760.5  794.41     780  800.81
   789.7  804.36   799.4  808.66   809.2  813.58   867.6  844.23   877.3  846.91
#Mann= 3 , 0 , 0
       0      .1       0   341.5    .045       0   390.3      .1       0
Bank Sta=341.5,390.3
XS Rating Curve= 0 ,0
Exp/Cntr=0.3,0.1

Type RM Length L Ch R = 1 ,25231.2 ,416.4,420.8,425.2
XS GIS Cut Line= 3
     1859762.906      518892.645     1859924.364      519078.843
     1860029.833      519370.509
#Sta/Elev= 30
       0     737     9.5  735.95    85.3  726.44   113.8  723.82   123.2   723.7
   132.7  722.37   142.2  720.02   151.7   718.3   161.1  717.35   180.1  712.96
   189.6  711.33   199.1  710.23   208.5  708.92     218  707.02   227.5   705.7
   246.4   704.7   285.2  701.82   304.6  700.08   362.8  693.74   372.4  693.13
   382.1  693.04   391.8  693.09   401.5  693.61   411.2  695.88   430.6  703.61
   440.3  708.34     450  714.36   517.8  758.24   527.5  764.08   556.6  780.48
#Mann= 3 , 0 , 0
       0      .1       0   362.8    .045       0   401.5      .1       0
Bank Sta=362.8,401.5
XS Rating Curve= 0 ,0
Exp/Cntr=0.3,0.1

Type RM Length L Ch R = 1 ,24810.4 ,678.8,645.5,612.1
XS GIS Cut Line= 4
     1859361.772      518990.139     1859540.555      519148.078
     1859574.249      519372.521     1859663.948      519515.041
#Sta/Elev= 30
       0  838.24     9.5  833.99    66.8  803.91    76.3  799.43    85.9  795.89
     105  789.84   114.5  786.33     124  781.12   133.6  774.08   143.1  765.58
   152.7  757.44   162.2  750.93   181.3  740.48   200.4  730.79     248  708.34
   257.5  704.91   266.9  702.92   304.8  697.39   333.1  693.82   342.6  692.21
     352  690.87   361.5  690.24     371  690.35   380.4  691.17   389.9  693.22
   427.7  703.76   465.5  715.61   484.2   721.9   568.4  749.44   633.9  771.29
#Mann= 3 , 0 , 0
       0      .1       0     352    .045       0   380.4      .1       0
Bank Sta=352,380.4
XS Rating Curve= 0 ,0
Exp/Cntr=0.3,0.1

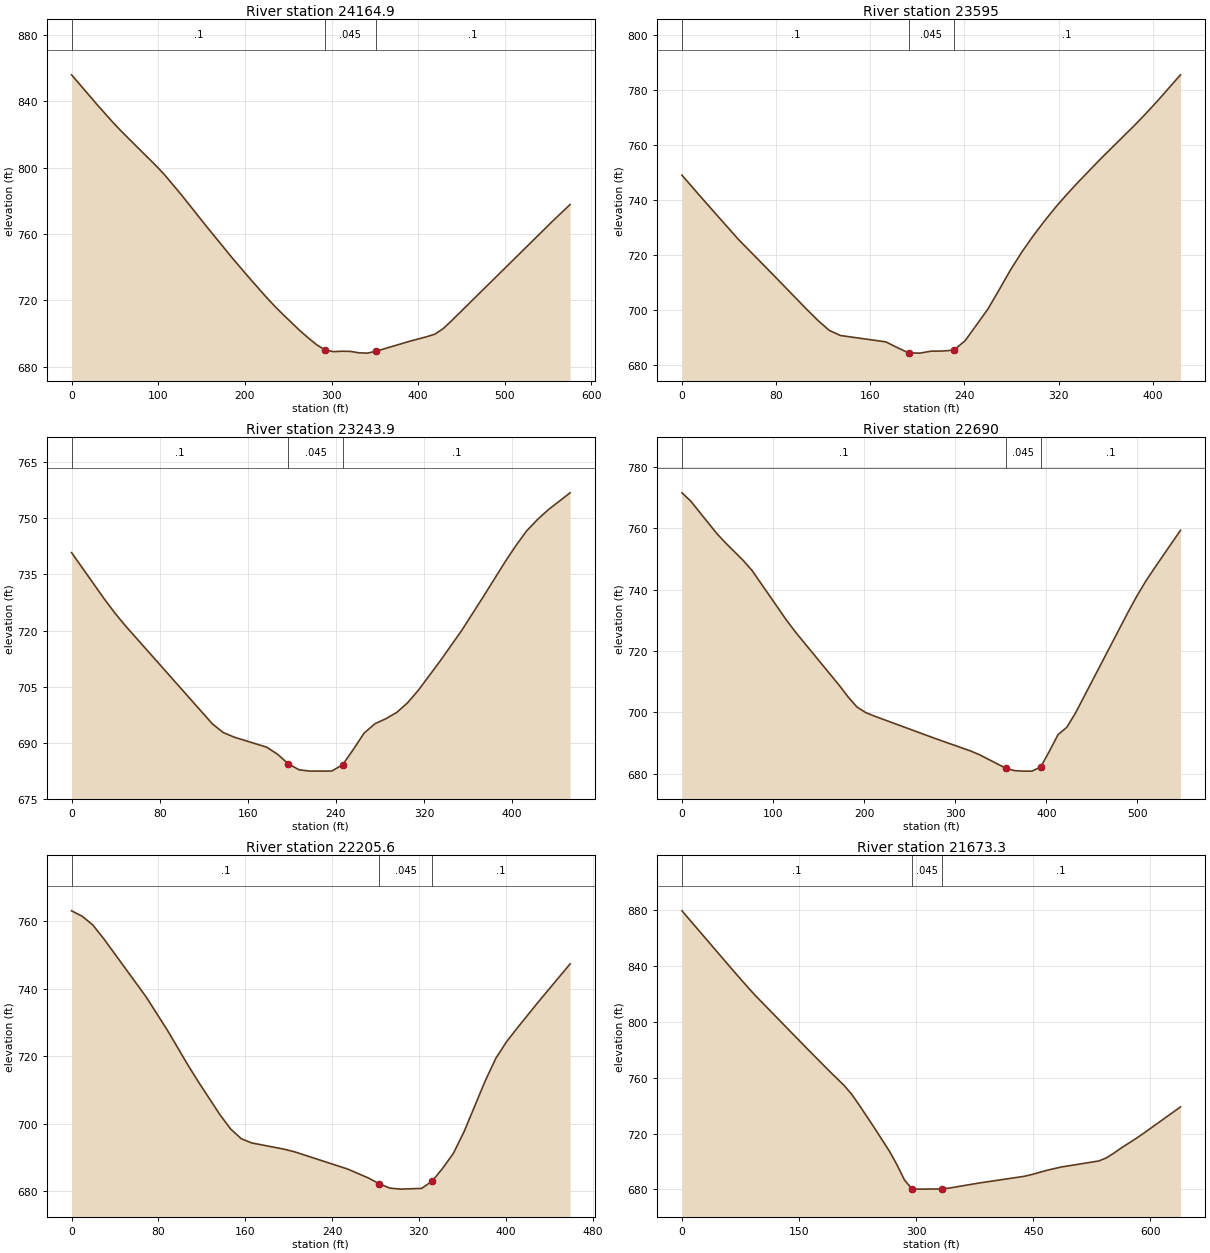
Type RM Length L Ch R = 1 ,24164.9 ,566,570,573.9
XS GIS Cut Line= 2
     1859034.446      519752.445      1859609.26      519725.978
#Sta/Elev= 30
       0  856.04    29.3  838.16    48.8  826.73    58.5  821.46    97.5   801.2
   107.3  795.78   126.8  783.62     156  764.44   185.3  745.69   204.8  733.74
   224.3  722.19   234.1  716.71   243.8  711.61   263.3  701.86   273.1  697.39
   282.8  693.27   292.6  690.03   302.3  689.08   312.1  689.32   321.8  689.24
   331.6  688.37   341.4  688.18   351.1  689.26   390.1  695.32   409.6  698.03
   419.4  699.64   429.1  703.04   438.9  707.86   555.9  768.14   575.4   777.8
#Mann= 3 , 0 , 0
       0      .1       0   292.6    .045       0   351.1      .1       0
Bank Sta=292.6,351.1
XS Rating Curve= 0 ,0
Exp/Cntr=0.3,0.1

Type RM Length L Ch R = 1 ,23595   ,348.2,351.1,354.1
XS GIS Cut Line= 2
      1859148.63      520278.184     1859568.574      520332.741
#Sta/Elev= 30
       0  749.01    19.2  739.55    48.1  725.56      77  712.96   105.9   700.2
   115.5  696.12   125.1   692.5   134.7  690.62   173.2  688.31   182.9  686.22
   192.5   684.3   202.1  684.21   211.7  684.93   221.4  684.97     231   685.3
   240.6  688.76   259.9  700.26   269.5  707.32   279.1  714.52   288.7  721.03
   298.4  726.93     308  732.37   317.6  737.45   327.2  742.15   336.8  746.59
   356.1  755.17     385   767.4   394.6   771.7   404.2  776.18   423.5  785.58
#Mann= 3 , 0 , 0
       0      .1       0   192.5    .045       0     231      .1       0
Bank Sta=192.5,231
XS Rating Curve= 0 ,0
Exp/Cntr=0.3,0.1

Type RM Length L Ch R = 1 ,23243.9 ,538.2,553.9,569.6
XS GIS Cut Line= 2
     1859058.479      520589.259     1859495.979      520705.145
#Sta/Elev= 30
       0  740.83    29.5  728.53    39.4  724.65    49.2  721.16   127.9  695.02
   137.7  692.72   147.6  691.49   177.1  688.81   186.9  686.94   196.8  684.34
   206.6  682.75   216.5   682.4   236.1  682.42     246  684.07   255.8   688.2
   265.6  692.58   275.5  695.09   285.3  696.41   295.2  698.09     305  700.66
   314.8  704.02   334.5   711.8   354.2  720.03   373.9   729.1   393.6  738.38
   403.4  742.71   413.2  746.67   423.1  749.72   432.9  752.34   452.6  756.83
#Mann= 3 , 0 , 0
       0      .1       0   196.8    .045       0     246      .1       0
Bank Sta=196.8,246
XS Rating Curve= 0 ,0
Exp/Cntr=0.3,0.1

Type RM Length L Ch R = 1 ,22690   ,480.5,484.4,488.3
XS GIS Cut Line= 3
     1858873.314      520799.963     1858932.258       520982.69
     1859137.384      521272.695
#Sta/Elev= 30
       0  771.47     9.6  768.77    38.4  758.16      48  755.13    67.2  749.47
    76.8  746.24   115.2  729.83   124.8  726.08   172.8  708.76   182.4  705.03
     192  701.78   201.6  699.97   211.2  698.81   278.4  691.47   316.8  687.46
   326.4  686.26   355.2  681.89   364.8  681.07   374.4   680.9     384   680.9
   393.6   682.2   403.2  687.32   412.8  692.78   422.4  695.16     432  699.84
   489.6  732.61   499.2  737.82   508.8  742.58   518.4  746.87   547.2  759.28
#Mann= 3 , 0 , 0
       0      .1       0   355.2    .045       0   393.6      .1       0
Bank Sta=355.2,393.6
XS Rating Curve= 0 ,0
Exp/Cntr=0.3,0.1

Type RM Length L Ch R = 1 ,22205.6 ,550.3,532.3,513.8
XS GIS Cut Line= 2
     1858514.933      521131.229     1858711.807      521546.196
#Sta/Elev= 30
       0     763     9.8  761.39    19.5  758.84    29.3  754.89    68.4  737.65
      88  727.81   107.5  717.19   117.3  712.16   136.8  702.61   146.6  698.41
   156.4  695.54   166.1  694.29   195.4  692.48   205.2   691.7   254.1   686.6
   273.6  683.91   283.4  682.22   293.2  680.94   302.9  680.63   322.5  680.84
   332.3  683.02     342  686.84   351.8  691.24   361.6  697.63   381.1  712.67
   390.9  719.37   400.7  724.23   410.4  728.23     430  736.02   459.3  747.29
#Mann= 3 , 0 , 0
       0      .1       0   283.4    .045       0   332.3      .1       0
Bank Sta=283.4,332.3
XS Rating Curve= 0 ,0
Exp/Cntr=0.3,0.1

Type RM Length L Ch R = 1 ,21673.3 ,472.7,468.1,462.9
XS GIS Cut Line= 4
     1857911.281      521643.162     1858109.164      521661.581
     1858391.205      521755.089     1858529.998      521788.263
#Sta/Elev= 30
       0  879.74    66.2   836.5    85.2  824.39    94.6  818.64   160.9  780.57
   189.3  764.53   208.3  754.15   217.9  747.78   227.5  740.06   237.1     732
   246.7  723.88   265.8  707.31   275.4  697.58     285  686.74   294.6  680.22
   304.2  680.13   332.9  680.27   342.5  680.89   380.9  684.54   438.4  689.32
     448  690.57   467.1  693.57   486.3  696.05   533.9  700.31   543.4  702.46
     553  705.84   562.5  709.56   581.5  716.39     591  720.03   638.6   739.1
#Mann= 3 , 0 , 0
       0      .1       0   294.6    .045       0   332.9      .1       0
Bank Sta=294.6,332.9
XS Rating Curve= 0 ,0
Exp/Cntr=0.3,0.1

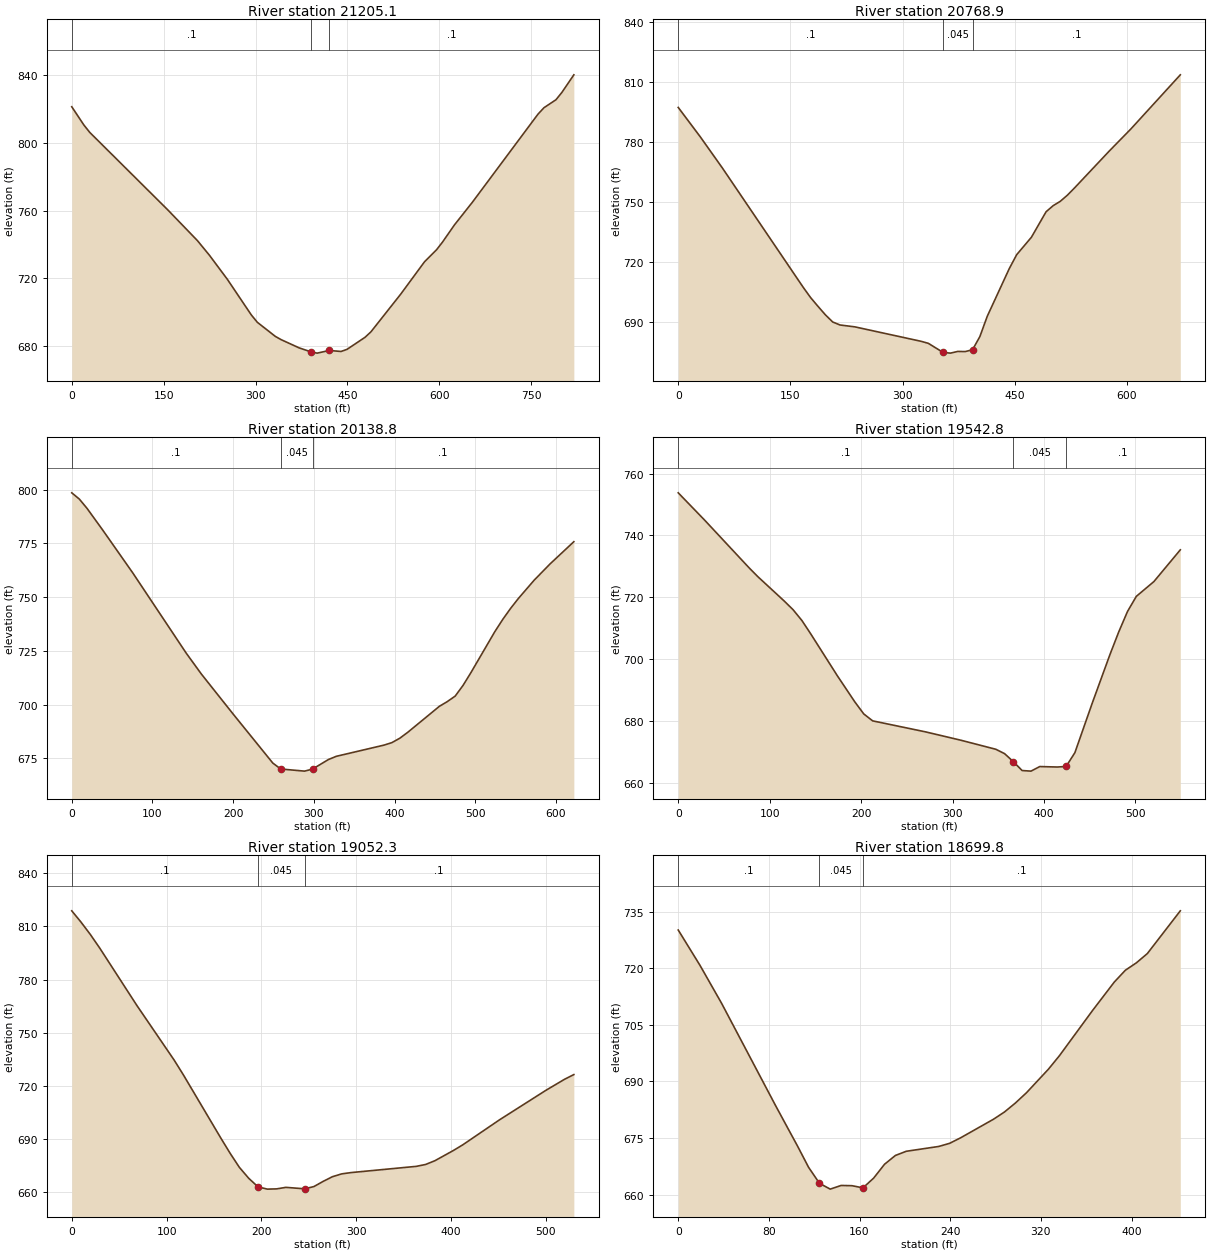
Type RM Length L Ch R = 1 ,21205.1 ,423.6,436.2,449.3
XS GIS Cut Line= 3
     1857820.111      522116.029     1858227.835      522163.299
     1858635.396      522201.328
#Sta/Elev= 30
       0  821.25    19.6  810.57    29.3  806.14   156.4  760.51   205.2  742.22
   224.8  733.58   254.1  719.36   293.2  698.34     303  694.01   332.3  685.71
     342  683.74   371.4  678.89   390.9  676.52   400.7  675.81   420.5677.3753
   439.7  676.79   449.4  678.03   478.7  685.11   488.4  688.34   537.2  710.67
   576.1  729.79   595.6  736.82   605.4  741.39   624.9  751.52   654.1  764.87
   761.3   816.9   771.1   820.7   790.6  825.39   800.3  829.72   819.8   840.1
#Mann= 3 , 0 , 0
       0      .1       0   390.9    .045       0   420.5      .1       0
Bank Sta=390.9,420.5
XS Rating Curve= 0 ,0
Exp/Cntr=0.3,0.1

Type RM Length L Ch R = 1 ,20768.9 ,640.8,630.1,619.3
XS GIS Cut Line= 3
     1857745.294      522312.552      1858130.02       522619.13
     1858295.269       522689.02
#Sta/Elev= 30
       0  797.33    29.5  782.59      59     767   167.3  707.08   177.1  701.99
   186.9  697.64   196.8  693.39   206.6   689.8   216.4   688.3   236.1  687.37
   324.7  680.13   334.5   679.1   354.2  674.54     364   674.2   373.9  675.05
   383.7  674.97   393.6  675.91   403.4  682.52   413.2  692.63   442.7  716.57
   452.6  723.54   472.3  732.28   491.9  745.04   501.4  748.11   510.8  750.25
   520.3  753.32   529.7  756.89   576.9  775.67   605.3  786.54   671.4  813.67
#Mann= 3 , 0 , 0
       0      .1       0   354.2    .045       0   393.6      .1       0
Bank Sta=354.2,393.6
XS Rating Curve= 0 ,0
Exp/Cntr=0.3,0.1

Type RM Length L Ch R = 1 ,20138.8 ,576.8,596,615.2
XS GIS Cut Line= 4
     1857489.569      522935.004     1857618.153      523031.205
     1857859.365      523078.945     1858055.206      523169.146
#Sta/Elev= 30
       0  798.52     9.4   795.6    18.9   791.3    37.8  781.49    75.6  761.27
   141.7  724.01   160.6  714.22   199.9  695.64   249.1  672.82   258.9  670.06
   288.4  669.07   298.3  670.01     318  674.46   327.8  675.96   386.8  681.16
   396.6  682.32   406.5  684.39   416.3  687.12   455.5  699.22   465.3  701.41
   475.1  703.98   484.9  708.99   494.7  714.97   524.1  733.88   533.9  739.58
   543.7  744.74   553.5  749.43   573.1  757.95   592.7  765.47   622.1  775.79
#Mann= 3 , 0 , 0
       0      .1       0   258.9    .045       0   298.3      .1       0
Bank Sta=258.9,298.3
XS Rating Curve= 0 ,0
Exp/Cntr=0.3,0.1

Type RM Length L Ch R = 1 ,19542.8 ,526,490.5,454.3
XS GIS Cut Line= 3
     1857141.902      523341.055     1857389.292      523423.797
     1857534.064      523672.995
#Sta/Elev= 30
       0  753.81      29  744.93    77.3  729.59      87  726.68   115.9  718.78
   125.6  715.96   135.3  712.45   144.9  708.15   173.9  694.63   193.2  686.09
   202.9  682.22   212.6  679.98   270.5  676.41   308.9  673.72   347.3  670.78
   356.9  669.36   366.5  666.76   376.1  663.89   385.8   663.7   395.4  665.18
   414.6  665.03   424.2  665.21   433.8  669.67     453  685.89   472.2  701.48
   481.8   708.8   491.4  715.42     501  720.29   520.2  725.07   549.1  735.35
#Mann= 3 , 0 , 0
       0      .1       0   366.5    .045       0   424.2      .1       0
Bank Sta=366.5,424.2
XS Rating Curve= 0 ,0
Exp/Cntr=0.3,0.1

Type RM Length L Ch R = 1 ,19052.3 ,361.3,352.5,343.7
XS GIS Cut Line= 3
     1857024.483       524008.84     1857362.136      523808.254
     1857490.846      523762.286
#Sta/Elev= 30
       0  818.77     9.8  812.37    19.6  805.41    29.5  797.74    68.7  765.33
     108  734.52   117.8  726.11   157.1  690.61   166.9  682.03   176.7  674.04
   186.6  667.85   196.4  663.02   206.2  661.74     216  661.88   225.8  662.74
   245.5  661.91   255.3  663.18   265.1  666.12   274.9  668.76   284.7  670.35
   294.6  671.08   363.3  674.59   373.1  675.65   382.9  677.77   402.5  683.57
   412.3  686.74   451.3  700.94   500.1  717.54   519.6  723.72   529.4  726.37
#Mann= 3 , 0 , 0
       0      .1       0   196.4    .045       0   245.5      .1       0
Bank Sta=196.4,245.5
XS Rating Curve= 0 ,0
Exp/Cntr=0.3,0.1

Type RM Length L Ch R = 1 ,18699.8 ,376.8,393.3,410.2
XS GIS Cut Line= 3
     1857390.369       524245.65     1857546.304      524039.256
     1857676.702       523908.97
#Sta/Elev= 30
       0  730.09    19.2  720.73    38.3  710.65    86.2  683.39   105.4  672.76
     115  667.22   124.6  662.98   134.1  661.43   143.7   662.4   153.3  662.34
     163661.7673   172.4  664.34     182  668.01   191.6  670.35   201.2  671.46
   229.9  672.74   239.5  673.57   249.1  675.02   278.1  679.94   287.8  681.86
   297.5  684.25   307.2  686.95   326.6   693.2   336.3  696.77   365.4   708.7
   384.8  716.32   394.5  719.43   404.2  721.39   413.9  723.85     443  735.18
#Mann= 3 , 0 , 0
       0      .1       0   124.6    .045       0     163      .1       0
Bank Sta=124.6,163
XS Rating Curve= 0 ,0
Exp/Cntr=0.3,0.1

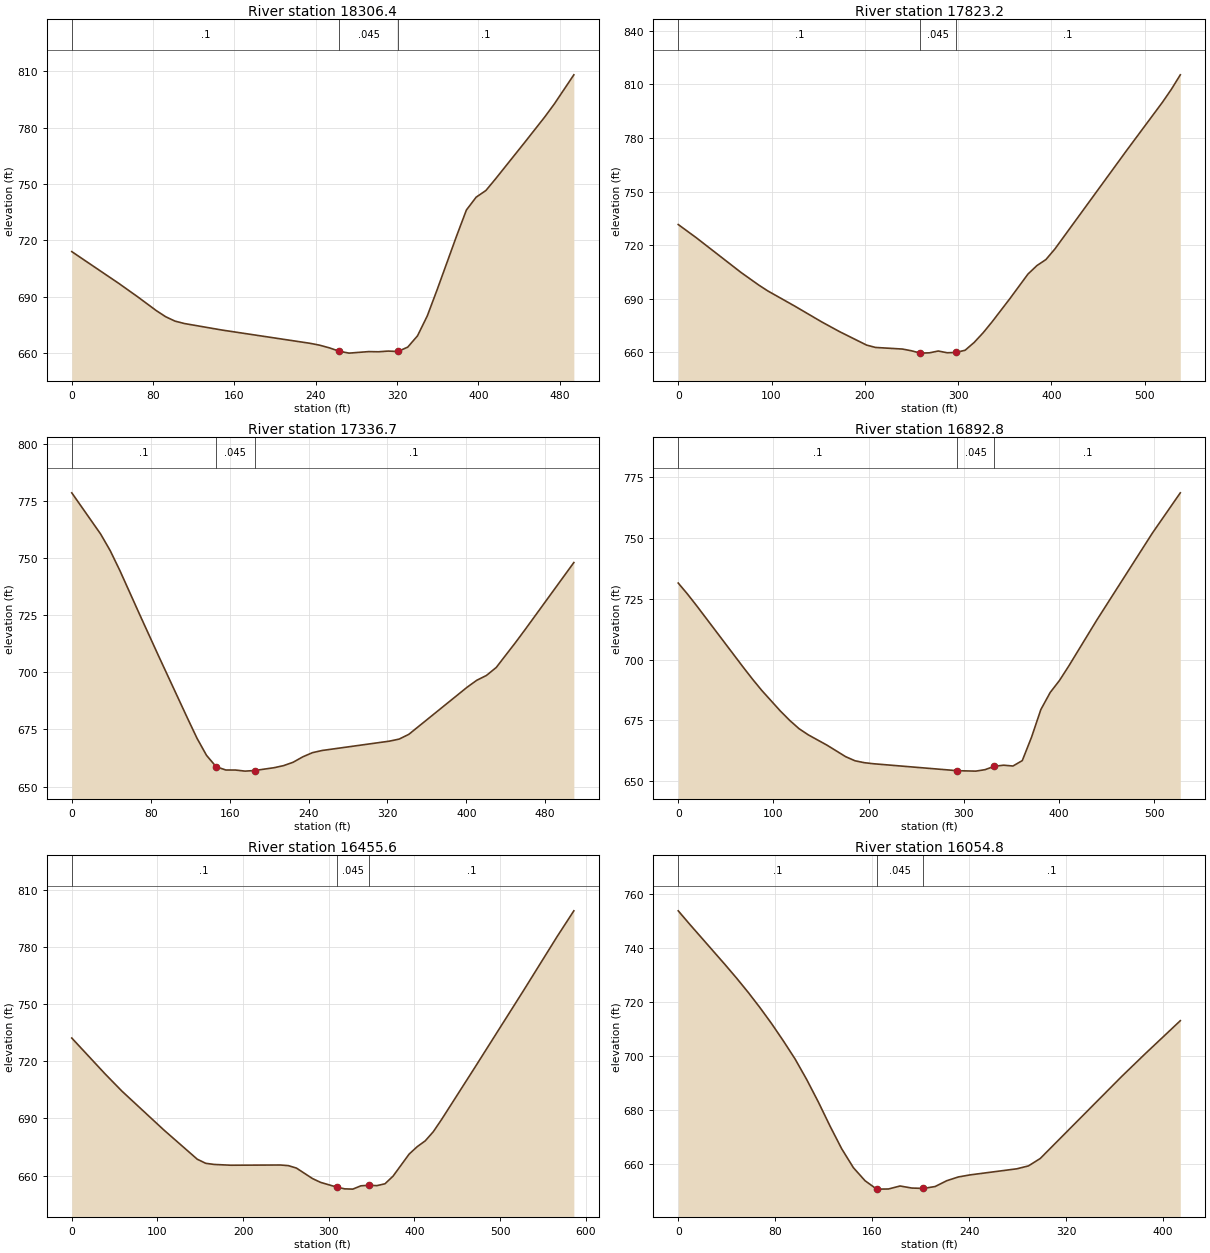
Type RM Length L Ch R = 1 ,18306.4 ,470,483.3,496.1
XS GIS Cut Line= 3
     1857480.294      524407.191     1857627.389      524392.781
     1857967.809      524330.341
#Sta/Elev= 30
       0  714.01    46.2  697.11    64.7     690    83.1  682.61    92.4  679.32
   101.6  676.99   110.8  675.71   147.8  672.24   234.3  665.19   243.9  664.17
   253.6  662.73   263.2  660.94   272.8  659.95     292  660.76   301.6  660.67
   311.2  661.04   320.8  660.82   330.5  663.15   340.1  669.15   349.7  679.74
   359.3  693.55   378.5  722.24   388.2  736.16   397.8     743   407.4  746.56
     417  752.83   445.8  772.34   465.1   785.6   474.7  792.65   493.9  808.16
#Mann= 3 , 0 , 0
       0      .1       0   263.2    .045       0   320.8      .1       0
Bank Sta=263.2,320.8
XS Rating Curve= 0 ,0
Exp/Cntr=0.3,0.1

Type RM Length L Ch R = 1 ,17823.2 ,503.7,486.5,469
XS GIS Cut Line= 3
     1857342.191      524705.444      1857696.67      524854.561
     1857845.133      524894.456
#Sta/Elev= 30
       0  731.55    19.2  724.22    67.3  704.73    86.5   697.6    96.1  694.36
     125  685.86   153.8  677.05   173.1  671.55   201.9  664.07   211.5  662.74
   240.4  661.84     250  660.88   259.6  659.56   269.2  659.72   278.8  660.74
   288.4  659.76     298  659.96   307.6  661.18   317.3  665.55   326.9  670.96
   336.5  677.08   355.7  690.14     375  703.84   384.6  708.58   394.2  711.93
   403.8  717.84   480.6   772.9   519.1  799.96   528.7  807.24   538.3  815.35
#Mann= 3 , 0 , 0
       0      .1       0   259.6    .045       0     298      .1       0
Bank Sta=259.6,298
XS Rating Curve= 0 ,0
Exp/Cntr=0.3,0.1

Type RM Length L Ch R = 1 ,17336.7 ,437.4,443.8,449.8
XS GIS Cut Line= 3
     1857313.417      525302.224     1857612.897      525183.735
     1857773.053       525087.38
#Sta/Elev= 30
       0  778.63    29.3  760.56      39  753.29    48.8  744.56    68.3  725.85
    87.8  707.39   117.1  680.14   126.9  671.21   136.6  663.67   146.4  658.68
   156.2  657.25   165.9  657.24   175.7  656.76   185.4  657.03     205  658.25
   214.7  659.16   224.5  660.66   234.2  663.02     244  664.84   253.8   665.8
   322.1  669.89   331.9  670.79   341.7  672.87   400.8   693.5   410.6  696.55
   420.4  698.66   430.3  702.14     450  713.16   459.8  718.86     509   748.1
#Mann= 3 , 0 , 0
       0      .1       0   146.4    .045       0   185.4      .1       0
Bank Sta=146.4,185.4
XS Rating Curve= 0 ,0
Exp/Cntr=0.3,0.1

Type RM Length L Ch R = 1 ,16892.8 ,411.5,437.2,462.9
XS GIS Cut Line= 2
     1857432.098       525561.13     1857956.445      525504.032
#Sta/Elev= 30
       0  731.45     9.8   726.9    19.5  722.06    68.4  696.81    78.1  691.94
    87.9  687.28   107.4  678.84   117.2     675     127   671.6   136.8  669.06
   156.3  664.86   175.8  660.15   185.6  658.46   195.4  657.67   205.1  657.23
     293  654.38   312.6   654.2   322.3   654.8   332.1   656.2   341.9  656.63
   351.6   656.3   361.4  658.52   371.2  668.22   380.9  679.48   390.7  686.49
   400.5  691.45   410.2  697.35   439.5  716.13   498.1  751.99   527.4  768.51
#Mann= 3 , 0 , 0
       0      .1       0     293    .045       0   332.1      .1       0
Bank Sta=293,332.1
XS Rating Curve= 0 ,0
Exp/Cntr=0.3,0.1

Type RM Length L Ch R = 1 ,16455.6 ,402.6,400.9,399.1
XS GIS Cut Line= 4
     1857369.407      525652.485     1857530.865      525808.735
     1857637.636      525985.818     1857749.615      526092.589
#Sta/Elev= 30
       0  732.22    39.1   713.3    58.6  704.33   107.5  683.96   146.5  668.62
   156.3  666.48   166.1  665.87   185.6  665.46   243.5  665.57   252.9  665.24
   262.3  663.96   281.1  658.45   290.5  656.46   309.3  653.98   318.7  653.05
   328.1  652.91   337.5  654.64   346.9  654.96   356.3  654.74   365.7  655.72
   375.1  659.72   393.9   671.3   403.3  675.18   412.7  678.25   422.1  683.04
   431.5  689.27   470.2  716.47   528.2  757.68   566.8  785.56   586.2  798.99
#Mann= 3 , 0 , 0
       0      .1       0   309.3    .045       0   346.9      .1       0
Bank Sta=309.3,346.9
XS Rating Curve= 0 ,0
Exp/Cntr=0.3,0.1

Type RM Length L Ch R = 1 ,16054.8 ,483.6,474.5,465.3
XS GIS Cut Line= 2
     1857128.522      525940.245     1857369.407      526277.485
#Sta/Elev= 30
       0  753.89     9.6  748.85    38.6     734    48.2  728.94    57.8  723.66
    67.5  718.01    77.1  712.09    86.7  705.76    96.4  699.05     106  691.43
   115.7  683.03   125.3  674.15   134.9  665.77   144.6  658.74   154.2  653.92
   163.8  650.81   173.5  650.86   183.1  651.97   192.8  651.21   202.4  651.07
     212  651.77   221.7  653.94   231.3  655.33     241  656.09   279.5  658.34
   289.1  659.42   298.8  662.16   366.2  692.62   385.5  700.98   414.4  713.19
#Mann= 3 , 0 , 0
       0      .1       0   163.8    .045       0   202.4      .1       0
Bank Sta=163.8,202.4
XS Rating Curve= 0 ,0
Exp/Cntr=0.3,0.1

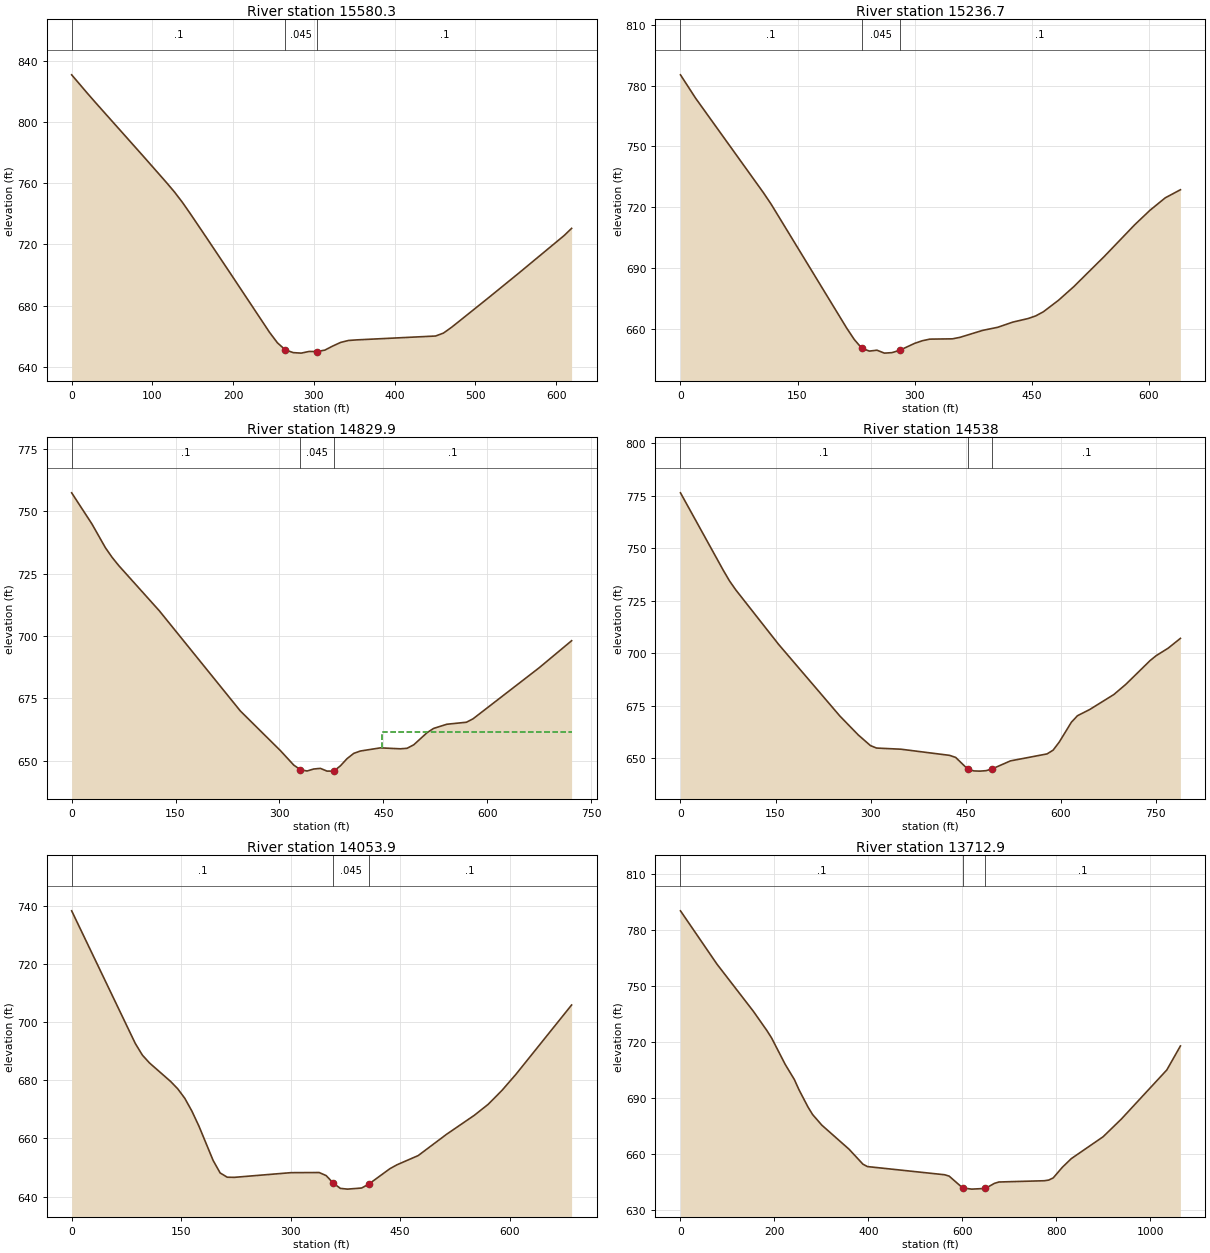
Type RM Length L Ch R = 1 ,15580.3 ,347.3,343.6,339.9
XS GIS Cut Line= 3
     1856679.739      526298.009     1857082.354      526541.108
     1857219.232      526599.408
#Sta/Elev= 30
       0  830.93    19.6  818.79    29.4  812.87    88.2  778.02   117.6  760.38
   127.4  754.27   137.2  747.51     147  740.08   166.6  724.75     196  701.54
     245  662.58   254.8   655.7   264.6  651.07   274.4  649.28   284.2  648.95
     294  650.04   303.8  649.97   313.5  650.92   323.3  653.58   333.1  655.96
   342.9  657.23   352.7   657.6   450.7  660.14   460.5  662.08   470.3  665.78
   479.6  669.68   516.8  685.41     554  701.39   609.8  725.81   619.1  730.53
#Mann= 3 , 0 , 0
       0      .1       0   264.6    .045       0   303.8      .1       0
Bank Sta=264.6,303.8
XS Rating Curve= 0 ,0
Exp/Cntr=0.3,0.1

Type RM Length L Ch R = 1 ,15236.7 ,408.1,406.8,405.3
XS GIS Cut Line= 3
     1856528.261      526655.089     1856924.095      526812.641
     1857135.032      526853.005
#Sta/Elev= 30
       0  785.27    19.4  773.75   106.5  727.12   116.2  721.58     213  660.58
   222.7  654.97   232.4  650.62   242.1  649.22   251.8  649.66   261.4  648.22
   271.1  648.46   280.8  649.59   300.2  653.04   309.8   654.3   319.5  655.11
   348.6  655.26   358.3     656   387.3  659.42   406.7  660.95     426   663.5
   445.6  665.26   455.3  666.55   465.1  668.57   484.6  674.27   504.1  680.95
   543.2  695.82   582.2  711.43   601.8  718.57   621.3  724.68   640.8  728.68
#Mann= 3 , 0 , 0
       0      .1       0   232.4    .045       0   280.8      .1       0
Bank Sta=232.4,280.8
XS Rating Curve= 0 ,0
Exp/Cntr=0.3,0.1

Type RM Length L Ch R = 1 ,14829.9 ,295.4,291.8,288.1
XS GIS Cut Line= 4
     1856411.499      526885.818       1856527.9      527099.833
     1856784.183      527183.861     1856957.414      527300.292
#Sta/Elev= 30
       0  757.31    29.2  744.89    48.7  735.36    58.5  731.45    68.2  728.13
   126.7  710.07   243.6  670.01   301.4  654.16   320.7  648.36   330.3  646.49
     340  645.98   349.6  646.78   359.2  647.03   368.8  645.94   378.5  645.93
   388.1  648.04   397.7  650.92   407.4  653.04     417  653.98   445.9  655.24
   474.8  654.86   484.4  655.07   494.1  656.48   513.3  661.33   522.8  663.03
   541.8  664.69   570.2   665.5   579.7  666.87   674.6  687.17     722  698.12
#Mann= 3 , 0 , 0
       0      .1       0   330.3    .045       0   378.5      .1       0
#XS Ineff= 2 , 0
                          447.59           661.6
Permanent Ineff=
       F       F
Bank Sta=330.3,378.5
XS Rating Curve= 0 ,0
Exp/Cntr=0.3,0.1

Type RM Length L Ch R = 1 ,14538   ,488.2,484.2,480.1
XS GIS Cut Line= 4
     1856100.917      527371.838     1856390.631      527390.284
     1856732.428      527443.452     1856869.147      527511.812
#Sta/Elev= 30
       0  776.44    67.7  739.43    77.4  734.43    87.1  730.24   154.8  704.21
   251.6     670   280.6  660.99   299.9   655.9   309.5  654.73     348  654.18
   424.8  651.25   434.4  650.26   453.6  644.64   463.2  643.83   472.9  643.73
   482.5  643.96   492.1  644.82   520.9  648.62   578.6  651.94   588.2  653.74
   597.8  657.57     617  667.05   626.6  670.15   645.8  673.09     684  680.25
   703.1  685.16   741.3  696.46   750.8  698.78     770  702.41   789.1  707.04
#Mann= 3 , 0 , 0
       0      .1       0   453.6    .045       0   492.1      .1       0
Bank Sta=453.6,492.1
XS Rating Curve= 0 ,0
Exp/Cntr=0.3,0.1

Type RM Length L Ch R = 1 ,14053.9 ,349.7,340.9,332.1
XS GIS Cut Line= 3
     1856130.214      527898.096     1856653.218      527887.246
     1856812.723      527860.119
#Sta/Elev= 30
       0  738.26    87.2  692.64    96.9  688.64   106.6  685.96   135.6  679.58
   145.3  677.06     155  673.79   164.7   669.4   174.4  664.21   193.8  652.43
   203.4  648.13   213.1  646.66   222.8  646.61   300.3  648.22   339.1  648.27
   348.7  647.21   358.4  644.63   368.1  642.82   377.8  642.56   397.2  642.94
   406.9  644.26   435.9  649.57   445.6  650.92   474.7  654.09   513.4  661.38
   551.7  667.96   570.7  671.74   589.7  676.56   608.8  682.09   684.9  705.88
#Mann= 3 , 0 , 0
       0      .1       0   358.4    .045       0   406.9      .1       0
Bank Sta=358.4,406.9
XS Rating Curve= 0 ,0
Exp/Cntr=0.3,0.1

Type RM Length L Ch R = 1 ,13712.9 ,459.7,434.9,410.1
XS GIS Cut Line= 5
     1856009.772      528538.287     1856188.287      528374.257
     1856386.291      528293.062     1856747.619      528133.556
     1856908.209      527993.582
#Sta/Elev= 30
       0   790.4    77.6  761.87   155.2  736.57   184.2  726.17     194  722.28
     223  708.11   242.4  700.04   252.2   694.6   271.6  685.23   281.3  681.26
   300.8  675.61   359.2  662.61   388.4  654.68   398.1  653.38   562.4     649
     572  648.27   600.9  641.93   620.2   641.3   649.1  641.67   668.4  644.39
     678  645.12   774.3  645.79     784  646.15   793.6  647.32   812.9  652.97
   832.1  657.64   899.8  669.36   938.6  678.83  1035.4  705.14  1064.4     718
#Mann= 3 , 0 , 0
       0      .1       0   600.9    .045       0   649.1      .1       0
Bank Sta=600.9,649.1
XS Rating Curve= 0 ,0
Exp/Cntr=0.3,0.1