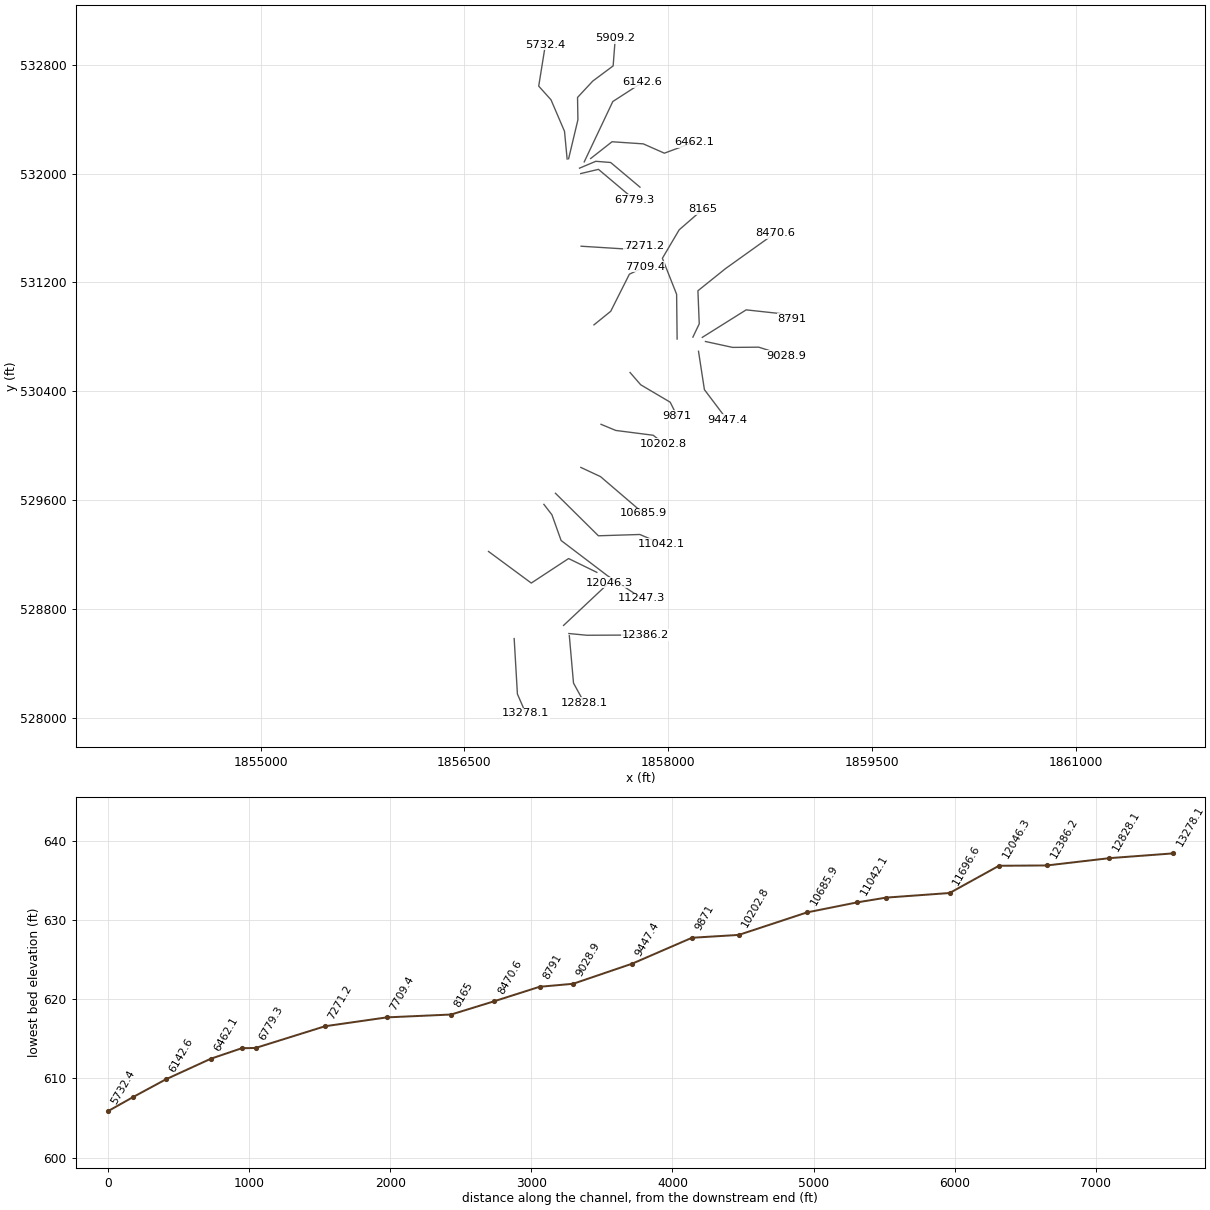
HEC-RAS study FALLINGRCR.prj: FALLINGRCR

--- FALLINGRCR.g01 (geometry) --- (continued)

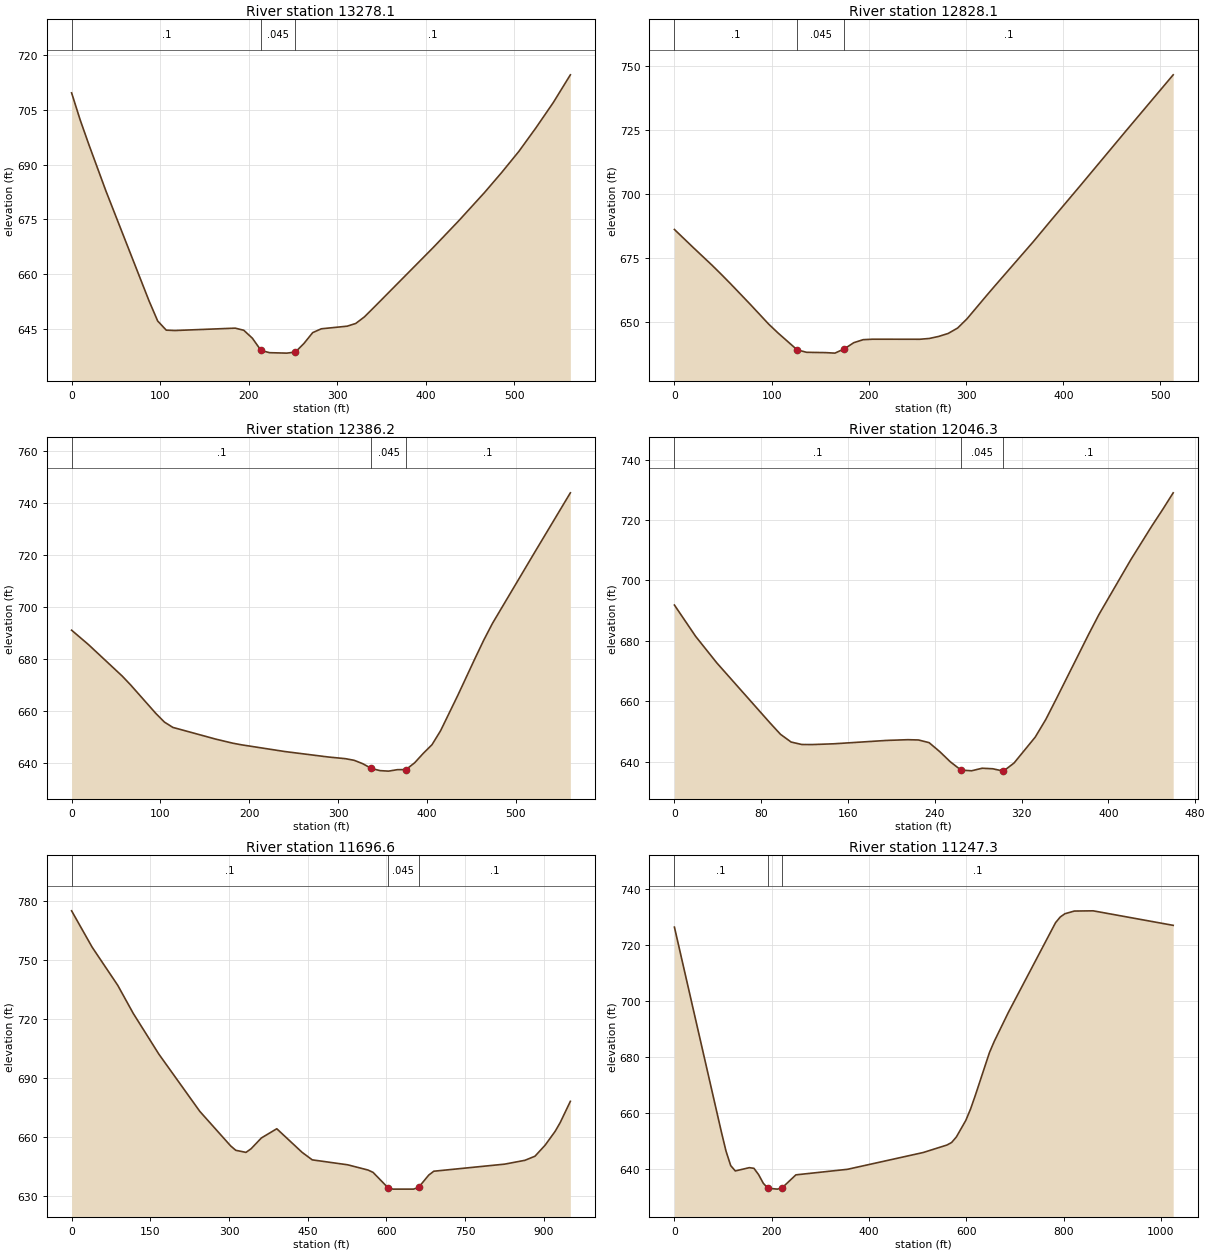
Type RM Length L Ch R = 1 ,13278.1 ,449.3,450,450.7
XS GIS Cut Line= 3
     1856865.891       528581.69     1856889.763      528173.704
     1856951.612       528031.56
#Sta/Elev= 30
       0  709.68     9.7  702.26    19.5  695.52    38.9  682.74    87.6  652.66
    97.3   647.2     107  644.69   116.8  644.59   184.9  645.24   194.6  644.66
   204.3  642.49   214.1  639.13   223.8  638.52   243.3   638.4     253   638.7
   262.7  641.08   272.5  644.02   282.2  645.06   311.4  645.78   321.1  646.52
   330.8   648.3   340.6  650.65   408.7  667.32   437.8  674.71   466.8  682.42
   486.2  687.91   505.6  693.68     525  700.18   544.3  706.99   563.7  714.62
#Mann= 3 , 0 , 0
       0      .1       0   214.1    .045       0     253      .1       0
Bank Sta=214.1,253
XS Rating Curve= 0 ,0
Exp/Cntr=0.3,0.1

Type RM Length L Ch R = 1 ,12828.1 ,408.1,441.9,475.6
XS GIS Cut Line= 3
     1857271.707      528602.306     1857302.494      528254.035
     1857381.299       528110.77
#Sta/Elev= 29
       0  686.04    19.4  678.98    38.8  672.06    48.6  668.39    58.3  664.65
    77.7  656.96    97.1  649.07   106.8  645.59   126.3  639.07     136  638.12
   155.4     638   165.1   637.8   174.8  639.48   184.5  641.87   194.2  643.05
     204  643.23   252.5  643.21   262.2  643.52   271.9  644.32   281.6  645.47
   291.4   647.6   301.1  651.23   320.5  659.98   330.2  664.27   368.9  681.15
   388.1   689.9     417   702.9     465  724.71   513.1  746.37
#Mann= 3 , 0 , 0
       0      .1       0   126.3    .045       0   174.8      .1       0
Bank Sta=126.3,174.8
XS Rating Curve= 0 ,0
Exp/Cntr=0.3,0.1

Type RM Length L Ch R = 1 ,12386.2 ,322.9,339.9,356.8
XS GIS Cut Line= 3
     1857268.452      528618.582     1857400.867       528605.91
     1857829.433      528607.732
#Sta/Elev= 30
       0  691.09      19  685.55      57  673.44    66.5  670.02      95  659.02
   104.5  655.75     114   653.7   162.2   649.2   181.7  647.61   191.5  646.99
   240.2  644.41   288.9  642.32   308.3  641.67   318.1  641.05   327.8  639.74
   337.6  637.91   347.3  637.07     357  636.88   366.8  637.44   376.5  637.47
   386.3   640.1     396  643.72   405.8  647.04   415.5  652.44     435  666.13
   454.4  680.35   464.2  687.35   473.9  693.72   522.6  721.72   561.6  743.93
#Mann= 3 , 0 , 0
       0      .1       0   337.6    .045       0   376.5      .1       0
Bank Sta=337.6,376.5
XS Rating Curve= 0 ,0
Exp/Cntr=0.3,0.1

Type RM Length L Ch R = 1 ,12046.3 ,353.7,349.7,345.7
XS GIS Cut Line= 2
      1857229.39      528678.261     1857564.676      528992.931
#Sta/Elev= 30
       0  691.85    19.6  681.46    39.1  672.68      88  652.86    97.8  649.03
   107.6  646.47   117.4  645.66   127.2  645.64   146.8  645.89   195.7  647.01
   215.2  647.25     225  647.16   234.8  646.27   244.6   643.3   254.4  639.91
   264.2  637.19   273.9  636.95   283.7   637.8   293.5  637.62   303.3  636.84
   313.1  639.53   332.6   648.1   342.4  653.98   352.2  660.88   381.6  681.97
   391.3  688.68   420.7  706.85   440.2  718.08     450  723.44   459.8  729.02
#Mann= 3 , 0 , 0
       0      .1       0   264.2    .045       0   303.3      .1       0
Bank Sta=264.2,303.3
XS Rating Curve= 0 ,0
Exp/Cntr=0.3,0.1

Type RM Length L Ch R = 1 ,11696.6 ,490.4,449.3,408.1
XS GIS Cut Line= 4
     1856677.089      529221.881     1856991.759      528989.676
     1857266.282      529169.798     1857474.181      529068.452
#Sta/Elev= 30
       0  774.86    39.1  756.41      88  736.98   117.3  722.82   166.2  702.07
   244.4  672.92   303.1  655.39   312.9  653.14   332.4  652.07   342.2  653.94
   361.7   659.4   391.1  664.09   439.4  652.09   458.7  648.28   526.3  645.76
   564.9  643.11   574.6  641.92   603.5     634   613.2   633.4   651.8   633.4
   661.5  634.32   680.8  640.55   690.4   642.5   825.4   646.1     864  648.04
   883.2  650.12   902.5  655.71   921.8  662.82   931.4  667.27   950.7  678.03
#Mann= 3 , 0 , 0
       0      .1       0   603.5    .045       0   661.5      .1       0
Bank Sta=603.5,661.5
XS Rating Curve= 0 ,0
Exp/Cntr=0.3,0.1

Type RM Length L Ch R = 1 ,11247.3 ,195.1,205.2,215.3
XS GIS Cut Line= 5
     1857084.598      529568.105     1857143.626      529491.716
     1857211.334       529302.48     1857552.306      529043.713
     1857802.914      528878.869
#Sta/Elev= 30
       0   726.5    96.5   653.3   106.1   646.4   115.7  641.24   125.2  639.32
     154   640.5   163.5  640.26   173.1     638   182.7  634.92   192.2  633.15
   211.4  632.82     221  633.21   249.7  637.92   355.9  639.91   511.5  645.91
   560.2  648.58   569.9  649.49   579.6  651.45   599.1  657.39   608.8  661.43
   618.6  666.31   647.7  681.64   657.5  685.62   686.6  696.01   783.6  728.08
   793.3  730.13     803   731.3   822.3  732.25     861  732.33  1025.5  727.14
#Mann= 3 , 0 , 0
       0      .1       0   192.2    .045       0     221      .1       0
Bank Sta=192.2,221
XS Rating Curve= 0 ,0
Exp/Cntr=0.3,0.1

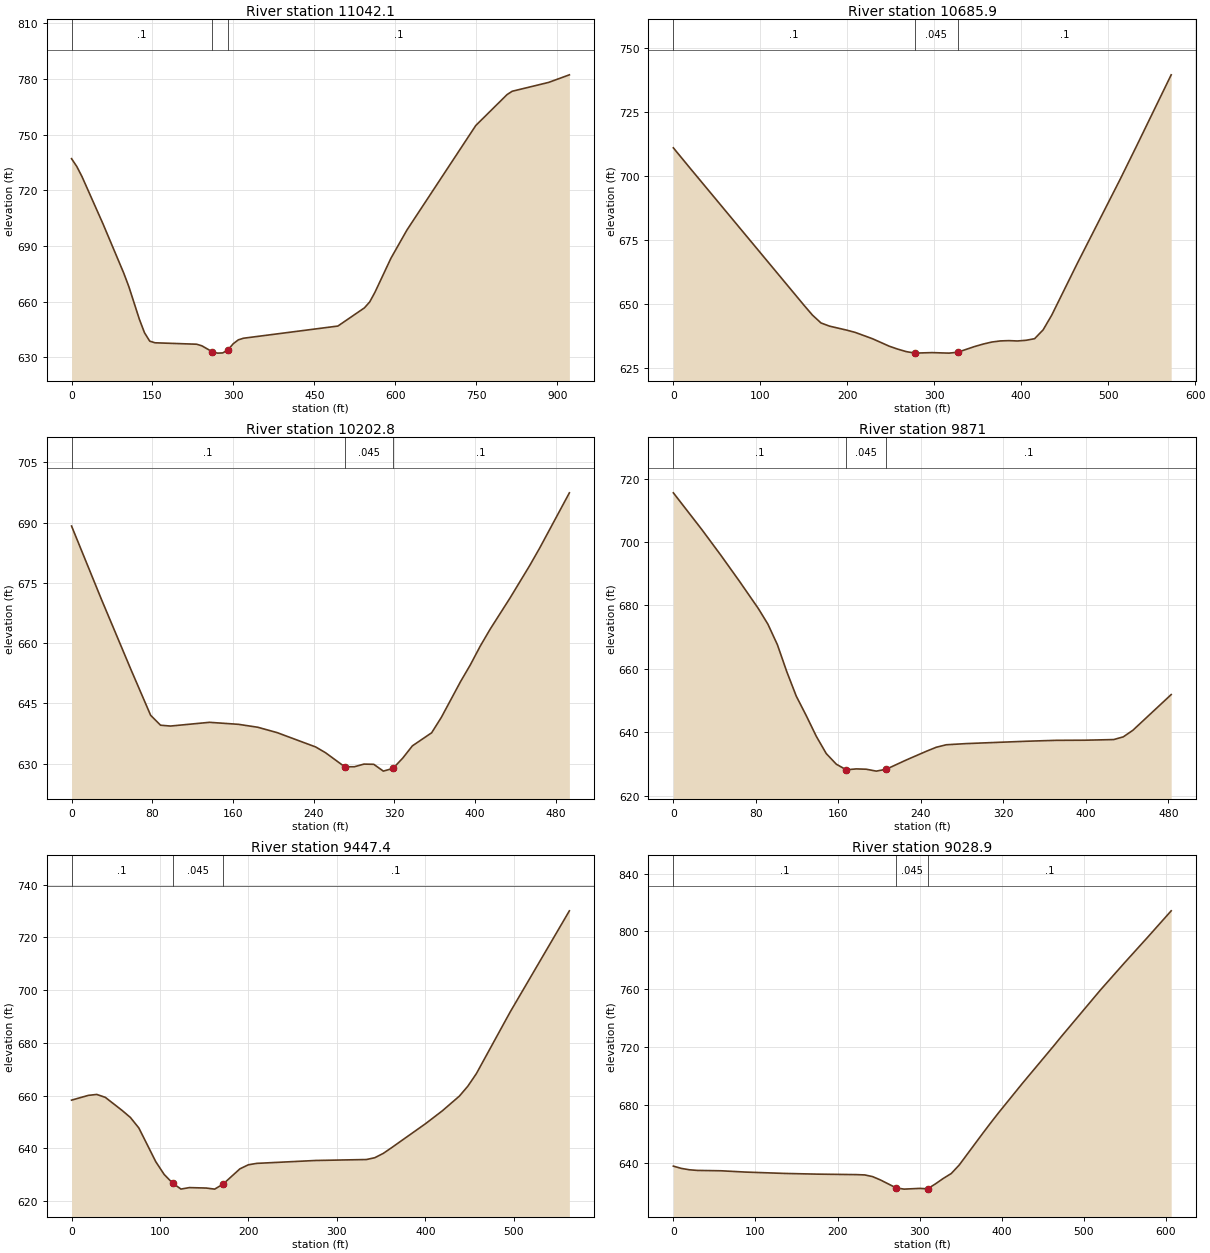
Type RM Length L Ch R = 1 ,11042.1 ,354.2,356.2,358.2
XS GIS Cut Line= 4
     1857169.667      529649.702      1857485.64      529337.202
     1857790.327      529346.751     1857950.049      529279.042
#Sta/Elev= 30
       0  737.07     9.7  732.87    19.3  727.44      58  702.12    96.6  675.47
   106.3  667.99   125.6  650.56   135.2  643.22   144.9  638.68   154.6   637.8
   231.9  637.02   241.5  636.17   260.1633.0623   270.5  632.22   280.2  632.33
   289.8  633.95   299.5  637.24   309.2   639.4   318.8  640.26   493.6  646.82
   542.7   656.6   552.6  659.82   562.4  665.08   591.9  683.36   621.4  698.51
   749.2  754.97   807.1  771.62   816.7  773.44   884.2  778.21   922.7   782.3
#Mann= 3 , 0 , 0
       0      .1       0   260.1    .045       0   289.8      .1       0
Bank Sta=260.1,289.8
XS Rating Curve= 0 ,0
Exp/Cntr=0.3,0.1

Type RM Length L Ch R = 1 ,10685.9 ,470.7,483.2,495.7
XS GIS Cut Line= 3
     1857356.299      529839.806     1857501.265      529772.098
     1857814.633      529503.869
#Sta/Elev= 30
       0  710.98    18.8  703.23   150.6  649.47     160  645.76   169.8  642.71
   179.6  641.47   199.3  639.92   209.1  639.03   228.8  636.59   248.4  633.63
   258.2  632.49     268  631.53   277.8  630.96   297.5  631.15   317.1  630.95
     327   631.3   346.6  633.54   356.4  634.49   366.2  635.27   376.1  635.71
   385.9  635.82   395.7  635.69   405.5  635.95   415.4  636.57   425.2  640.01
     435  645.68   464.4  665.84   513.6  698.57   533.2  712.05   572.5  739.44
#Mann= 3 , 0 , 0
       0      .1       0   277.8    .045       0     327      .1       0
Bank Sta=277.8,327
XS Rating Curve= 0 ,0
Exp/Cntr=0.3,0.1

Type RM Length L Ch R = 1 ,10202.8 ,340.9,331.7,322.6
XS GIS Cut Line= 4
     1857504.954      530156.647     1857613.531      530111.621
     1857888.952      530076.311     1857966.108      530015.588
#Sta/Elev= 30
       0  689.12    29.4     671    58.8  653.43    78.4     642    88.2  639.54
      98  639.33   136.7  640.26   165.4  639.76   184.6  639.03   203.7   637.7
     242  634.12   251.6  632.71   270.7   629.2   280.3   629.2   289.8  629.86
   299.5  629.81     309  628.11   318.6  628.79   328.2  631.34   337.8   634.4
   356.9  637.66   366.5   641.5   385.6  650.43   395.2  654.55     405  659.21
   414.9  663.46   434.5  671.18   454.1   679.3     464  683.66   493.4  697.39
#Mann= 3 , 0 , 0
       0      .1       0   270.7    .045       0   318.6      .1       0
Bank Sta=270.7,318.6
XS Rating Curve= 0 ,0
Exp/Cntr=0.3,0.1

Type RM Length L Ch R = 1 ,9871    ,443.6,423.6,403.7
XS GIS Cut Line= 4
     1857718.713      530537.506     1857796.838      530447.445
     1858013.851      530319.407     1858063.765      530219.581
#Sta/Elev= 30
       0  715.51    27.5  703.98    45.9   695.9    64.2  687.58    82.5  678.98
    91.7  674.09   100.9  667.62     110  659.12   119.2   651.4   128.9  645.24
   138.6  638.75   148.3  633.28     158  629.95   167.7  628.16   177.4  628.45
   187.1  628.35   196.8  627.75   206.4  628.34   225.8  631.25   245.2  633.99
   254.9  635.27   264.6  636.06     284  636.43   342.1  637.17   371.2  637.46
   399.1   637.5     427   637.7   436.3  638.55   445.6  640.62   482.8  651.89
#Mann= 3 , 0 , 0
       0      .1       0   167.7    .045       0   206.4      .1       0
Bank Sta=167.7,206.4
XS Rating Curve= 0 ,0
Exp/Cntr=0.3,0.1

Type RM Length L Ch R = 1 ,9447.4  ,386.1,418.5,450.8
XS GIS Cut Line= 3
     1858222.185      530693.756     1858265.588      530411.638
     1858432.688      530190.284
#Sta/Elev= 30
       0  658.25      19  660.06    28.5  660.41    38.1  659.32    57.1  654.36
    66.6  651.65    76.1  647.67    95.2   634.9   104.7  630.05   114.2  626.77
   123.7   624.5   133.2  625.06   152.2  624.89   161.8  624.48   171.3  626.39
   190.3  632.17   199.8  633.71   209.3  634.25   275.9  635.35   333.3  635.71
   342.8   636.4   352.4  638.04     362  640.25   400.2  649.32   419.3  654.23
   438.5   659.8     448  663.55   457.6  668.28   495.8  691.67   562.8  730.09
#Mann= 3 , 0 , 0
       0      .1       0   114.2    .045       0   171.3      .1       0
Bank Sta=114.2,171.3
XS Rating Curve= 0 ,0
Exp/Cntr=0.3,0.1

Type RM Length L Ch R = 1 ,9028.9  ,225.4,237.9,250.3
XS GIS Cut Line= 4
       1858273.4      530765.588     1858473.053      530722.185
     1858664.893      530723.921     1858865.414      530660.553
#Sta/Elev= 30
       0  637.83     9.7  636.27    19.5  635.31    29.2  634.87    58.4  634.61
    87.6  633.73   136.2  632.78   175.1   632.3   223.5  631.96   233.1  631.75
   242.7  630.59   252.3  628.28   271.5  622.78   281.1  621.94   300.2  622.45
   309.8  622.16   319.4  625.61     329  629.38   338.6  632.74   348.2  638.56
     377  660.54   386.6  667.72   396.2   674.7   424.8  694.72   463.1  720.71
   472.6  727.33   520.4   759.6   549.1  777.98   577.8  795.97   606.5  814.24
#Mann= 3 , 0 , 0
       0      .1       0   271.5    .045       0   309.8      .1       0
Bank Sta=271.5,309.8
XS Rating Curve= 0 ,0
Exp/Cntr=0.3,0.1

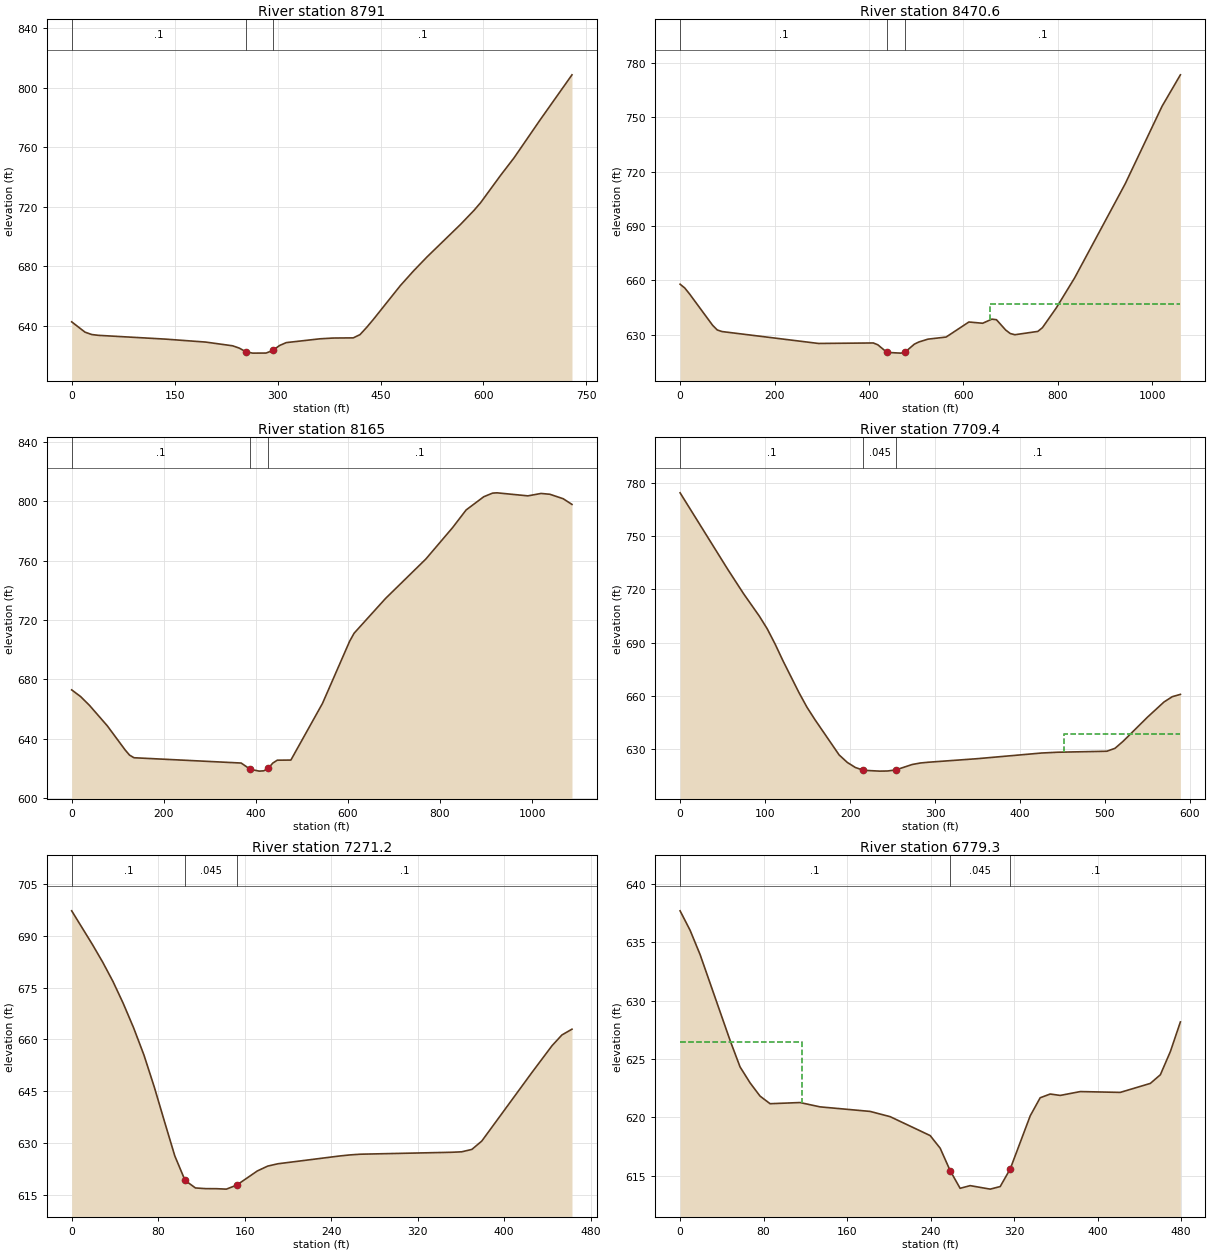
Type RM Length L Ch R = 1 ,8791    ,317.6,320.3,322.8
XS GIS Cut Line= 4
     1858249.963       530795.97     1858572.879      530998.226
     1858835.032      530969.581     1858911.421       530933.99
#Sta/Elev= 30
       0  642.61    19.5  635.65    29.3  634.06    39.1  633.53   136.8  630.98
   195.4  628.99   234.5  626.49   244.2  624.94     254  622.42   263.8  621.56
   283.3  621.61   293.1  623.38   302.9  626.69   312.6  628.63   361.5  631.18
     381  631.71   410.3  631.82   420.1     634   429.9  638.92   439.6  644.24
   478.7  666.87   498.2  676.92   517.8   686.3   566.6  708.16   586.1  717.54
   595.9   722.8   625.2   741.3   644.7  753.03   682.2  778.23     729   808.8
#Mann= 3 , 0 , 0
       0      .1       0     254    .045       0   293.1      .1       0
Bank Sta=254,293.1
XS Rating Curve= 0 ,0
Exp/Cntr=0.3,0.1

Type RM Length L Ch R = 1 ,8470.6  ,276.7,305.7,334.7
XS GIS Cut Line= 5
     1858180.952      530797.923      1858227.61      530895.579
     1858217.845      531138.634     1858420.753      531301.395
     1858785.336      531561.812
#Sta/Elev= 30
       0  657.81     9.8  655.73    19.7  652.54    68.9  635.11    78.7  632.54
    88.6  631.66   293.1  625.08   409.3  625.35   418.9  624.32   438.2  620.14
   467.1  619.74   476.7  620.33     496  624.67   505.6  625.89   524.9  627.46
   563.4  628.62   611.6  636.93   640.8  636.24   660.3   638.5     670   638.2
   689.5  632.51   699.3  630.56     709   629.9   757.7  631.74   767.4   633.8
   796.7   644.7   835.6   661.3   942.8  713.31  1020.7  756.06  1059.6  773.44
#Mann= 3 , 0 , 0
       0      .1       0   438.2    .045       0   476.7      .1       0
#XS Ineff= 2 , 0
                          656.94           646.8
Permanent Ineff=
       F       F
Bank Sta=438.2,476.7
XS Rating Curve= 0 ,0
Exp/Cntr=0.3,0.1

Type RM Length L Ch R = 1 ,8165    ,474.7,455.5,436.4
XS GIS Cut Line= 5
      1858064.85      530783.817     1858061.114      531112.641
     1857956.343       531377.35     1858080.041      531586.768
     1858253.652      531737.593
#Sta/Elev= 30
       0  672.88    19.3  668.39    38.7  662.42    77.4  648.62   116.1  632.36
   125.7  628.86   135.4  627.09   368.1  623.52   387.8  619.32   407.4  618.06
   417.2  618.26     427  619.94   436.8  623.48   446.6  625.44   476.1  625.52
   544.8  663.77   603.7  705.66   613.5  711.13   681.6  734.52   769.2  761.14
   827.6  782.45   856.8  794.29   895.1   803.2   914.2  805.64   923.8  805.84
   990.9  803.79  1019.7  805.42  1038.8  804.86  1067.6  801.86  1086.7  798.01
#Mann= 3 , 0 , 0
       0      .1       0   387.8    .045       0     427      .1       0
Bank Sta=387.8,427
XS Rating Curve= 0 ,0
Exp/Cntr=0.3,0.1

Type RM Length L Ch R = 1 ,7709.4  ,464.7,438.2,411.7
XS GIS Cut Line= 4
     1857453.088      530887.983     1857576.351       530987.81
     1857713.504      531260.379     1857826.351      531314.199
#Sta/Elev= 30
       0  774.21      56  731.25    74.6  717.55    93.3  704.83   102.6  697.69
     112  688.99   121.3  679.53     140  661.77   149.3  653.66   158.6  646.73
   187.2  626.79   196.8  622.59   206.3  619.74   215.8  618.17   234.9   617.7
   244.4  617.78     254   618.4     273  621.41   282.6  622.26   292.1   622.7
   349.3  624.68   425.6  627.89   444.7  628.33   502.2  628.88   511.8  630.52
   521.4  634.49   550.3  648.16   569.5  656.58   579.2  659.56   588.8  660.86
#Mann= 3 , 0 , 0
       0      .1       0   215.8    .045       0     254      .1       0
#XS Ineff= 2 , 0
                           451.7           638.7
Permanent Ineff=
       F       F
Bank Sta=215.8,254
XS Rating Curve= 0 ,0
Exp/Cntr=0.3,0.1

Type RM Length L Ch R = 1 ,7271.2  ,506.1,491.9,476.3
XS GIS Cut Line= 3
      1857358.47      531466.108     1857663.157      531447.011
     1857819.407      531466.976
#Sta/Elev= 30
       0  697.23    19.1  687.52    28.6  682.41    38.2  676.76    47.7   670.4
    57.2  663.39    66.8  655.49    76.3  646.28    85.9  636.12    95.4   626.2
   104.9   619.1   114.5  616.92     124  616.72   133.6  616.71   143.1  616.58
   152.6  617.73   171.7  621.84   181.3  623.25   190.8  623.93     248  626.19
   257.6   626.5   267.1   626.7   351.6  627.26   360.9   627.4   370.2  628.09
   379.4  630.52   425.7  650.36   444.3  658.13   453.5  661.26   462.8  662.93
#Mann= 3 , 0 , 0
       0      .1       0   104.9    .045       0   152.6      .1       0
Bank Sta=104.9,152.6
XS Rating Curve= 0 ,0
Exp/Cntr=0.3,0.1

Type RM Length L Ch R = 1 ,6779.3  ,98.6,99,99.3
XS GIS Cut Line= 3
     1857355.654      532000.245     1857486.074      532031.213
     1857749.937      531808.781
#Sta/Elev= 30
       0  637.69     9.6  636.02    19.2  633.93    47.9  626.58    57.4  624.32
      67  622.95    76.6  621.81    86.2  621.16   114.9  621.26     134  620.89
     182   620.5   201.2  620.05   239.5  618.43   249.1  617.35   258.7  615.42
   268.2  613.91   277.8  614.14     297  613.84   306.6  614.06   316.2  615.57
   335.4  620.13   344.9  621.67   354.5  621.99   364.1  621.87   383.3   622.2
   421.6  622.13   450.4   622.9     460  623.64   469.6  625.63   479.2  628.17
#Mann= 3 , 0 , 0
       0      .1       0   258.7    .045       0   316.2      .1       0
#XS Ineff= 2 , 0
           116.5  626.43
Permanent Ineff=
       F       F
Bank Sta=258.7,316.2
XS Rating Curve= 0 ,0
Exp/Cntr=0.3,0.1

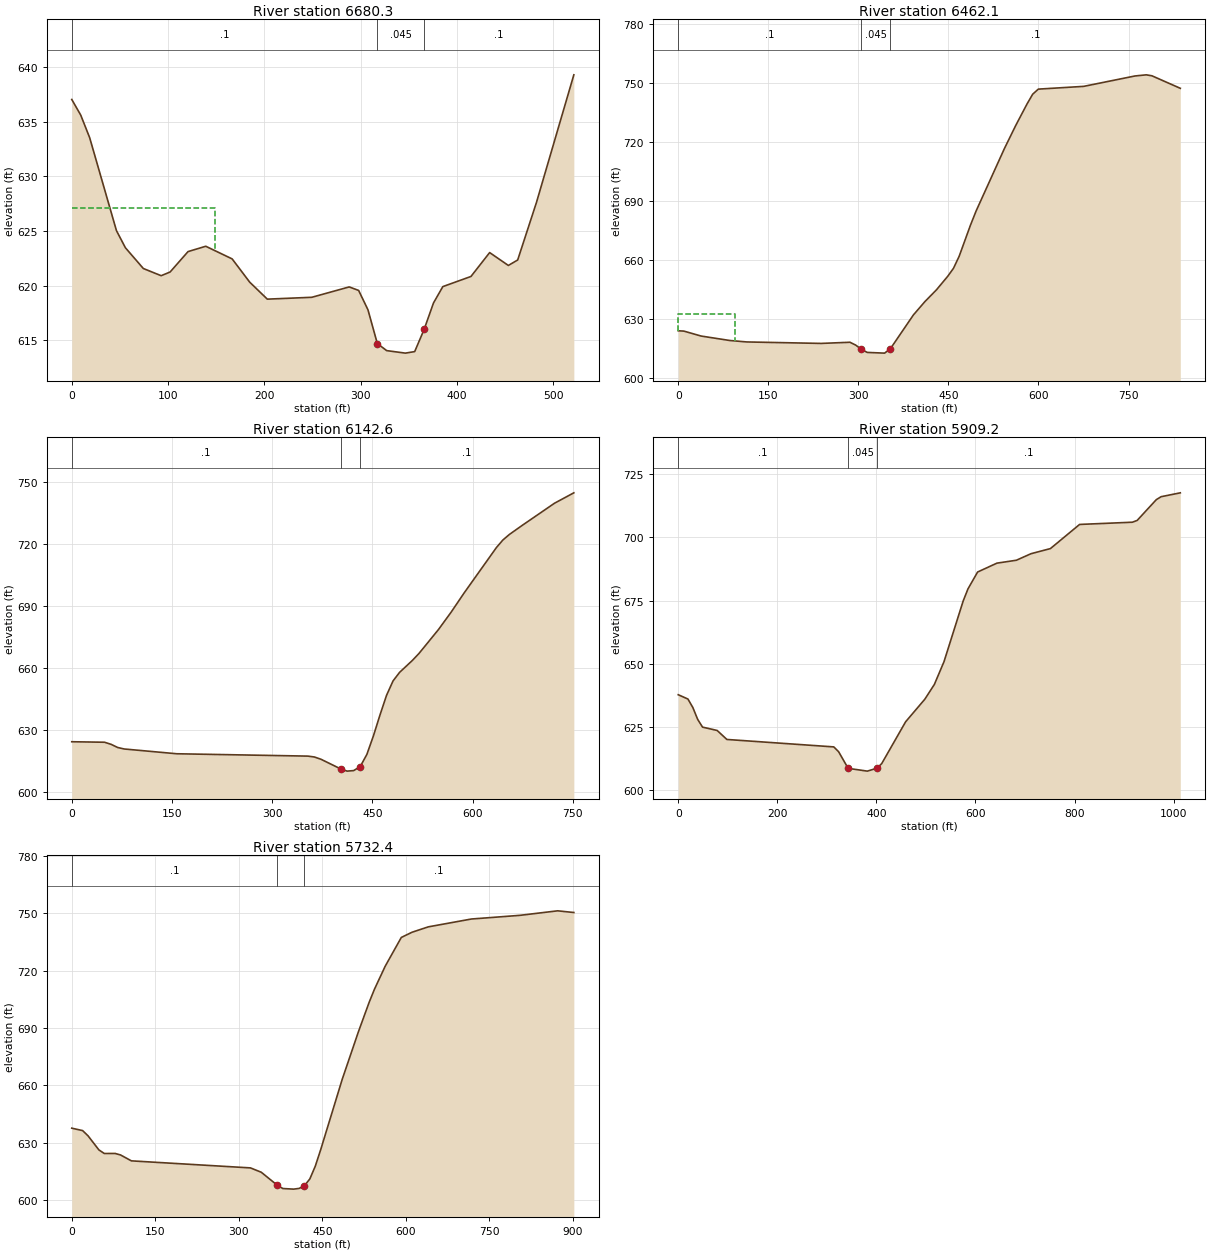
Type RM Length L Ch R = 1 ,6680.3  ,203.9,218.3,232.7
XS GIS Cut Line= 4
     1857346.759      532039.978     1857466.549      532090.379
     1857575.697      532081.681     1857791.508      531900.506
#Sta/Elev= 30
       0  637.06     9.3  635.63    18.6  633.55    46.4  625.03    55.7  623.46
    74.3  621.56    92.8   620.9   102.1  621.24   120.7  623.11   139.1   623.6
   166.5  622.44   184.7  620.31     203  618.75   249.2  618.92     288  619.87
   297.8  619.55   307.5  617.77   317.2  614.68   326.9  614.03   346.3   613.8
     356  613.94   365.8  615.98   375.5   618.4   385.2   619.9   414.4  620.83
   433.8  623.02   453.2  621.84   462.9  622.34   482.4  627.62   521.2  639.32
#Mann= 3 , 0 , 0
       0      .1       0   317.2    .045       0   365.8      .1       0
#XS Ineff= 2 , 0
          148.37   627.1
Permanent Ineff=
       F       F
Bank Sta=317.2,365.8
XS Rating Curve= 0 ,0
Exp/Cntr=0.3,0.1

Type RM Length L Ch R = 1 ,6462.1  ,292.2,319.5,346.8
XS GIS Cut Line= 5
      1857428.89      532110.892     1857585.887      532234.116
     1857815.906      532218.599     1857971.077      532150.141
     1858192.881      532232.291
#Sta/Elev= 30
       0  623.85     9.5  623.68      38  621.18    85.5  618.92     114  618.17
     238  617.42     286  618.01   295.6  616.56   305.2  614.38   314.8  612.84
   343.7  612.48   353.3   614.7   391.7  631.92   410.9  638.73   430.1   644.7
     449  651.64   458.4  655.64   467.8   661.7   486.7  677.59   496.1   684.8
   543.2  716.55     562  728.27   580.9  739.26   590.3  744.22   599.7  746.82
   675.4  748.23   760.6  753.51   779.5   754.1     789   753.6   836.2  747.24
#Mann= 3 , 0 , 0
       0      .1       0   305.2    .045       0   353.3      .1       0
#XS Ineff= 2 , 0
           94.19  632.53
Permanent Ineff=
       F       F
Bank Sta=305.2,353.3
XS Rating Curve= 0 ,0
Exp/Cntr=0.3,0.1

Type RM Length L Ch R = 1 ,6142.6  ,222.9,233.3,243.7
XS GIS Cut Line= 3
     1857381.426      532086.247     1857591.502      532529.741
     1857810.429      532671.335
#Sta/Elev= 30
       0   624.1    49.1  623.86    58.9  622.84    68.7  621.32    78.5  620.59
     157  618.28   353.3  617.14   363.1  616.72     373  615.62   402.4  610.96
   412.2  609.87     422  610.13   431.8  612.11   441.7  617.96   451.5  626.94
   461.3  637.02   471.1  646.54   480.9  653.56   490.7   657.7     510  663.53
   519.7  666.85   548.7  678.36     568  686.93   587.3  696.16   635.6  718.13
   645.2  721.76   654.9  724.45   674.2  728.87   722.5  739.59   751.5  744.64
#Mann= 3 , 0 , 0
       0      .1       0   402.4    .045       0   431.8      .1       0
Bank Sta=402.4,431.8
XS Rating Curve= 0 ,0
Exp/Cntr=0.3,0.1

Type RM Length L Ch R = 1 ,5909.2  ,166.8,176.9,185.9
XS GIS Cut Line= 6
     1857266.416      532109.066     1857334.874      532395.677
     1857332.136      532559.976     1857444.407      532680.462
     1857594.102      532791.821     1857609.619      532994.456
#Sta/Elev= 30
       0   637.8    19.6   636.1    29.5  632.74    39.3  628.04    49.1     625
    78.6  623.68    98.2  620.13     314  617.19   323.7   615.3     343  608.72
   381.7  607.62     401  608.76   410.7  610.58     459  627.11   497.7  636.01
   517.1  641.89   536.5  650.87   575.2  674.84   584.9  679.62   604.3  686.27
   643.3  689.78   682.6  690.93   712.1  693.51   751.3  695.53   810.2  705.07
   916.7  705.95   926.4  706.66   965.1  714.87   974.8  716.03  1013.5  717.56
#Mann= 3 , 0 , 0
       0      .1       0     343    .045       0     401      .1       0
Bank Sta=343,401
XS Rating Curve= 0 ,0
Exp/Cntr=0.3,0.1

Type RM Length L Ch R = 1 ,5732.4  ,379.8,389.5,400.2
XS GIS Cut Line= 5
     1857255.463      532107.241     1857236.295      532310.789
     1857136.803      532542.634     1857046.438      532643.039
     1857095.728      532948.818
#Sta/Elev= 30
       0   637.7    19.5  636.43    29.2  633.71    48.7  626.35    58.4  624.47
    77.9  624.49    87.6   623.7   107.1  620.62   320.9  616.94   340.3  614.67
   369.4  607.81   379.1  606.16   398.5  605.85   408.2  606.22   417.9  607.65
   427.6  611.23   437.3  617.84     447  626.45   485.7  663.26   514.6  687.95
   533.9  703.36   543.6  710.33   562.9  722.35   591.8  737.36   611.2  740.09
   640.2  742.88   717.6  746.98   804.8   748.9   872.5  751.26   901.6  750.38
#Mann= 3 , 0 , 0
       0      .1       0   369.4    .045       0   417.9      .1       0
Bank Sta=369.4,417.9
XS Rating Curve= 0 ,0
Exp/Cntr=0.3,0.1