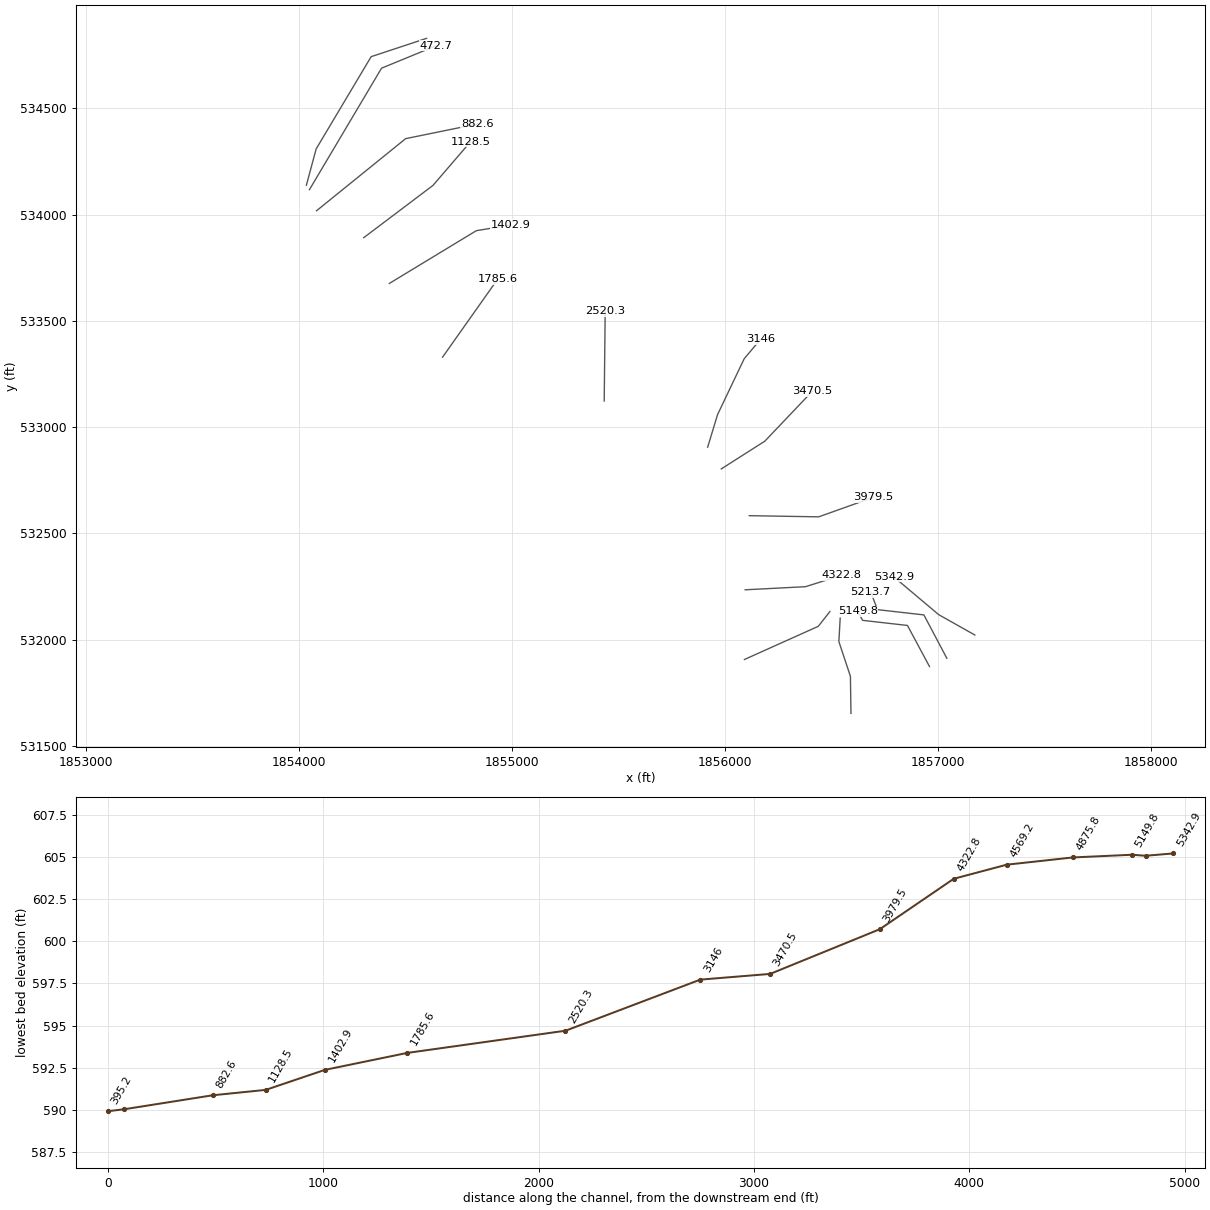
HEC-RAS study FALLINGRCR.prj: FALLINGRCR

--- FALLINGRCR.g01 (geometry) --- (continued)

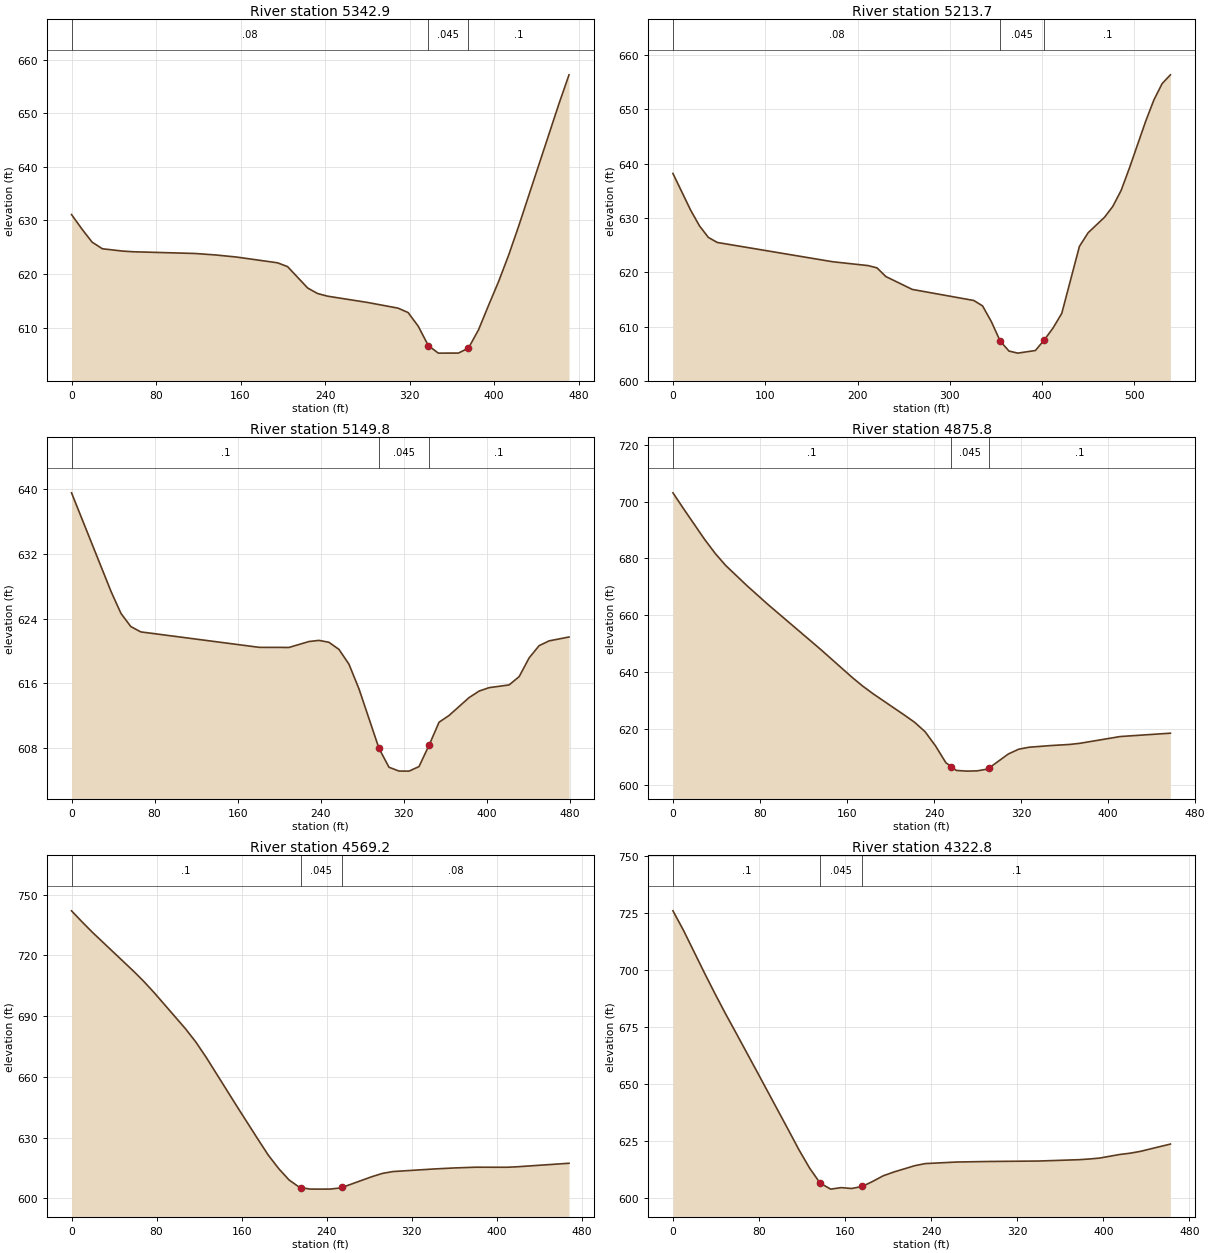
Type RM Length L Ch R = 1 ,5342.9  ,114.2,129.1,143
XS GIS Cut Line= 3
     1857171.488      532022.353     1857001.712      532118.194
     1856790.862      532296.185
#Sta/Elev= 29
       0  631.09     9.8   628.4    19.5  625.94    29.2  624.71    48.7  624.27
    58.5  624.15     117  623.83   136.5  623.55     156  623.17     195  622.09
   204.5  621.38   223.5  617.39     233  616.35   242.5  615.86   280.6  614.68
   309.1  613.63   318.6  612.81   328.2  610.26   337.7  606.65   347.2  605.24
   366.2  605.25   375.7  606.17   385.3  609.61   394.8  614.18   404.3  618.62
   413.8  623.54   423.3  628.96   461.4  651.77   470.9  657.16
#Mann= 3 , 0 , 0
       0     .08       0   337.7    .045       0   375.7      .1       0
Bank Sta=337.7,375.7
XS Rating Curve= 0 ,0
Exp/Cntr=0.3,0.1

Type RM Length L Ch R = 1 ,5213.7  ,64.9,63.9,63.9
XS GIS Cut Line= 4
     1857040.049       531912.82     1856932.394      532116.835
     1856714.574      532141.687     1856682.538      532224.875
#Sta/Elev= 30
       0   638.2    19.2  631.44    28.8  628.54    38.4  626.42    48.1  625.49
     173  621.94   211.4  621.23   221.1  620.81   230.7  619.21   259.3  616.84
     326   614.8   335.5   613.8   345.1  610.87   354.6  607.31   364.1  605.48
   373.6   605.1   392.7  605.58   402.2   607.5   411.8  609.72   421.3  612.43
   440.4  624.76   449.9  627.29   467.7  630.15   476.6  632.14   485.6  635.08
   494.5  639.16   512.3  647.87   521.2  651.79   530.1  654.78     539  656.38
#Mann= 3 , 0 , 0
       0     .08       0   354.6    .045       0   402.2      .1       0
Bank Sta=354.6,402.2
XS Rating Curve= 0 ,0
Exp/Cntr=0.3,0.1

Type RM Length L Ch R = 1 ,5149.8  ,300.7,274,247.7
XS GIS Cut Line= 4
      1856958.58       531874.18     1856855.226      532067.275
     1856644.457      532091.322     1856621.774      532133.729
#Sta/Elev= 30
       0  639.54    38.1  627.34    47.6  624.65    57.1  623.02    66.7  622.36
   180.9  620.45   209.5  620.44   228.7  621.17   238.3  621.31   247.9  621.08
   257.6   620.2   267.2  618.38   276.9  615.32   296.2  607.96   305.8  605.64
   315.4  605.17   325.1  605.16   334.7  605.72   344.4  608.36     354   611.2
   363.6  612.03   382.9  614.24   392.6  615.05   402.2  615.47   421.5  615.81
   431.2  616.84   440.8  619.15   450.4  620.66     460  621.25   479.2  621.73
#Mann= 3 , 0 , 0
       0      .1       0   296.2    .045       0   344.4      .1       0
Bank Sta=296.2,344.4
XS Rating Curve= 0 ,0
Exp/Cntr=0.3,0.1

Type RM Length L Ch R = 1 ,4875.8  ,340,306.7,272.9
XS GIS Cut Line= 4
     1856590.004      531653.694     1856587.439      531828.074
     1856533.194      531991.472     1856539.498      532102.004
#Sta/Elev= 30
       0  703.06     9.7   697.5    29.1  686.67    38.8  681.74    48.4   677.5
    67.8  670.44    87.2  663.77   135.6  647.95   164.7  638.04   174.4  634.98
     184  632.26   212.7  624.77   222.2   622.2   231.8  618.88   241.4  613.88
   250.9  607.97   255.8606.5795   260.5  605.25     270     605   279.6  605.09
   289.2  605.72   290.4606.0458   308.3  611.04   317.9  612.73   327.4  613.42
   346.6  613.99     365  614.41   374.2  614.81   411.2  617.19   457.3  618.37
#Mann= 3 , 0 , 0
       0      .1       0   255.8    .045       0   290.4      .1       0
Bank Sta=255.8,290.4
XS Rating Curve= 0 ,0
Exp/Cntr=0.3,0.1

Type RM Length L Ch R = 1 ,4569.2  ,254.7,246.3,237.9
XS GIS Cut Line= 3
     1856090.004      531907.167     1856436.716      532063.281
     1856490.925      532132.424
#Sta/Elev= 30
       0  742.04     9.8  736.65    19.5   731.5    58.5  712.16    68.2  707.06
      78  701.48   107.2   683.8     117  677.21   126.8  669.59     156  645.16
   175.5  629.13   185.2  621.32     195  614.67   204.7  609.09   214.5  605.46
   215.5605.3714   224.2   604.6     234  604.57   243.7   604.6   253.5   605.2
   254.7605.4252   282.7  610.73   292.5  612.33   302.2  613.24   341.2  614.53
   360.7  615.04   380.2   615.4   409.5  615.37   419.3  615.61   468.1  617.35
#Mann= 3 , 0 , 0
       0      .1       0   215.5    .045       0   254.7     .08       0
Bank Sta=215.5,254.7
XS Rating Curve= 0 ,0
Exp/Cntr=0.3,0.1

Type RM Length L Ch R = 1 ,4322.8  ,344.9,343.3,341.8
XS GIS Cut Line= 3
     1856093.503      532235.029     1856376.463      532249.634
     1856547.151      532303.487
#Sta/Elev= 30
       0  725.88     9.8  717.32    29.3  698.61    39.1  689.49    48.8  680.77
    58.6  672.33    78.2  655.23   107.5  629.53   117.2  620.93     127  612.97
   136.8  606.36   146.6  603.73   156.3  604.39   166.1  604.01   175.9   604.9
   185.6  607.11   195.4  609.58   205.2  611.23   224.7  614.02   234.5  614.94
   263.8  615.63   292.8  615.86   339.9  616.06   377.5  616.65     387  616.96
   396.4  617.35   415.2  618.94   424.6  619.48   434.1  620.27   462.3  623.51
#Mann= 3 , 0 , 0
       0      .1       0   136.8    .045       0   175.9      .1       0
Bank Sta=136.8,175.9
XS Rating Curve= 0 ,0
Exp/Cntr=0.3,0.1

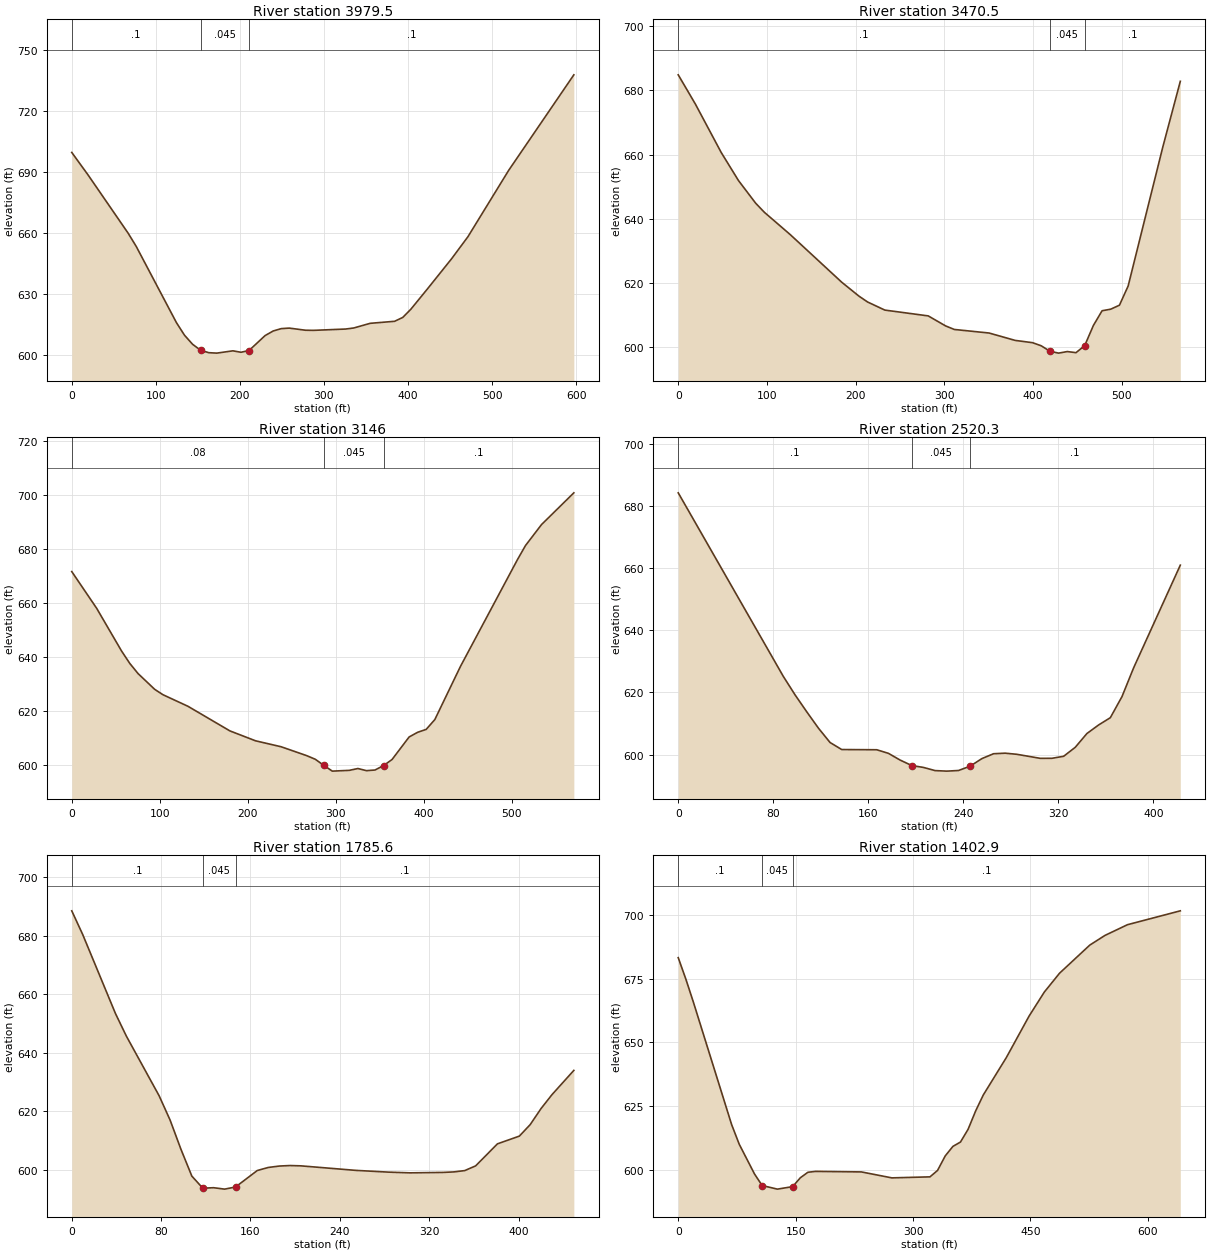
Type RM Length L Ch R = 1 ,3979.5  ,490,509.1,528.1
XS GIS Cut Line= 3
     1856112.671      532583.709     1856438.531      532578.232
     1856694.108      532669.509
#Sta/Elev= 30
       0  699.45    19.2  688.49    67.1  659.71    76.7  653.21   124.6  615.67
   134.2   609.5   143.8  605.06   153.4  602.12     163  600.95   172.5  600.73
   191.7  601.86   201.3  601.15   210.9  602.02     230  609.36   239.6  611.62
   249.2  612.78   258.8  613.04     278  611.99   287.6  611.93   325.9  612.58
   335.6  613.11     355  615.39   384.1  616.39   393.8   618.3   403.4  622.32
   422.8  632.15   451.9  647.17   471.3  657.99   519.8  690.66   597.3  737.63
#Mann= 3 , 0 , 0
       0      .1       0   153.4    .045       0   210.9      .1       0
Bank Sta=153.4,210.9
XS Rating Curve= 0 ,0
Exp/Cntr=0.3,0.1

Type RM Length L Ch R = 1 ,3470.5  ,317.3,324.4,331.6
XS GIS Cut Line= 3
     1855981.232      532803.687     1856185.693      532934.213
      1856408.41      533168.796
#Sta/Elev= 30
       0  684.85    19.4   675.7    48.5  660.61    67.9  651.89    87.3  644.82
      97  642.01   126.1  635.07   184.4  620.16   203.8  615.83   213.5  614.01
   232.9  611.49   281.8  609.68   301.4  606.56   311.2  605.45   350.4  604.34
   379.8  602.04   399.4  601.33   409.2  600.36     419  598.66   428.8  598.07
   438.6  598.56   448.4  598.21   458.2   600.4     468  606.69   477.8  611.28
   487.6  611.78   497.4  613.02   507.2     619   546.4  662.48     566  682.83
#Mann= 3 , 0 , 0
       0      .1       0     419    .045       0   458.2      .1       0
Bank Sta=419,458.2
XS Rating Curve= 0 ,0
Exp/Cntr=0.3,0.1

Type RM Length L Ch R = 1 ,3146    ,615.9,625.7,635.6
XS GIS Cut Line= 4
     1855917.338      532905.917     1855963.889      533059.263
     1856088.939      533322.142     1856165.612      533413.419
#Sta/Elev= 30
       0  671.72    28.3   658.1    56.6  642.26      66  637.64    75.4  633.88
    94.3  628.04   103.7  626.05     132  621.78   179.7  612.65   208.8  608.98
   237.9  606.77     267  603.47   276.7  602.14   286.4  599.87   296.1  597.73
   315.5  598.02   325.2   598.7   334.9   597.9   344.6  598.14   354.3  599.77
     364  602.04   383.4  610.39   393.1  612.13   402.8  613.21   412.6  616.84
   441.7  636.53   506.4  676.08   515.6  681.35   533.9  689.16   570.6  700.92
#Mann= 3 , 0 , 0
       0     .08       0   286.4    .045       0   354.3      .1       0
Bank Sta=286.4,354.3
XS Rating Curve= 0 ,0
Exp/Cntr=0.3,0.1

Type RM Length L Ch R = 1 ,2520.3  ,748.4,734.7,720.7
XS GIS Cut Line= 2
     1855431.742      533123.157     1855436.306      533545.771
#Sta/Elev= 30
       0  684.16    88.5  625.11    98.3  619.23   108.1   613.8     118  608.51
   127.8  603.89   137.6  601.63   167.1  601.56   176.9  600.41   186.8  598.24
   196.6  596.48   206.4  595.88   216.2  594.86   226.1  594.69   235.9  594.89
   245.7  596.28   255.6  598.72   265.4  600.28   275.2  600.46     285   600.1
   304.7   598.8   314.5  598.81   324.4  599.46   334.2  602.36     344  606.78
   353.8  609.52   363.7  611.87   373.5  618.64   383.3  627.89   422.6  660.91
#Mann= 3 , 0 , 0
       0      .1       0   196.6    .045       0   245.7      .1       0
Bank Sta=196.6,245.7
XS Rating Curve= 0 ,0
Exp/Cntr=0.3,0.1

Type RM Length L Ch R = 1 ,1785.6  ,392.1,382.7,373.3
XS GIS Cut Line= 2
     1854672.864      533329.313     1854931.921      533696.703
#Sta/Elev= 30
       0  688.45     9.8  680.35    39.1  653.38    48.9  645.63    78.2  625.27
      88     617    97.7  607.03   107.5  597.82   117.3  593.69     127  593.85
   136.8  593.37   146.6  594.09   166.1  599.73   175.9  600.77   185.7  601.25
   195.4  601.43   205.2  601.32   254.1  599.78   283.4  599.18     303  598.93
   332.3  599.08     342  599.25   351.8   599.7   361.6  601.32   381.1  608.84
   400.7  611.48   410.4   615.4   420.2  620.93     430  625.68   449.5  633.94
#Mann= 3 , 0 , 0
       0      .1       0   117.3    .045       0   146.6      .1       0
Bank Sta=117.3,146.6
XS Rating Curve= 0 ,0
Exp/Cntr=0.3,0.1

Type RM Length L Ch R = 1 ,1402.9  ,272,274.4,276.9
XS GIS Cut Line= 3
     1854423.227      533676.292     1854831.438      533924.359
     1854993.153       533951.05
#Sta/Elev= 30
       0  683.28     9.8   674.8    19.5  665.68    68.2  617.74      78  609.96
    97.5   598.3   107.2  593.78   126.7  592.36   146.2  593.34     156  596.81
   165.7  598.98   175.5  599.33     234  599.12     273  596.78   321.7  597.18
   331.4  599.71   341.2  605.41     351  609.14   360.7  610.87   370.4  615.86
   380.2  623.17   389.9  629.38   419.2     644   448.4  660.36   467.9   669.8
   487.3  677.18   525.9  688.21   545.2     692   574.1  696.23   641.6  701.68
#Mann= 3 , 0 , 0
       0      .1       0   107.2    .045       0   146.2      .1       0
Bank Sta=107.2,146.2
XS Rating Curve= 0 ,0
Exp/Cntr=0.3,0.1

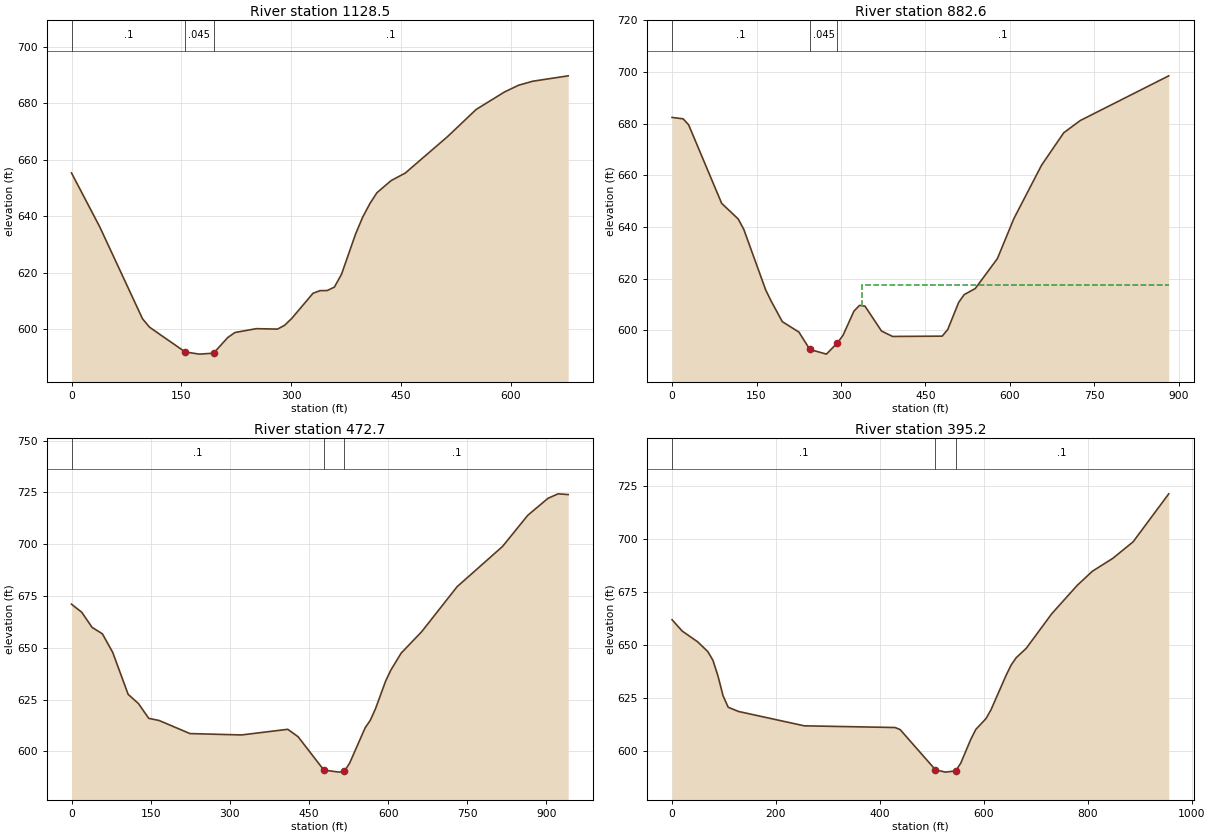
Type RM Length L Ch R = 1 ,1128.5  ,245.3,245.9,246.5
XS GIS Cut Line= 3
     1854302.861      533891.439     1854627.861      534137.272
      1854804.25      534342.828
#Sta/Elev= 30
       0  655.31    38.8   636.1      97  603.68   106.7  600.68   155.2  591.95
   174.6  591.17     194   591.5   213.4  597.04   223.2  598.82   252.3  600.18
   281.4  600.03   291.1  601.38   300.8   603.8   329.9  612.72   339.6  613.64
   349.3  613.68     359  614.88   368.7  619.38   388.1  633.75   397.8   639.7
   407.5  644.43   417.2  648.31   436.5  652.58   455.9  655.26   513.9  668.22
   552.6  677.75   591.3  683.94   610.6  686.34     630  687.76   678.4  689.67
#Mann= 3 , 0 , 0
       0      .1       0   155.2    .045       0     194      .1       0
Bank Sta=155.2,194
XS Rating Curve= 0 ,0
Exp/Cntr=0.3,0.1

Type RM Length L Ch R = 1 ,882.6   ,400.8,409.9,418.9
XS GIS Cut Line= 3
     1854081.448      534018.152      1854499.62      534357.288
     1854836.194      534426.161
#Sta/Elev= 30
       0  682.41    19.6  681.88    29.4  679.58    88.1  649.18   117.5  643.12
   127.3  639.17   166.4  615.63   176.2  611.28   195.8  603.41   225.2  599.39
   244.7  592.66   274.1  590.85   293.7   595.2   303.5   598.1     323  607.48
   332.8   609.7   342.6  609.42     372  599.78   391.6  597.69   479.7  597.81
   489.5  600.35     509  610.88   518.8  613.88   538.4  616.22   577.7   627.8
   607.1  643.33   656.2  663.96   695.5  676.47   724.9  681.22     882  698.51
#Mann= 3 , 0 , 0
       0      .1       0   244.7    .045       0   293.7      .1       0
#XS Ineff= 2 , 0
                          337.11           617.4
Permanent Ineff=
       F       F
Bank Sta=244.7,293.7
XS Rating Curve= 0 ,0
Exp/Cntr=0.3,0.1

Type RM Length L Ch R = 1 ,472.7   ,78,77.5,77
XS GIS Cut Line= 3
     1854048.115      534117.457     1854386.401      534688.662
     1854642.993      534794.454
#Sta/Elev= 30
       0  671.06    19.5  667.14      39  659.87    58.6  656.74    78.1   647.8
   107.4  627.54   126.9  623.11   146.4  615.97     166  614.95   224.5  608.62
   322.2  607.96     410  610.69   429.6  607.07   478.4  590.98   507.7  590.02
   517.4  590.52   527.2  594.38   556.5  611.38   566.2  614.99     576  620.49
   595.5  634.04   605.3  639.27   624.8  647.43   663.9  657.84   730.9  679.51
     817  698.92   864.8  713.95   903.1  722.13   922.3   724.3   941.4  723.94
#Mann= 3 , 0 , 0
       0      .1       0   478.4    .045       0   517.4      .1       0
Bank Sta=478.4,517.4
XS Rating Curve= 0 ,0
Exp/Cntr=0.3,0.1

Type RM Length L Ch R = 1 ,395.2   ,395.4,395.2,395
XS GIS Cut Line= 4
     1854033.618      534138.204     1854079.533      534308.914
     1854337.675      534742.933     1854597.854      534829.176
#Sta/Elev= 30
       0  661.78    19.6  656.42    49.1   651.4    68.8  646.76    78.6   642.7
    88.4  635.26    98.2   625.9     108  620.52   127.7  618.52   254.5  611.74
   429.3  610.94     439  609.96     507  590.98   526.4   589.9   545.8  590.49
   555.5  594.07   574.9  605.35   584.6  610.04   604.1  615.12   613.8   619.3
   642.9  635.57   652.6  640.41   662.3  643.85   681.8  648.34   730.7  664.59
   779.7  677.98     809  684.66   848.2  690.72   887.3  698.52   955.9  721.16
#Mann= 3 , 0 , 0
       0      .1       0     507    .045       0   545.8      .1       0
Bank Sta=507,545.8
XS Rating Curve= 0 ,0
Exp/Cntr=0.3,0.1

Chan Stop Cuts=-1
Use User Specified Reach Order=0
Composite Channel Slope=5